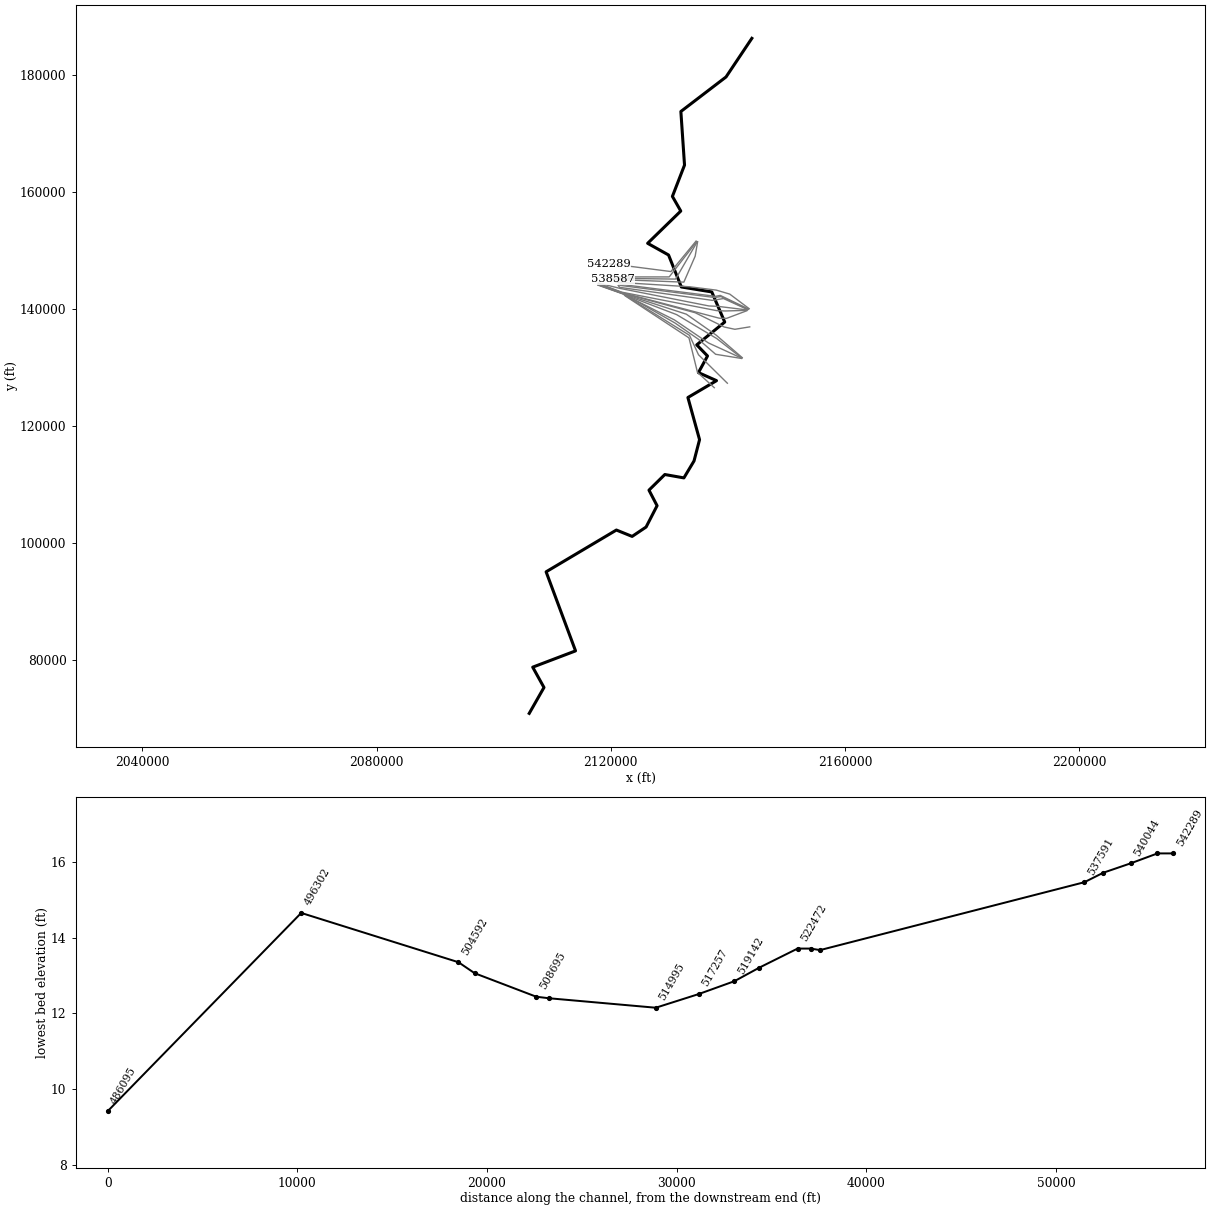
--- Waccamaw River.prj (project) ---

Proj Title=Waccamaw River Detailed Study
Current Plan=p01
Default Exp/Contr=0.3,0.1
English Units
Geom File=g01
Flow File=f01
Flow File=f02
Plan File=p01
Plan File=p02
Y Axis Title=Elevation
X Axis Title(PF)=Main Channel Distance
X Axis Title(XS)=Station
BEGIN DESCRIPTION:
Waccamaw River
END DESCRIPTION:
DSS Export Rating Curves= 0
DSS Export Rating Curve Sorted= 0
DSS Export Volume Flow Curves= 0
DXF OffsetX= 0
DXF OffsetY= 0
DXF ScaleX= 1
DXF ScaleY= 10

--- Waccamaw River.p01 (plan) ---

Plan Title=Multiple Run
Short Identifier=Multiple
Geom File=g01
Flow File=f01
Subcritical Flow
K Sum by GR= 0
Std Step Tol= 0.01
Critical Tol= 0.01
Num of Std Step Trials= 20
Max Error Tol= 0.3
Flow Tol Ratio= 0.001
Split Flow NTrial= 30
Split Flow Tol= 0.02
Split Flow Ratio= 0.02
Log Output Level= 0
Friction Slope Method= 1
Unsteady Friction Slope Method= 2
Unsteady Bridges Friction Slope Method= 1
Parabolic Critical Depth
Global Vel Dist=  1 , 1 , 1
Global Log Level= 0
CheckData=True
Encroach Param= -1, 0, 0, 0
BEGIN DESCRIPTION:
Multiple Run
END DESCRIPTION:

--- Waccamaw River.p02 (plan) ---

Plan Title=Floodway Run
Program Version=4.00
Short Identifier=Floodway
Geom File=g01
Flow File=f02
Subcritical Flow
K Sum by GR= 0
Std Step Tol= 0.01
Critical Tol= 0.01
Num of Std Step Trials= 20
Max Error Tol= 0.3
Flow Tol Ratio= 0.001
Split Flow NTrial= 30
Split Flow Tol= 0.02
Split Flow Ratio= 0.02
Log Output Level= 0
Friction Slope Method= 1
Unsteady Friction Slope Method= 2
Unsteady Bridges Friction Slope Method= 1
Parabolic Critical Depth
Global Vel Dist= 1 , 1 , 1
Global Log Level= 0
CheckData=True
Encroach Param=-1 ,5,5, 2
Encroach River=Waccamaw River
Encroach Reach=Reach-1
Encroach Node=542289
       1    3310    8720
Encroach Node=541448
       1 3172.08    8400
Encroach Node=540044
       1 4049.62 9658.66
Encroach Node=538587
       1 3292.09   10000
Encroach Node=537591
       1    73.6 9374.82
Encroach Node=523658
       1  4753.814819.66
Encroach Node=523161
       1  4403.814386.96
Encroach Node=522472
       1  4453.814346.31
Encroach Node=520464
       1    4155   14160
Encroach Node=519142
       1  4453.814505.81
Encroach Node=517257
       1  4453.8   15000
Encroach Node=514995
       1  4956.916153.94
Encroach Node=509361
       1    460013103.67
Encroach Node=508695
       1  4349.912252.24
Encroach Node=505446
       1  4563.912223.22
Encroach Node=504592
       1 3379.66 11143.9
Encroach Node=496302
       1  1031.712936.03
Encroach Node=486095
       1    441516879.33
Encroach Node=485021
       1  4919.8   17110
Encroach Node=484901
       1  4919.8   17000
Encroach Node=484461
       1  4919.8   13500
Encroach Node=480685
       1    3500   11250
Encroach Node=480160
       1 3516.4410229.89
Encroach Node=477958
       1 3268.53 9846.98
Encroach Node=477202
       1 3729.5510186.38
Encroach Node=476142
       1 3859.24 10141.8
Encroach Node=475142
       1    440010461.49
Encroach Node=473142
       1 3408.55  8666.2
Encroach Node=472142
       1 3214.38 8002.23
Encroach Node=465553
       1 4274.7210364.16
Encroach Node=465030
       1    430010468.29
Encroach Node=464142
       1 3822.41 9994.35
Encroach Node=463142
       1 3450.03  9527.1
Encroach Node=462295
       1 3206.12 8863.19
Encroach Node=460830
       1  2639.4 7352.66
Encroach Node=459904
       1 2680.21 7206.48
Encroach Node=457142
       1 3980.24 7997.78
Encroach Node=456251
       1 3523.83 7328.87
Encroach Node=454910
       1 3703.49 7544.36
Encroach Node=454341
       1  3849.7 7793.54
Encroach Node=453142
       1  3245.7 8162.53
Encroach Node=452238
       1 2381.25 7729.69
Encroach Node=451659
       1  1403.5 7429.96
Encroach Node=448982
       1  492.64 6432.67
Encroach Node=446715
       1 -695.94  5283.4
Encroach Node=445771
       1  -943.9  5063.4
Encroach Node=444924
       1 -999.24  5065.8
Encroach Node=444142
       1-1015.79  5065.8
Encroach Node=443368
       1-1189.12  5065.8
Encroach Node=442206
       1    -900    5061
Encroach Node=436496
       1 1186.57 7493.71
Encroach Node=434142
       1    1100 8181.97
Encroach Node=432894
       1  371.64 7655.07
Encroach Node=429744
       1 1923.98 9400.01
Encroach Node=427363
       1  2111.3  9674.4
Encroach Node=426569
       1 1866.81 9201.15
Encroach Node=425142
       1 2729.3510153.52
Encroach Node=423637
       1 1450.96 8675.15
Encroach Node=422285
       1 1268.94 8265.77
Encroach Node=417103
       1  332.28 7704.45
Encroach Node=415875
       1 1084.25  8608.4
Encroach Node=411190
       1 -528.15 7893.65
Encroach Node=405901
       1-1711.13  5045.2
Encroach Node=405128
       1-1163.89  5119.5
Encroach Node=404201
       1-1391.37  5769.5
Encroach Node=402377
       1   -2960    5300
Encroach Node=401279
       1-2714.55  5740.6
Encroach Node=399806
       1   -3081  5364.6
Encroach Node=399274
       1-1993.55  5185.5
Encroach Node=399143
       1 -2006.5    5173
Encroach Node=398554
       1-2600.34  5170.6
Encroach Node=397832
       1-2853.62  5164.6
Encroach Node=397142
       1-3400.23  5164.6
Encroach Node=396202
       1-4100.13    5186
Encroach Node=394736
       1-3962.99  5117.3
Encroach Node=393977
       1-4010.18  5117.3
Encroach Node=393085
       1-3537.89    5089
Encroach Node=392168
       1-3132.38  5117.3
Encroach Node=390540
       1-2659.43  5093.7
Encroach Node=389005
       1   -2400  5243.7
Encroach Node=388147
       1   -2250  5351.9
Encroach Node=387108
       1 -2277.9  5726.2
Encroach Node=386377
       1   -2300 6036.15
Encroach Node=385245
       1   -2200 6912.03
Encroach Node=383731
       1-1266.32 8370.58
Encroach Node=382983
       1-1460.96 8687.43
Encroach Node=380461
       1  208.4310549.15
Encroach Node=377142
       1-1827.23    9200
Encroach Node=376142
       1-2476.83    8940
Encroach Node=375129
       1-2725.41    8700
Encroach Node=373936
       1-3287.63  7705.4
Encroach Node=371911
       1-4028.87    6840
Encroach Node=371142
       1-4150.26 6843.97
Encroach Node=370142
       1-4870.34  6236.6
Encroach Node=369197
       1   -5288 5777.39
Encroach Node=362319
       1-1415.67    9200
Encroach Node=359656
       1-1579.19    9100
Encroach Node=357688
       1     70010861.06
Encroach Node=356737
       1     200 10371.8
Encroach Node=355768
       1  954.0811365.67
Encroach Node=355142
       1     940 11560.1
Encroach Node=354142
       1    1100 11877.2
Encroach Node=353344
       1    1255   11830
BEGIN DESCRIPTION:
Floodway Run
END DESCRIPTION:
Computation Interval=1HOUR
Output Interval=1HOUR
Run HTab= 0
Run UNet= 0
Run PostProcess= 0
Run WQNet= 0
UNET Theta= 1
UNET Theta Warmup= 1
UNET ZTol= 0.02
UNET ZSATol= 0.05
UNET MxIter= 20
UNET MaxInSteps= 0
UNET DtIC= 0
UNET DtMin= 0
UNET MaxCRTS= 20
UNET WFStab= 2
UNET SFStab= 1
UNET WFX= 1
UNET SFX= 1
UNET DSS MLevel= 4
UNET DZMax Abort= 100
UNET Convert EG Bridges= 0
UNET Use Existing IB Tables=-1
UNET Froude Reduction=False
UNET Froude Limit= 1
UNET Froude Power= 10
UNET Time Slicing=0,0, 5
Instantaneous Interval=1HOUR
Write IC File= 0
Echo Input=False
Echo Output=False
Write Detailed= 0
Detailed Automatic Start=False, 10
WQ ULTIMATE=-1
WQ Max Comp Step=1HOUR
WQ Output Interval=15MIN
WQ Output Selected Increments= 0
WQ Output face flow=0
WQ Output face velocity=0
WQ Output face area=0
WQ Output face dispersion=0
WQ Output cell volume=0
WQ Output cell surface area=0
WQ Output cell continuity=0
WQ Output face conc=0
WQ Output face dconc_dx=0
WQ Output face courant=0
WQ Output face peclet=0
WQ Output face adv mass=0
WQ Output face disp mass=0
WQ Output cell mass=0
WQ Output cell source sink temp=0
WQ Output cell source sink nsm=0
WQ Output MaxMinRange=-1
WQ Daily Max Min Mean=-1
WQ Daily Range=0
WQ Daily Time=0
WQ Create Restart=0
WQ Fixed Restart=0
WQ System Summary=False
Sorting and Armoring Iterations= 10
XS Update Threshold= 0.02
Hydraulics Update Threshold= 0.02
Energy Slope Method= 1
Volume Change Method= 0
XS Weighting Method= 0
Number of US Weighted Cross Sections= 1
Number of DS Weighted Cross Sections= 1
Upstream XS Weight=0.25
Main XS Weight=0.5
Downstream XS Weight=0.25
Number of DS XS's Weighted with US Boundary= 1
Upstream Boundary Weight= 1
Weight of XSs Associated with US Boundary= 0
Number of US XS's Weighted with DS Boundary= 1
Downstream Boundary Weight= 0.5
Weight of XSs Associated with DS Boundary= 0.5
Sediment Output Level= 4
Mass or Volume Output= 0
Output Increment Type= 1
Profile and TS Output Increment= 10
XS Output Flag= 0
XS Output Increment= 10
Disregard all LS=0
Disregard all Conn=0
Disregard all Breaches=0
Disregard all Pumps=0

--- Waccamaw River.f01 (steady flow) ---

Flow Title=Multiple
Number of Profiles=8
Profile Names=10-year,50-year,100-year,500-year,Fut35,Fut10,Fut20,25-year
River Rch & RM= Waccamaw River,Reach-1,542289
    7832   12816   15290   21224   39413   25169   32258   10507
River Rch & RM= Waccamaw River,Reach-1,537591
    9025   15130   18165   25991   46911   29957   38394   12336
River Rch & RM= Waccamaw River,Reach-1,486095
    9128   15274   18329   26177   47263   30182   38682   12459
River Rch & RM= Waccamaw River,Reach-1,453142
    9873   16312   19504   27483   49762   31778   40728   13351
River Rch & RM= Waccamaw River,Reach-1,405901
   11604   18230   21377   28925   56192   35844   45990   15239
River Rch & RM= Waccamaw River,Reach-1,362319
   11880   18633   21827   29554   57671   36828   47201   15599
Boundary for River Rch & Prof#=Waccamaw River,Reach-1,1
Up Type=0
Dn Type=1
Dn Known WS=22.81
Boundary for River Rch & Prof#=Waccamaw River,Reach-1,2
Up Type=0
Dn Type=1
Dn Known WS=24.17
Boundary for River Rch & Prof#=Waccamaw River,Reach-1,3
Up Type=0
Dn Type=1
Dn Known WS=24.73
Boundary for River Rch & Prof#=Waccamaw River,Reach-1,4
Up Type=0
Dn Type=1
Dn Known WS=25.97
Boundary for River Rch & Prof#=Waccamaw River,Reach-1,5
Up Type=0
Dn Type=3
Dn Slope=0.000025
Boundary for River Rch & Prof#=Waccamaw River,Reach-1,6
Up Type=0
Dn Type=3
Dn Slope=0.000025
Boundary for River Rch & Prof#=Waccamaw River,Reach-1,7
Up Type=0
Dn Type=3
Dn Slope=0.000025
Boundary for River Rch & Prof#=Waccamaw River,Reach-1,8
Up Type=0
Dn Type=3
Dn Slope=0.000025

--- Waccamaw River.f02 (steady flow) ---

Flow Title=Floodway
Number of Profiles=2
Profile Names=100-year,100-FW
River Rch & RM= Waccamaw River,Reach-1,542289
   15290   15290
River Rch & RM= Waccamaw River,Reach-1,537591
   18165   18165
River Rch & RM= Waccamaw River,Reach-1,486095
   18329   18329
River Rch & RM= Waccamaw River,Reach-1,453142
   19504   19504
River Rch & RM= Waccamaw River,Reach-1,405901
   21377   21377
River Rch & RM= Waccamaw River,Reach-1,362319
   21827   21827
Boundary for River Rch & Prof#=Waccamaw River,Reach-1,1
Up Type=0
Dn Type=1
Dn Known WS=24.73
Boundary for River Rch & Prof#=Waccamaw River,Reach-1,2
Up Type=0
Dn Type=1
Dn Known WS=25.53

--- Waccamaw River.g01 (geometry) ---

Geom Title=Existing Conditions
Program Version=4.00

River Reach=Waccamaw River  ,Reach-1
Reach XY= 30
      2144089.46       186199.95      2139677.87       179595.98
      2131966.39       173693.29      2132590.61        164529.3
      2130520.35       159177.58      2131951.04       156676.39
      2126291.58       151160.06       2129862.4       149162.86
      2132044.61       143693.96      2137247.52       142846.57
      2139456.72       137697.26      2134677.21       133798.83
      2136517.49       131898.65      2134966.27       129057.07
      2138057.42       127679.47      2133166.79       124798.39
      2135157.24       117591.79       2134212.8       113951.17
      2132483.41       111056.05      2129228.42       111633.46
       2126517.4       108961.57       2127902.9         106301.
      2126027.26       102656.07      2123643.58       101052.77
      2120952.61       102142.18      2108952.61        95002.42
      2113979.52        81484.19      2106664.42        78700.34
       2108588.9        75228.12      2106068.86        70800.44

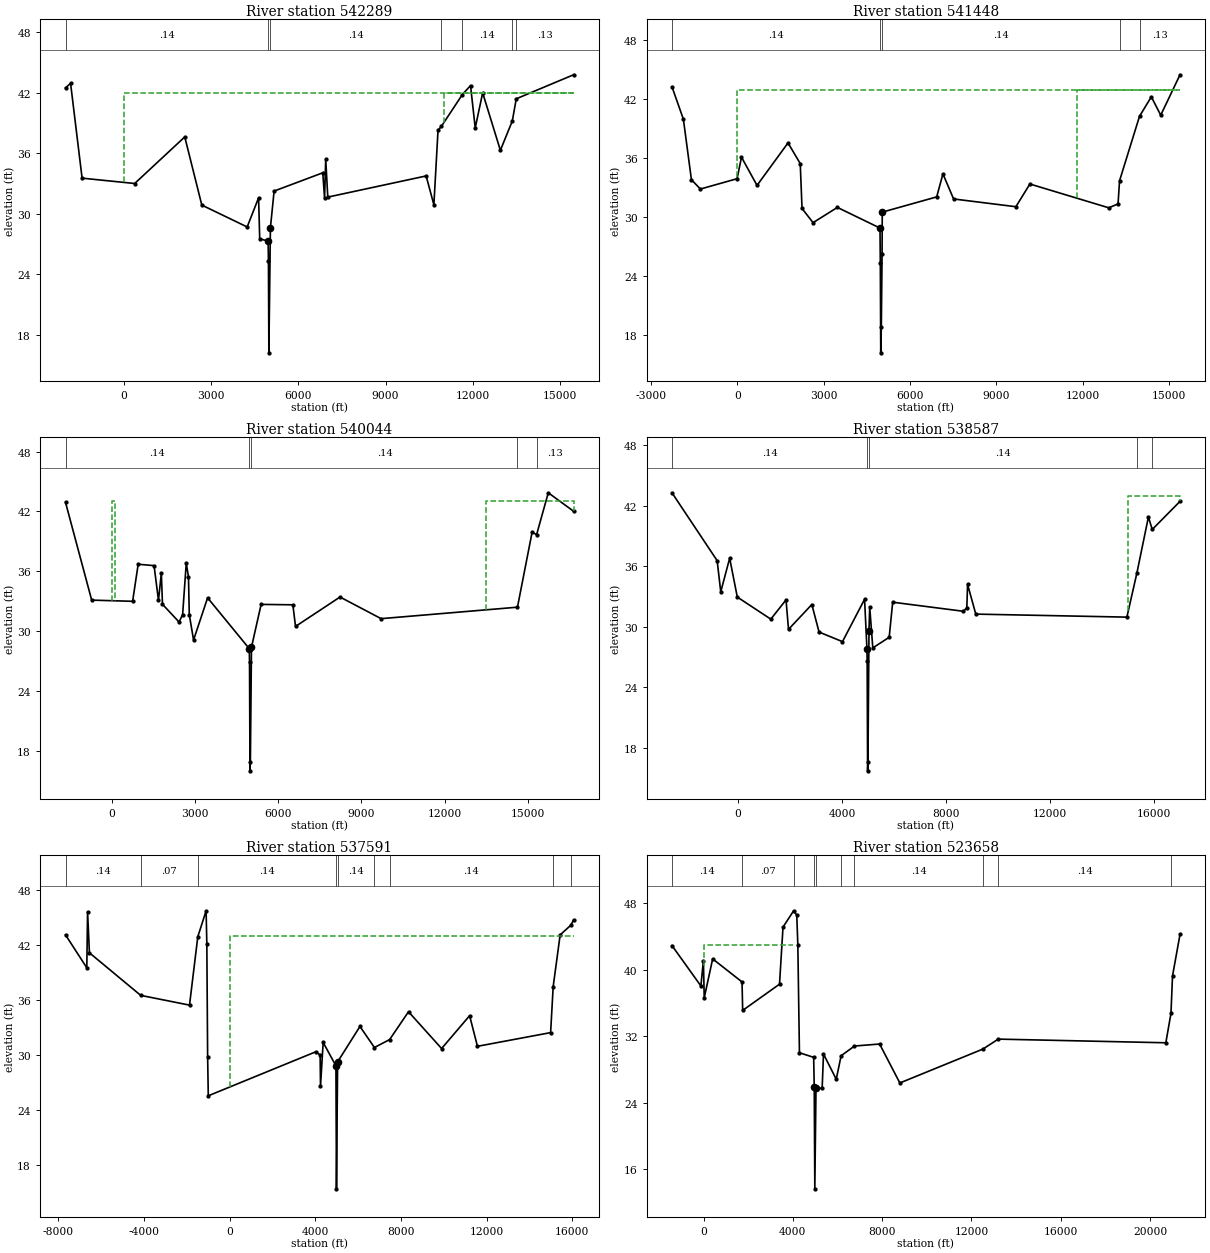
Type RM Length L Ch R = 1 ,542289  ,262,841,1237
BEGIN DESCRIPTION:
Waccamaw River 173.0
END DESCRIPTION:
XS GIS Cut Line= 4
      2134555.94       151534.43      2130269.32       146331.03
      2121795.16       147421.27      2119614.54       147701.82
#Sta/Elev= 30
   -2014   42.49 -1839.5   42.94 -1443.1   33.54   366.6   33.01  2090.1   37.63
    2677   30.87    4238    28.7  4630.8   31.59  4669.9   27.52  4958.8   27.31
  4970.2   25.33  4984.7   16.22  5037.8   28.62    5165   32.26  6839.8   34.07
    6902   31.54  6940.7   35.45  7012.1   31.66 10397.1   33.76 10663.7    30.9
 10806.2   38.29   10923   38.68 11643.5   41.83 11924.6   42.72 12086.6   38.52
 12342.4      42 12952.3    36.3 13362.6   39.21   13499   41.41 15470.3   43.79
#Mann= 7 ,-1 , 0
   -2014     .14       0  4958.8     .04       0  5037.8     .14       0
   10923     .07       0 11643.5     .14       0 13362.6     .07       0
   13499     .13       0
#XS Ineff= 2 , 0
       0    -300      42   11000       0      42
Permanent Ineff=
       F       F
Bank Sta=4958.8,5037.8
XS Rating Curve= 0 ,0
Exp/Cntr=0.3,0.1

Type RM Length L Ch R = 1 ,541448  ,694,1404,338
BEGIN DESCRIPTION:
Waccamaw River 172.0
END DESCRIPTION:
XS GIS Cut Line= 4
      2134679.88       151460.16      2129971.98       145414.23
      2121250.04       145414.23      2120006.76       145704.55
#Sta/Elev= 30
 -2272.8   43.28 -1876.1   39.98 -1596.6   33.83 -1284.5   32.88    -9.9   33.93
   144.1   36.12   683.9   33.25  1761.2   37.57  2186.1   35.47  2248.9    30.9
    2632   29.46  3477.7   31.01  4958.8   28.91  4970.2   25.33  4984.7   16.22
    5005   18.87  5030.8   26.28  5037.8   30.53  6929.8   32.08  7146.7   34.42
  7517.1   31.87  9682.1   31.08 10169.7   33.39 12912.9   30.97 13234.4   31.37
 13286.6   33.72   13981   40.28 14391.3   42.26 14718.1   40.39 15388.6    44.5
#Mann= 5 ,-1 , 0
 -2272.8     .14       0  4958.8     .04       0  5037.8     .14       0
 13286.6     .07       0   13981     .13       0
#XS Ineff= 2 , 0
       0    -500      43   11800       0      43
Permanent Ineff=
       F       F
Bank Sta=4958.8,5037.8
XS Rating Curve= 0 ,0
Exp/Cntr=0.3,0.1

Type RM Length L Ch R = 1 ,540044  ,1234,1457,398
BEGIN DESCRIPTION:
Waccamaw River 171.0
END DESCRIPTION:
XS GIS Cut Line= 4
      2134729.39       151360.99      2131062.23       145042.56
      2121373.93       145166.45      2120052.35       145183.35
#Sta/Elev= 30
 -1666.7    42.9  -722.8   33.09   752.8   32.97   953.5   36.69  1526.3   36.55
  1684.9   33.07  1788.4   35.79  1829.5   32.67  2428.1   30.89  2555.7   31.64
  2686.4   36.79  2766.4   35.45  2795.9   31.64    2950   29.09  3456.3   33.32
  4958.8   28.22  4967.5   26.86  4984.7   15.96  4998.3   16.84  5037.8   28.36
  5385.6   32.66  6530.2   32.62  6626.3   30.45  8230.3    33.4  9711.5   31.23
 14627.5   32.38 15155.2    39.9 15317.9   39.66 15738.3   43.86 16649.6   42.01
#Mann= 5 ,-1 , 0
 -1666.7     .14       0  4958.8     .04       0  5037.8     .14       0
 14627.5     .07       0 15317.9     .13       0
#XS Ineff= 2 , 0
       0     100      43   13500       0      43
Permanent Ineff=
       F       F
Bank Sta=4958.8,5037.8
XS Rating Curve= 0 ,0
Exp/Cntr=0.3,0.1

Type RM Length L Ch R = 1 ,538587  ,4975,996,861
BEGIN DESCRIPTION:
Waccamaw River 169.0
END DESCRIPTION:
XS GIS Cut Line= 5
      2134828.52       151435.34      2134407.29       148957.52
      2132474.59       144522.22      2121473.05       144943.45
      2120320.26       144987.58
#Sta/Elev= 30
 -2529.9   43.28  -794.2   36.55  -656.3   33.46  -313.6   36.79   -20.7   32.94
  1267.1   30.75    1851   32.66  1946.4   29.74  2842.6    32.2  3120.1   29.47
  4019.5   28.52  4868.3   32.72  4958.8   27.83  4967.5   26.61  4984.7   15.71
  4998.3   16.59  5037.8    29.6  5065.7   31.94  5184.2    27.9  5813.4   28.95
  5948.1   32.43  8665.9   31.53  8796.1   31.89  8824.7    34.2  9139.8   31.25
 14943.9   30.95 15328.9   35.33 15771.2   40.88 15917.7   39.64 16984.8   42.43
#Mann= 5 ,-1 , 0
 -2529.9     .14       0  4958.8     .04       0  5037.8     .14       0
 15328.9     .07       0 15917.7     .13       0
#XS Ineff= 2 , 0
       0                   15000       0      43
Permanent Ineff=
       F       F
Bank Sta=4958.8,5037.8
XS Rating Curve= 0 ,0
Exp/Cntr=0.3,0.1

Type RM Length L Ch R = 1 ,537591  ,1665,13933,1767
BEGIN DESCRIPTION:
Waccamaw River 168.0
END DESCRIPTION:
XS GIS Cut Line= 6
      2143632.48        139981.3       2140313.7       142476.27
      2138022.97       143156.67      2133465.72       143729.31
      2121473.05       144472.66      2120896.99       144508.37
#Sta/Elev= 30
 -7670.9   43.08 -6676.4    39.5 -6640.3    45.6 -6554.5   41.13 -4158.9    36.5
 -1879.2   35.44 -1492.4   42.88 -1103.8    45.7 -1070.2   42.05 -1033.1   29.78
 -1002.3   25.58  4023.8   30.37  4221.4   30.02  4238.3   26.63  4363.1   31.38
  4958.8   28.84  4984.7   15.46  5037.8   29.27  6081.1   33.12  6756.5   30.83
  7465.5   31.69    8349   34.72  9894.2   30.72 11202.9   34.29 11568.1   30.96
 14985.5   32.45 15105.7   37.46 15430.8   43.08   15931   44.13 16056.7    44.7
#Mann= 9 ,-1 , 0
 -7670.9     .14       0 -4158.9     .07       0 -1492.4     .14       0
  4958.8     .04       0  5037.8     .14       0  6756.5     .08       0
  7465.5     .14       0 15105.7     .07       0   15931     .13       0
#XS Ineff= 2 , 0
       0   -1400      43               0
Permanent Ineff=
       F       F
Bank Sta=4958.8,5037.8
XS Rating Curve= 0 ,0
Exp/Cntr=0.3,0.1

Type RM Length L Ch R = 1 ,523658  ,186,497,537
BEGIN DESCRIPTION:
Waccamaw River 158.0
END DESCRIPTION:
XS GIS Cut Line= 4
      2143526.52       139922.48      2138697.35       142250.35
      2137876.25       142093.95      2121448.29       144175.32
#Sta/Elev= 30
 -1413.5    42.9  -118.5   38.05    -5.1   41.09      31   36.61   408.7    41.3
  1724.6   38.53  1753.4   35.11  3403.3   38.26  3560.5   45.12  4036.4   47.08
  4176.4   46.56  4224.5   42.93    4296   30.02  4932.8   29.47  4958.8    25.9
  4984.7   13.67  5037.8   25.84  5312.9   25.73  5373.4   29.87  5944.6   26.84
  6162.7   29.66  6761.2   30.83  7886.7   31.07  8793.3   26.39   12511   30.46
 13201.4   31.66 20707.5   31.22 20937.2   34.75 21006.9   39.25 21342.6   44.24
#Mann= 10 ,-1 , 0
 -1413.5     .14       0  1724.6     .07       0  4036.4     .14       0
  4958.8     .04       0  5037.8     .14       0  6162.7     .08       0
  6761.2     .14       0   12511     .08       0 13201.4     .14       0
 20937.2     .07       0
#XS Ineff= 2 , 0
       0    4000      43               0
Permanent Ineff=
       F       F
Bank Sta=4958.8,5037.8
XS Rating Curve= 0 ,0
Exp/Cntr=0.3,0.1

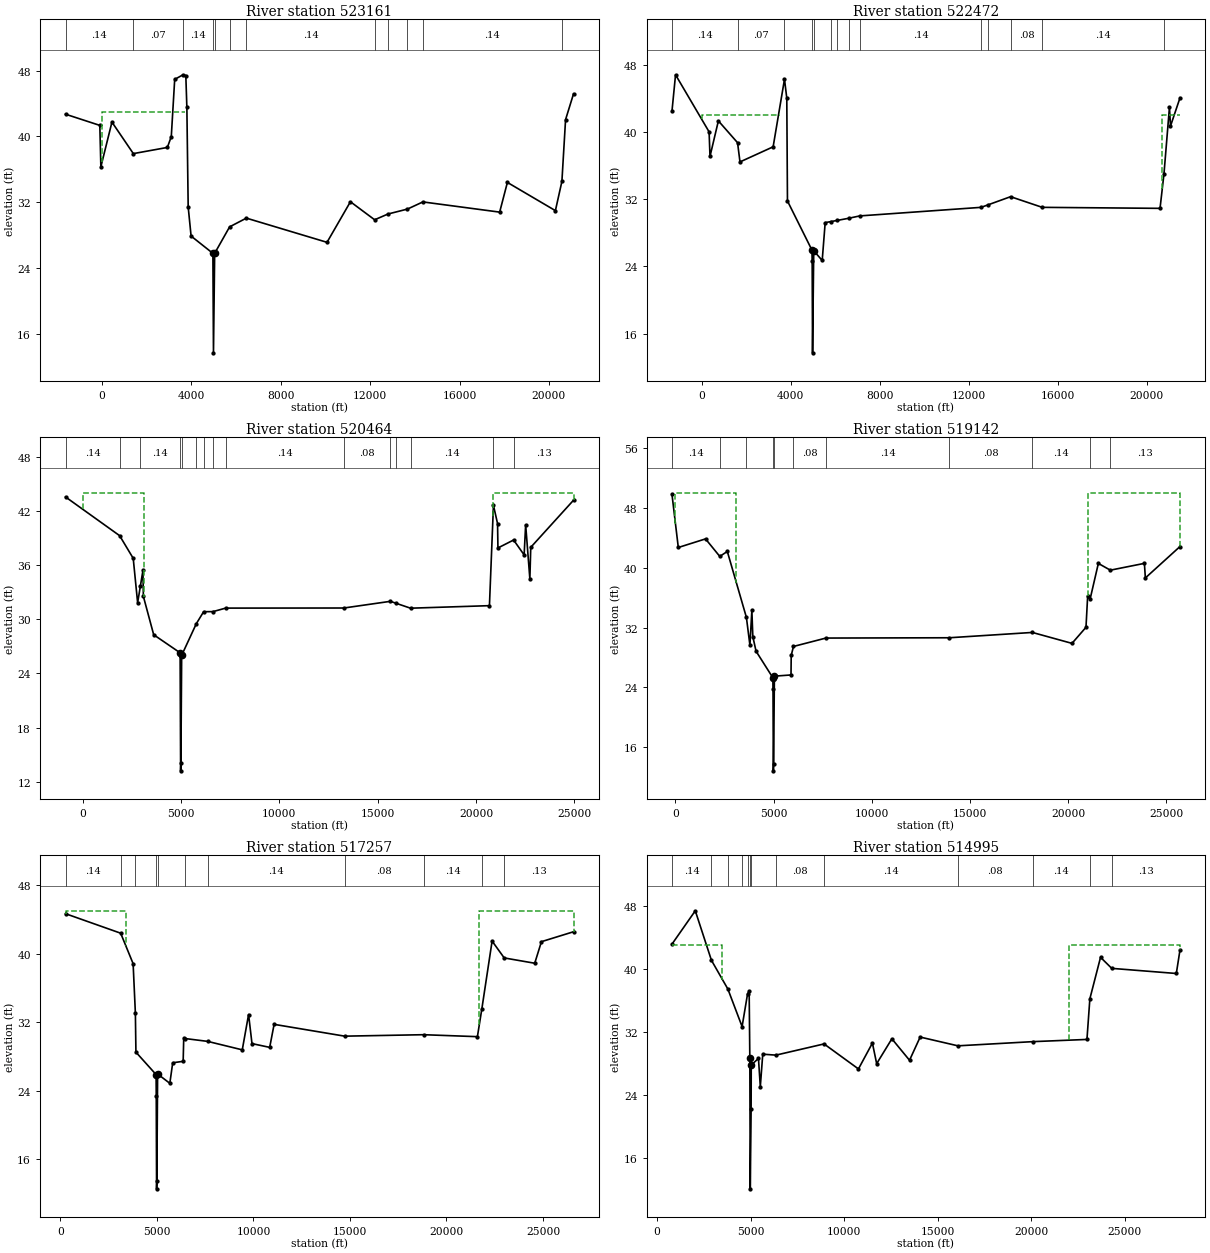
Type RM Length L Ch R = 1 ,523161  ,422,689,1027
BEGIN DESCRIPTION:
Waccamaw River 157.0
END DESCRIPTION:
XS GIS Cut Line= 5
      2143444.14       139875.41      2138804.67        142058.3
      2137727.58       141895.72      2122027.31       143909.19
      2121339.62        144032.8
#Sta/Elev= 30
 -1639.6   42.71  -103.6   41.35   -56.5   36.31   439.2   41.75  1397.1   37.92
  2920.5   38.67  3096.1   39.99  3248.5   46.94  3621.2    47.5  3746.7   47.41
  3793.4   43.54  3852.6   31.44  3982.7    27.9  4958.8    25.8  4984.7   13.71
  5037.8    25.8  5707.2   29.02  6457.4   30.08 10067.6   27.14 11115.5   32.07
 12199.6   29.88 12796.9   30.58 13668.5   31.18 14359.4   32.05 17796.9   30.81
 18142.6   34.42 20292.1   30.99 20583.2   34.54 20747.3   42.05 21104.6   45.19
#Mann= 12 ,-1 , 0
 -1639.6     .14       0  1397.1     .07       0  3621.2     .14       0
  4958.8     .04       0  5037.8     .14       0  5707.2     .08       0
  6457.4     .14       0 12199.6     .08       0 12796.9     .14       0
 13668.5     .08       0 14359.4     .14       0 20583.2     .07       0
#XS Ineff= 2 , 0
       0    3700      43               0
Permanent Ineff=
       F       F
Bank Sta=4958.8,5037.8
XS Rating Curve= 0 ,0
Exp/Cntr=0.3,0.1

Type RM Length L Ch R = 1 ,522472  ,1225,2008,1361
BEGIN DESCRIPTION:
Waccamaw River 156.0
END DESCRIPTION:
XS GIS Cut Line= 5
      2143373.59       139828.31      2139239.48       141718.65
      2137380.68       141400.16       2121522.6        143630.2
      2121271.86       143919.85
#Sta/Elev= 30
 -1332.3   42.49 -1171.9   46.83     336   40.03   376.3   37.11   752.9   41.34
  1615.1   38.74  1723.5   36.45  3213.5   38.25    3724    46.3    3827   44.04
    3857    31.8  4958.8   25.94  4967.5   24.61  4984.7   13.71  5037.8   25.87
  5418.4   24.71  5552.2   29.22  5799.6   29.34  6088.2   29.48  6612.6   29.74
  7108.3   30.02 12558.1   31.04 12873.4   31.34 13883.3   32.31   15305   31.04
 20598.7   30.92 20775.3   35.01   21022   42.95 21068.7   40.72 21496.6   44.09
#Mann= 14 ,-1 , 0
 -1332.3     .14       0  1615.1     .07       0    3724     .14       0
  4958.8     .04       0  5037.8     .14       0  5799.6     .08       0
  6088.2     .14       0  6612.6     .08       0  7108.3     .14       0
 12558.1     .08       0 12873.4     .14       0 13883.3     .08       0
   15305     .14       0 20775.3     .07       0
#XS Ineff= 2 , 0
       0    3500      42   20700       0      42
Permanent Ineff=
       F       F
Bank Sta=4958.8,5037.8
XS Rating Curve= 0 ,0
Exp/Cntr=0.3,0.1

Type RM Length L Ch R = 1 ,520464  ,808,1322,622
BEGIN DESCRIPTION:
Waccamaw River 155.0
END DESCRIPTION:
XS GIS Cut Line= 5
      2143279.44       139769.48      2138273.24       140385.73
      2136756.53       140450.27      2121547.38       143456.75
      2117905.74       144360.37
#Sta/Elev= 30
  -865.4   43.54    1885   39.25  2575.7   36.74  2799.9   31.82  2944.4   33.73
  3069.3    35.4  3092.4   32.52  3615.9   28.28  4958.8   26.28  4984.7   13.21
  4998.3   14.09  5037.8      26  5783.3   29.51  6153.9   30.83  6626.1   30.84
  7275.7   31.23 13278.7   31.24 15644.3   31.98 15939.1   31.76 16667.6   31.22
 20677.8    31.5 20881.6   42.61 21090.3   40.59   21110   37.89 21905.3   38.77
 22441.4   37.12 22518.3   40.46 22732.4   34.46 22777.8   37.96 24952.2   43.18
#Mann= 15 ,-1 , 0
  -865.4     .14       0    1885     .07       0  2944.4     .14       0
  4958.8     .04       0  5037.8     .14       0  5783.3     .08       0
  6153.9     .14       0  6626.1     .08       0  7275.7     .14       0
 13278.7     .08       0 15644.3     .14       0 15939.1     .08       0
 16667.6     .14       0 20881.6     .07       0 21905.3     .13       0
#XS Ineff= 2 , 0
       0    3100      44 20860.8       0      44
Permanent Ineff=
       F       F
Bank Sta=4958.8,5037.8
XS Rating Curve= 0 ,0
Exp/Cntr=0.3,0.1

Type RM Length L Ch R = 1 ,519142  ,1442,1885,806
BEGIN DESCRIPTION:
Waccamaw River 154.0
END DESCRIPTION:
XS GIS Cut Line= 5
      2143244.08       139698.87      2139548.19       139591.13
      2138070.11       139649.78      2121844.72       142812.52
      2117950.93       144270.01
#Sta/Elev= 30
  -176.7   49.79   145.4   42.69  1531.5   43.84  2256.7    41.5  2641.3   42.16
  3612.8   33.35  3791.6   29.63  3890.6   34.29    3940   30.78  4104.6   28.83
  4958.8   25.29  4967.5   23.75  4984.7   12.85  4998.3   13.73  5037.8    25.5
  5883.8   25.66    5894   28.27    6010   29.47  7661.8   30.59 13940.7   30.63
 18171.2   31.34   20189   29.88 20901.4   32.03 20986.3   36.19 21109.5   35.78
 21530.8   40.56 22141.9   39.66 23875.4   40.57 23924.1   38.62 25688.4   42.82
#Mann= 11 ,-1 , 0
  -176.7     .14       0  2256.7     .07       0  3612.8     .14       0
  4958.8     .04       0  5037.8     .14       0    6010     .08       0
  7661.8     .14       0 13940.7     .08       0 18171.2     .14       0
 21109.5     .07       0 22141.9     .13       0
#XS Ineff= 2 , 0
       0    3100      50   21000       0      50
Permanent Ineff=
       F       F
Bank Sta=4958.8,5037.8
XS Rating Curve= 0 ,0
Exp/Cntr=0.3,0.1

Type RM Length L Ch R = 1 ,517257  ,1790,2262,139
BEGIN DESCRIPTION:
Waccamaw River 152.0
END DESCRIPTION:
XS GIS Cut Line= 5
      2143185.27        139616.5       2139772.7       138328.88
       2138531.4        138352.7      2121993.39        142713.4
      2117939.65       144213.52
#Sta/Elev= 30
   267.3   44.66  3124.6   42.38  3769.4   38.82  3886.7   33.03  3914.7   28.48
  4958.8   25.86  4967.5   23.41  4984.7   12.51  4998.3   13.39  5037.8   25.93
  5670.5   24.84  5820.1   27.24  6361.4   27.41  6390.5   30.09  6468.3   30.07
  7630.2   29.74  9423.1   28.75  9749.9   32.88  9926.4   29.48 10843.1   29.04
   11072   31.73 14726.8   30.35 18813.4   30.52 21602.2   30.29   21835   33.58
 22363.2   41.46 22990.8   39.49 24571.5   38.87 24918.3   41.39 26581.9   42.55
#Mann= 11 ,-1 , 0
   267.3     .14       0  3124.6     .07       0  3886.7     .14       0
  4958.8     .04       0  5037.8     .14       0  6468.3     .08       0
  7630.2     .14       0 14726.8     .08       0 18813.4     .14       0
   21835     .07       0 22990.8     .13       0
#XS Ineff= 2 , 0
       0    3400      45   21700       0      45
Permanent Ineff=
       F       F
Bank Sta=4958.8,5037.8
XS Rating Curve= 0 ,0
Exp/Cntr=0.3,0.1

Type RM Length L Ch R = 1 ,514995  ,3821,5634,661
BEGIN DESCRIPTION:
Waccamaw River 149.0
END DESCRIPTION:
XS GIS Cut Line= 6
      2143726.62        136874.4      2141188.96       136459.27
      2139369.65       136851.68      2134407.29       139294.01
      2122067.72       142614.29      2117942.45       144154.66
#Sta/Elev= 30
   802.2   43.17    2048    47.4  2911.1   41.12  3788.8   37.48  4548.7   32.72
    4839   36.84  4926.4   37.22  4961.9   28.72  4984.7   12.15  5030.8   22.21
  5037.8   27.85  5423.6   28.68  5522.3    25.1  5652.8   29.22  6355.7    29.1
  8928.1   30.52 10765.6   27.35 11511.8   30.63 11739.2   28.02 12551.9   31.17
   13495   28.45 14062.9   31.39 16080.5   30.28 20081.4   30.81 22974.8   31.09
 23130.8   36.25 23701.2    41.5 24299.6    40.1   27750   39.45 27947.5   42.45
#Mann= 13 ,-1 , 0
   802.2     .14       0  2911.1     .07       0  3788.8     .14       0
  4548.7     .07       0    4839     .14       0  4961.9     .04       0
  5037.8     .14       0  6355.7     .08       0  8928.1     .14       0
 16080.5     .08       0 20081.4     .14       0 23130.8     .07       0
 24299.6     .13       0
#XS Ineff= 2 , 0
       0    3500      43   22000       0      43
Permanent Ineff=
       F       F
Bank Sta=4961.9,5037.8
XS Rating Curve= 0 ,0
Exp/Cntr=0.3,0.1

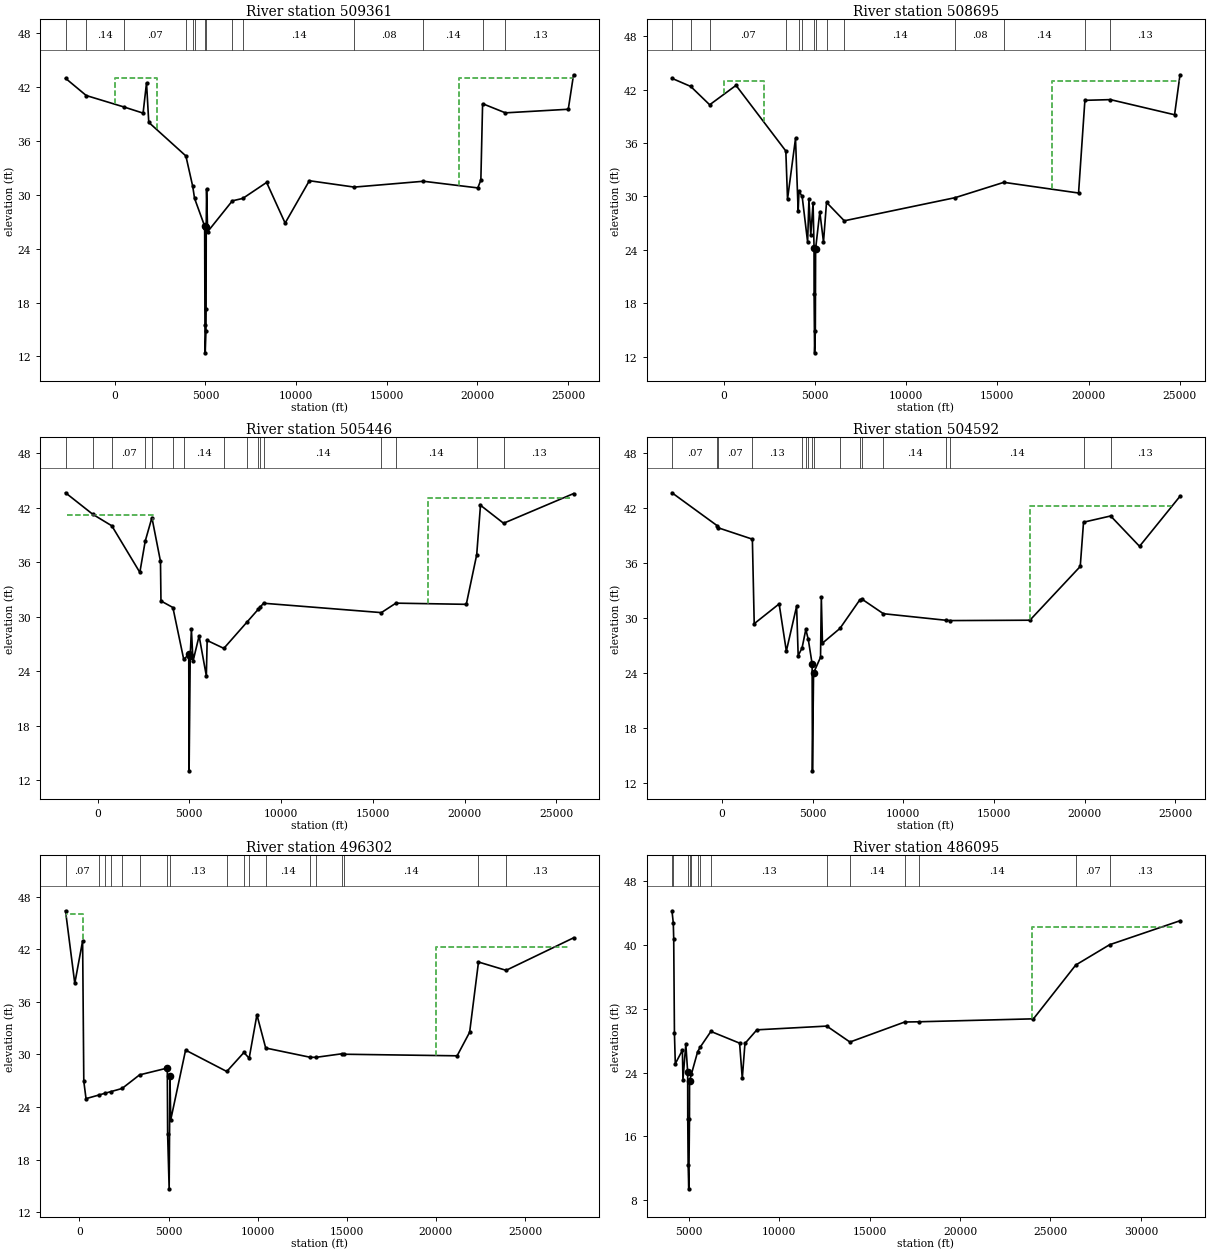
Type RM Length L Ch R = 1 ,509361  ,673,666,1067
BEGIN DESCRIPTION:
Waccamaw River 145.0
END DESCRIPTION:
XS GIS Cut Line= 6
      2142443.82       131613.81       2138002.5        135455.7
      2132895.82       139046.22      2122387.44       142451.04
      2122267.21       142541.61       2117844.1       144171.05
#Sta/Elev= 30
 -2721.2   42.98   -1578   41.06     493   39.79  1558.4    39.1  1747.9   42.47
  1871.5   38.07  3918.8   34.33  4297.7   30.93    4397   29.61  4954.9   26.51
  4971.4   15.53  4985.3    12.4  5026.3   14.81  5034.5   17.31  5041.6   26.41
    5061   30.63    5119   25.89  6482.6   29.33  7058.5    29.6  8373.1   31.38
  9393.8   26.85 10729.8   31.57   13209   30.86 17023.6   31.51 20021.9   30.77
 20191.1   31.64 20287.4   40.15 21545.7   39.13 25013.4   39.53 25304.4   43.37
#Mann= 14 ,-1 , 0
 -2721.2     .07       0   -1578     .14       0     493     .07       0
  3918.8     .14       0  4297.7     .07       0    4397     .14       0
  4954.9     .04       0  5041.6     .14       0  6482.6     .08       0
  7058.5     .14       0   13209     .08       0 17023.6     .14       0
 20287.4     .07       0 21545.7     .13       0
#XS Ineff= 2 , 0
       0    2300      43   19000       0      43
Permanent Ineff=
       F       F
Bank Sta=4954.9,5041.6
XS Rating Curve= 0 ,0
Exp/Cntr=0.3,0.1

Type RM Length L Ch R = 1 ,508695  ,1607,3249,1298
BEGIN DESCRIPTION:
Waccamaw River 143.0
END DESCRIPTION:
XS GIS Cut Line= 6
      2142373.22       131543.19      2138082.01       134884.85
      2131235.68       138971.89      2122487.96       142315.89
      2122254.52       142530.74      2117792.55       144169.32
#Sta/Elev= 30
 -2832.1   43.27 -1804.9   42.36  -765.5    40.3   678.8   42.48  3408.6   35.11
    3502   29.71  3939.6   36.52  4084.5   28.34  4131.2    30.6  4304.4      30
  4603.6   24.88  4674.8   29.69  4775.7   25.66  4902.7   29.25  4954.9   24.26
  4958.5   19.06  4985.3   12.44  5026.3   14.85  5041.6   24.13  5271.7   28.27
  5473.3   24.89  5639.5   29.34    6613   27.27 12692.6   29.87 15359.3   31.59
 19454.6   30.39 19802.1    40.8   21200   40.88 24717.8   39.18 25015.9   43.67
#Mann= 14 ,-1 , 0
 -2832.1     .07       0 -1804.9     .14       0  -765.5     .07       0
  3408.6     .14       0  4131.2     .07       0  4304.4     .14       0
  4954.9     .04       0  5041.6     .14       0  5639.5     .08       0
    6613     .14       0 12692.6     .08       0 15359.3     .14       0
 19802.1     .07       0   21200     .13       0
#XS Ineff= 2 , 0
       0    2200      43   18000       0      43
Permanent Ineff=
       F       F
Bank Sta=4954.9,5041.6
XS Rating Curve= 0 ,0
Exp/Cntr=0.3,0.1

Type RM Length L Ch R = 1 ,505446  ,866,854,476
BEGIN DESCRIPTION:
Waccamaw River 141.0
END DESCRIPTION:
XS GIS Cut Line= 6
      2142326.13       131531.44      2136675.86       134125.29
      2130868.95       138062.39      2122488.34       142278.82
      2122234.58       142528.92      2117800.35       144133.79
#Sta/Elev= 30
 -1747.7   43.62  -250.9   41.24   775.8   39.99  2303.5   34.87  2595.8    38.3
  2961.2   40.89  3428.4   36.08  3454.4   31.73  4103.9   31.01    4696    25.3
  4968.9   25.86  4987.5   13.06  5048.7   25.65    5113   28.63  5199.7   25.09
  5532.4   27.89  5927.7   23.49  5971.7   27.39  6881.8   26.52  8125.4   29.37
  8754.1   30.81  8874.9   31.09  9044.4   31.48 15465.4   30.45 16257.2   31.49
 20093.4   31.36 20661.4   36.81 20866.8   42.25 22125.7   40.27 25938.8   43.53
#Mann= 16 ,-1 , 0
 -1747.7     .07       0  -250.9     .14       0   775.8     .07       0
  2595.8     .15       0  2961.2     .07       0  4103.9     .13       0
    4696     .14       0  6881.8     .08       0  8125.4     .08       0
  8754.1     .14       0  8874.9     .08       0  9044.4     .14       0
 15465.4     .08       0 16257.2     .14       0 20661.4     .07       0
 22125.7     .13       0
#XS Ineff= 2 ,-1
 -1650.9    3000   41.19   18000 25749.5   43.03
Permanent Ineff=
       F       F
Bank Sta=4968.9,5048.7
XS Rating Curve= 0 ,0
Exp/Cntr=0.3,0.1

Type RM Length L Ch R = 1 ,504592  ,3260,8290,424
BEGIN DESCRIPTION:
Waccamaw River 140.0
END DESCRIPTION:
XS GIS Cut Line= 6
      2142326.09        131472.6      2137902.13       132189.07
      2134956.46       134762.24      2130975.64       137528.01
       2122221.9       142516.24      2117799.09       144108.06
#Sta/Elev= 30
 -2762.7   43.68  -274.8    40.1  -210.8   39.86    1673   38.62  1774.7    29.4
  3150.1   31.56  3547.4   26.41  4113.8    31.3    4200   25.91  4415.7   26.76
  4621.2   28.77  4757.5   27.69  4968.9   25.03  4987.5   13.35  5048.7   24.02
  5433.4   25.74  5477.1   32.29  5539.5   27.28  6502.8   28.88  7600.8      32
  7731.5   32.06  8901.5   30.49 12370.9   29.77 12575.6   29.74 16984.5   29.78
 19761.5   35.64 19943.5   40.47 21439.3   41.15 23032.8   37.84 25266.4    43.3
#Mann= 17 ,-1 , 0
 -2762.7     .07       0  -274.8     .15       0  -210.8     .07       0
    1673     .13       0  4415.7      .1       0  4621.2     .13       0
  4757.5     .14       0  4968.9     .04       0  5048.7     .14       0
  6502.8     .08       0  7600.8     .14       0  7731.5     .08       0
  8901.5     .14       0 12370.9     .08       0 12575.6     .14       0
 19943.5     .07       0 21439.3     .13       0
#XS Ineff= 1 ,-1
   17000 24793.6   42.24
Permanent Ineff=
       F
Bank Sta=4968.9,5048.7
XS Rating Curve= 0 ,0
Exp/Cntr=0.3,0.1

Type RM Length L Ch R = 1 ,496302  ,3844,10207,424
BEGIN DESCRIPTION:
Waccamaw River 132.0
END DESCRIPTION:
XS GIS Cut Line= 6
      2139907.45       127239.14      2134974.28       132115.28
      2133440.94        135428.6      2122452.32       142250.37
      2122198.11       142507.88      2117849.29       144055.38
#Sta/Elev= 30
  -778.4    46.4    -258   38.11   181.5   42.96   247.8   26.93   372.5   24.95
  1075.2   25.35  1449.1   25.57  1783.2   25.76  2394.6   26.11  3374.5   27.66
    4932   28.44  4951.2   20.87  5036.2   14.65  5080.6   27.55  5125.7   22.54
  5958.2   30.49  8268.9   28.05  9230.4   30.22  9524.1   29.56  9959.6   34.52
 10452.1   30.73 12954.9   29.67 13289.4   29.67 14720.6   30.07 14819.8   30.02
 21190.7   29.84 21893.3   32.53 22389.8   40.55 23938.7    39.6 27722.5   43.31
#Mann= 18 ,-1 , 0
  -778.4     .07       0  1075.2     .13       0  1449.1     .08       0
  1783.2     .13       0  2394.6     .08       0  3374.5     .13       0
    4932     .04       0  5080.6     .13       0  8268.9     .07       0
  9230.4     .14       0  9524.1     .08       0 10452.1     .14       0
 12954.9     .07       0 13289.4     .14       0 14720.6     .08       0
 14819.8     .14       0 22389.8     .07       0 23938.7     .13       0
#XS Ineff= 2 ,-1
  -726.4   178.8      46   20000 27479.9   42.23
Permanent Ineff=
       F       F
Bank Sta=4932,5080.6
XS Rating Curve= 0 ,0
Exp/Cntr=0.3,0.1

Type RM Length L Ch R = 1 ,486095  ,922,1074,73
BEGIN DESCRIPTION:
Waccamaw River 123.0
END DESCRIPTION:
XS GIS Cut Line= 6
      2137674.98       126475.02      2134803.19       129092.64
       2133348.9       134995.34      2122449.97       142179.56
      2122186.81        142462.7      2117781.51        144021.5
#Sta/Elev= 30
  4081.9   44.29    4155   42.76    4178   40.77  4218.3   28.91  4266.3   25.11
  4658.9   26.81  4687.7   23.09  4847.8   27.56    4950   24.05  4953.9   18.21
  4975.8   12.45  5009.9    9.42  5048.8   18.14  5053.9   22.95  5153.1   23.78
  5501.6   26.62  5645.6    27.2  6232.8   29.16  7818.9   27.69  7967.7   23.26
  8115.6   27.65    8774   29.36 12636.9   29.83 13918.3   27.83 16942.8   30.34
 17720.2   30.37 24060.2   30.74 26398.6   37.49 28266.6   40.03 32160.1   43.04
#Mann= 14 ,-1 , 0
  4081.9     .07       0    4155     .13       0    4950     .04       0
  5053.9     .13       0  5153.1      .1       0  5501.6     .13       0
  5645.6      .1       0  6232.8     .13       0 12636.9     .07       0
 13918.3     .14       0 16942.8     .07       0 17720.2     .14       0
 26398.6     .07       0 28266.6     .13       0
#XS Ineff= 1 ,-1
   24000 31827.3   42.25
Permanent Ineff=
       F
Bank Sta=4950,5053.9
XS Rating Curve= 0 ,0
Exp/Cntr=0.5,0.3