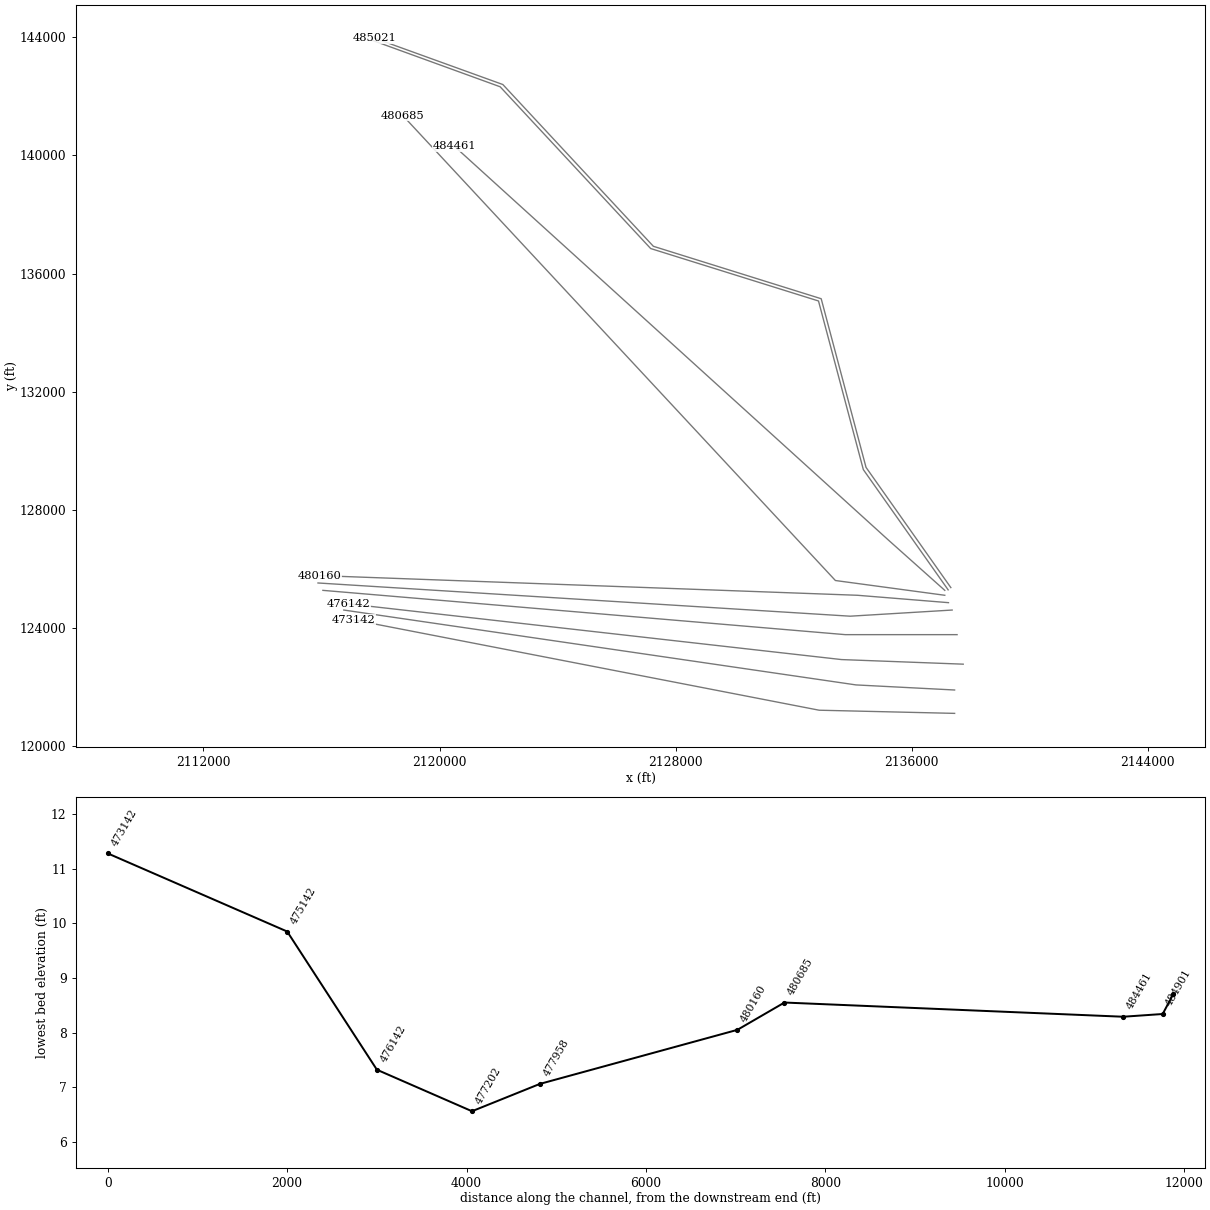
HEC-RAS study Waccamaw River.prj: Waccamaw River Detailed Study

--- Waccamaw River.g01 (geometry) --- (continued)

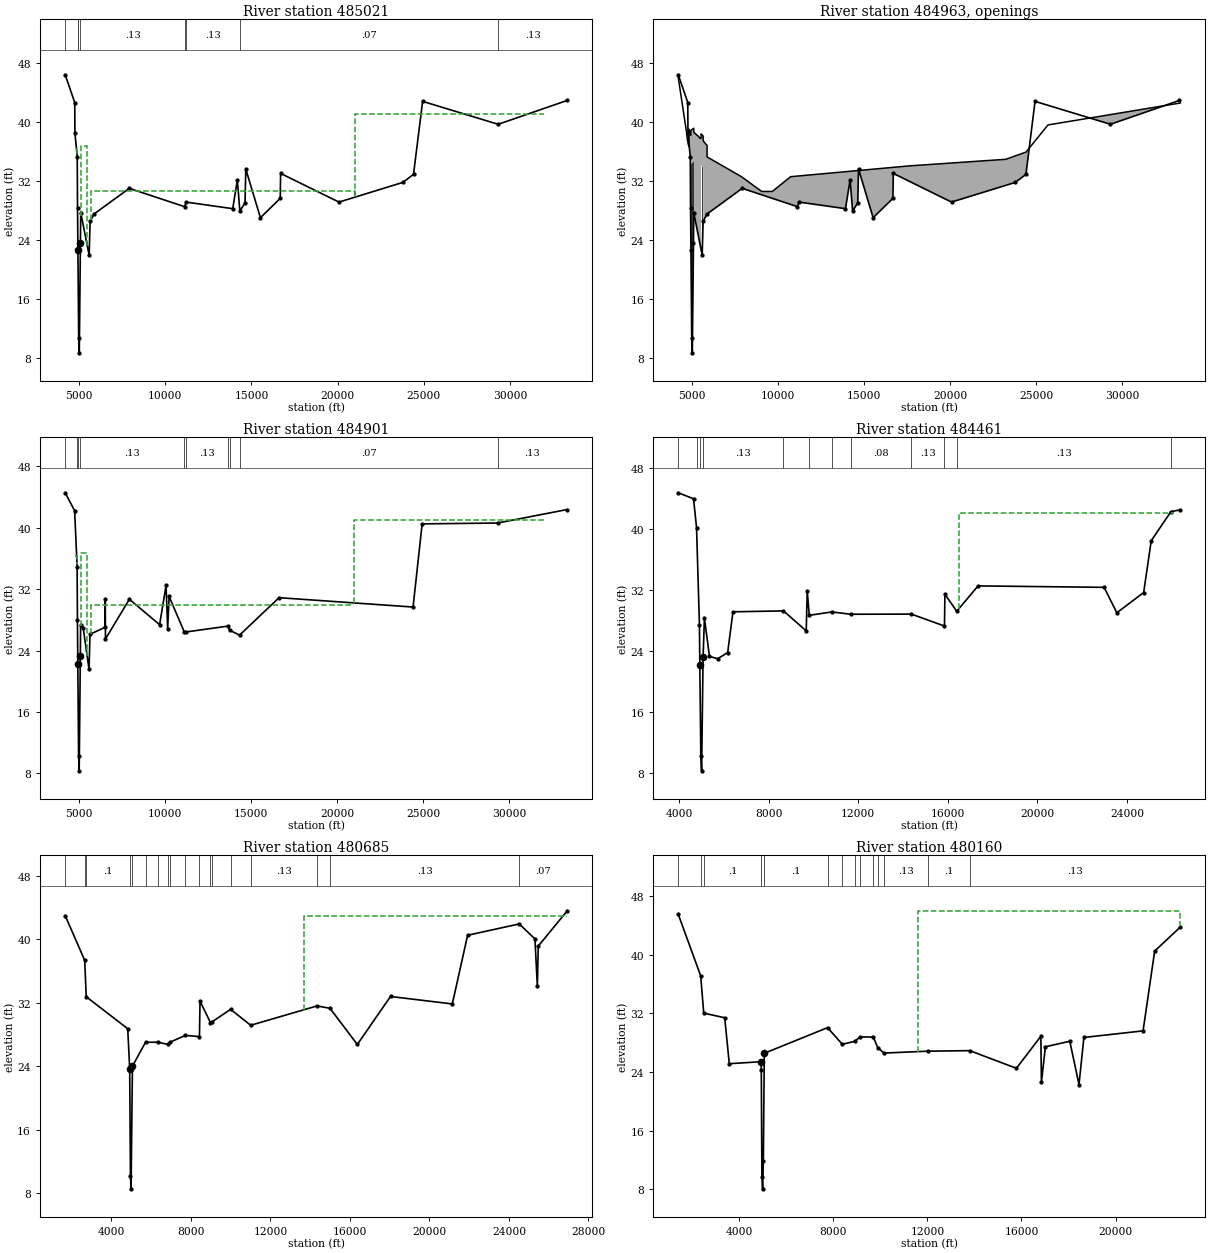
Type RM Length L Ch R = 1 ,485021  ,120,120,123
BEGIN DESCRIPTION:
Whiteville Road (WR) us
END DESCRIPTION:
XS GIS Cut Line= 6
       2137327.1       125368.57       2134453.2       129438.68
      2132933.49       135148.86      2127245.88       136924.36
      2122145.09       142401.32      2117815.37       143965.03
#Sta/Elev= 30
  4191.1   46.34  4743.1   42.58  4755.8   38.43  4888.4   35.25  4906.3    28.3
  4928.6   22.61  4973.7   10.69    5008    8.71  5074.6   23.62  5091.7    27.7
  5580.9   21.92  5635.4   26.49  5864.6    27.5  7909.3   30.97 11118.8   28.49
 11206.2   29.11 13913.2   28.22 14182.1   32.12 14325.1   27.89 14626.5   29.01
 14670.7   33.58 15519.7      27 16669.4   29.61 16692.7   32.99 20078.1   29.11
 23791.5   31.78 24404.7   32.87 24932.6   42.74 29317.6   39.64 33326.2   42.87
#Mann= 8 ,-1 , 0
  4191.1     .07       0  4906.3     .13       0  4928.6     .04       0
  5074.6     .13       0 11118.8      .1       0 11206.2     .13       0
 14325.1     .07       0 29317.6     .13       0
#XS Ineff= 4 ,-1
    4833  4883.3   36.32  5132.3    5480   36.67    5680   21000   30.55
 21000.1   32000      41
Permanent Ineff=
       F       F       F       F
Bank Sta=4928.6,5074.6
XS Rating Curve= 0 ,0
Exp/Cntr=0.5,0.3

Type RM Length L Ch R = 4 ,484963  ,,,
BEGIN DESCRIPTION:
Whiteville Road (WR) tor
Structure ID: BK_WAC_02
Detailed Survey Structure
END DESCRIPTION:
Bridge Culvert--1,0,-1,-1, 0
Deck Dist Width WeirC Skew NumUp NumDn MinLoCord MaxHiCord MaxSubmerge Is_Ogee
36,44,3,0, 36, 36, , , 0.95, 0, 1,1,,
  4196.4  4663.1  4718.9  4767.7  4807.9  4807.9  4917.1  4919.3  4919.3  4919.9
  5090.1  5096.3  5096.3    5099  5339.3  5464.5  5514.4    5516    5516  5516.7
  5638.1  5638.5  5638.5  5640.2  5865.6  5865.6  5866.7  7879.5  9042.5  9658.3
 10725.4 17665.7 23226.8 24409.9 25683.5 33378.1
   45.88   38.69    37.6   36.99   36.61      39   38.16   38.67   38.67   38.81
   39.11   38.72   38.72   38.55   38.06   37.73   37.76   38.16   38.16   38.34
   38.05   37.93   37.93    37.4   36.76   35.22   35.22   32.53   30.55   30.55
   32.55   34.02    34.9   35.88   39.55   42.52
  -11.29  -11.29  -11.29  -11.29  -11.29  -11.29  -11.29  -11.29   34.36   34.36
   34.71   34.72  -11.29  -11.29  -11.29  -11.29  -11.29  -11.29   34.09   34.09
   33.94   33.94  -11.29  -11.29  -11.29  -11.29  -11.29  -11.29  -11.29  -11.29
  -11.29  -11.29  -11.29  -11.29  -11.29  -11.29
  4196.4  4663.1  4718.9  4767.7  4807.9  4807.9  4917.1  4919.3  4919.3  4919.9
  5090.1  5096.3  5096.3    5099  5339.3  5464.5  5514.4    5516    5516  5516.7
  5638.1  5638.5  5638.5  5640.2  5865.6  5865.6  5866.7  7879.5  9042.5  9658.3
 10725.4 17665.7 23226.8 24409.9 25683.5 33378.1
   45.88   38.69    37.6   36.99   36.61      39   38.16   38.67   38.67   38.81
   39.11   38.72   38.72   38.55   38.06   37.73   37.76   38.16   38.16   38.34
   38.05   37.93   37.93    37.4   36.76   35.22   35.22   32.53   30.55   30.55
   32.55   34.02    34.9   35.88   39.55   42.52
  -11.29  -11.29  -11.29  -11.29  -11.29  -11.29  -11.29  -11.29   34.36   34.36
   34.71   34.72  -11.29  -11.29  -11.29  -11.29  -11.29  -11.29   34.09   34.09
   33.94   33.94  -11.29  -11.29  -11.29  -11.29  -11.29  -11.29  -11.29  -11.29
  -11.29  -11.29  -11.29  -11.29  -11.29  -11.29
Pier Skew, UpSta & Num, DnSta & Num=  ,4956.1, 2 ,4956.1, 2 , 0 , 0 , 0 ,0,0
     1.8     1.8
   15.71   34.43
     1.8     1.8
       8   34.43
Pier Skew, UpSta & Num, DnSta & Num=  ,5008, 2 ,5008, 2 , 0 , 0 , 0 ,0,0
     1.8     1.8
    8.71   34.54
     1.8     1.8
       8   34.54
Pier Skew, UpSta & Num, DnSta & Num=  ,5053.4, 2 ,5053.4, 2 , 0 , 0 , 0 ,0,0
     1.8     1.8
   17.91   34.63
     1.8     1.8
       8   34.63
Pier Skew, UpSta & Num, DnSta & Num=  ,5577, 2 ,5577, 2 , 0 , 0 , 0 ,0,0
     1.8     1.8
      22      36
     1.8     1.8
      22   34.02
Abutment Skew #Up #Dn= , 2 , 2
  4919.3  4950.1
   34.36   16.98
  4919.3  4950.1
   34.36   16.98
Abutment Skew #Up #Dn= , 2 , 2
  5049.2  5096.3
   16.84   34.72
  5049.2  5096.3
   16.84   34.72
Abutment Skew #Up #Dn= , 2 , 2
    5516    5536
   34.09   23.72
    5516    5536
   34.09   23.72
Abutment Skew #Up #Dn= , 2 , 2
  5618.5  5638.5
   23.75   33.94
  5618.5  5638.5
   23.75   33.94
BR Coef= 1 , 1 , 0 ,1.25, 0 ,,,0.8,0,2,0,
WSPro=,,,, 1 ,,,, 0 ,,,, 0 ,,,,-1 ,-1 ,-1 , 0 , 0 , 0 , 0 , 0
BR Coef= 1 , 1 , 0 ,1.25, 0 ,,,0.8,0,2,0,
WSPro=,,,, 1 ,,,, 0 ,,,, 0 ,,,,-1 ,-1 ,-1 , 0 , 0 , 0 , 0 , 0
BC Mult= 3 ,4191.1,5244.6,4195.7,5244.6
BC Mult= 3 ,5244.6,33326.2,5244.6,33368.7
BC Design=,, 0 ,, 0 ,,,,,,
BC HTab HWMax=46.34
BC Use User HTab Curves=0
BC User HTab FreeFlow(D)= 0

Type RM Length L Ch R = 1 ,484901  ,401,440,4707
BEGIN DESCRIPTION:
Whiteville Road (WR) ds
END DESCRIPTION:
XS GIS Cut Line= 6
      2137236.02       125292.23       2134362.1       129362.36
       2132842.4       135072.54      2127154.79       136848.04
      2122053.99         142325.      2117691.17       143908.53
#Sta/Elev= 30
  4195.7   44.55  4743.1   42.21  4888.4   34.88  4906.3   27.93  4928.6   22.24
  4973.7   10.32    5008    8.34  5074.6   23.25  5091.7   27.33  5244.5   26.91
  5580.9   21.55  5635.4   26.12  6507.2   27.03  6523.3   30.75  6535.5   25.51
  7923.5   30.69  9682.1   27.37 10056.2    32.5 10149.3   26.86 10233.2   31.05
 11118.8   26.41 11206.2   26.42 13656.5   27.19 13746.4   26.66 14325.1   26.01
 16622.7   30.89 24409.3   29.67 24937.3    40.5 29317.6   40.61 33368.7   42.37
#Mann= 10 ,-1 , 0
  4195.7     .07       0  4906.3     .13       0  4928.6     .04       0
  5074.6     .13       0 11118.8      .1       0 11206.2     .13       0
 13656.5     .07       0 13746.4     .13       0 14325.1     .07       0
 29317.6     .13       0
#XS Ineff= 4 ,-1
  4770.6  4879.3   36.32  5136.3    5470   36.67    5690   21000      30
 21000.1   32000      41
Permanent Ineff=
       F       F       F       F
Bank Sta=4928.6,5074.6
XS Rating Curve= 0 ,0
Exp/Cntr=0.5,0.3

Type RM Length L Ch R = 1 ,484461  ,1426,3776,1876
BEGIN DESCRIPTION:
Waccamaw River 122.0
END DESCRIPTION:
XS GIS Cut Line= 3
       2137122.2       125274.82       2135206.3       126982.48
      2120503.85       140310.47
#Sta/Elev= 30
  3966.7   44.78  4649.1   43.99  4782.7    40.2  4911.6   27.44  4928.6   22.19
  4973.7   10.27    5008    8.29  5074.6    23.2  5133.7   28.33  5359.7   23.31
  5724.7      23  6171.8   23.81    6408   29.16  8661.6   29.28  9678.6   26.66
  9723.4   31.89  9816.4    28.7 10812.4   29.14 11681.3   28.84 14369.1   28.86
 15849.7   27.29 15869.4   31.46 16397.2   29.23 17349.9   32.56 22976.3   32.37
 23543.4   29.03   24741   31.69 25079.2   38.49 25955.6    42.3 26377.5   42.54
#Mann= 12 ,-1 , 0
  3966.7     .07       0  4782.7     .13       0  4928.6     .04       0
  5074.6     .13       0  8661.6     .15       0  9816.4     .13       0
 10812.4     .15       0 11681.3     .08       0 14369.1     .13       0
 15849.7     .08       0 16397.2     .13       0 25955.6     .07       0
#XS Ineff= 1 ,-1
   16500 26074.4   42.08
Permanent Ineff=
       F
Bank Sta=4928.6,5074.6
XS Rating Curve= 0 ,0
Exp/Cntr=0.3,0.1

Type RM Length L Ch R = 1 ,480685  ,391,525,4164
BEGIN DESCRIPTION:
Waccamaw River 121.0
END DESCRIPTION:
XS GIS Cut Line= 3
      2137122.25       125108.22      2133415.35       125608.03
      2118754.55       141351.72
#Sta/Elev= 30
    1682   43.01  2663.3   37.36  2739.7   32.78  4826.9   28.74  4925.5   23.71
  4963.3   10.23  4993.8    8.55  5064.3   24.02  5721.1   27.04  6356.7   27.04
  6851.8   26.76  6951.3   27.04  7724.2    27.9  8434.8   27.75  8463.3   32.22
  8988.4   29.52  9055.4   29.59   10000   31.19 11011.8   29.18 14351.8   31.62
 15000.5   31.32 16375.3   26.76 18045.5   32.81 21154.5   31.87 21922.9   40.53
 24517.8   41.96 25309.3   40.08   25432   34.08 25476.3   39.16 26935.3   43.62
#Mann= 18 ,-1 , 0
    1682     .07       0  2663.3     .13       0  2739.7      .1       0
  4925.5     .04       0  5064.3      .1       0  5721.1     .13       0
  6356.7      .1       0  6851.8     .13       0  6951.3     .07       0
  7724.2     .15       0  8434.8     .14       0  8988.4      .1       0
  9055.4     .15       0   10000     .08       0 11011.8     .13       0
 14351.8     .07       0 15000.5     .13       0 24517.8     .07       0
#XS Ineff= 1 ,-1
   13700   27000      43
Permanent Ineff=
       F
Bank Sta=4925.5,5064.3
XS Rating Curve= 0 ,0
Exp/Cntr=0.3,0.1

Type RM Length L Ch R = 1 ,480160  ,589,2202,582
BEGIN DESCRIPTION:
Waccamaw River 117.0
END DESCRIPTION:
XS GIS Cut Line= 3
      2137247.13       124858.33      2134165.05       125108.23
      2115922.31       125774.63
#Sta/Elev= 30
  1407.2   45.52    2360   37.12  2490.4   32.03  3381.8    31.4  3576.2   25.13
  4925.5    25.4  4937.9   24.24  4963.3    9.73  4993.8    8.05  5025.3    11.9
  5064.3   26.55  7754.5   30.05  8381.8   27.78  8910.7   28.18  9138.6   28.78
  9696.5   28.77  9890.8   27.32 10154.4   26.58 12044.7   26.84 13801.5   26.91
 15784.7    24.5 16824.3   28.87   16849    22.6 17017.9   27.44 18055.1   28.19
 18446.3   22.29 18654.7   28.71 21170.7   29.61   21664    40.5 22754.3   43.78
#Mann= 14 ,-1 , 0
  1407.2     .07       0    2360     .13       0  2490.4      .1       0
  4925.5     .04       0  5064.3      .1       0  7754.5     .13       0
  8381.8      .1       0  8910.7     .13       0  9138.6      .1       0
  9696.5     .13       0  9890.8      .1       0 10154.4     .13       0
 12044.7      .1       0 13801.5     .13       0
#XS Ineff= 2 , 0
       0                   11600       0      46
Permanent Ineff=
       F       F
Bank Sta=4925.5,5064.3
XS Rating Curve= 0 ,0
Exp/Cntr=0.3,0.1

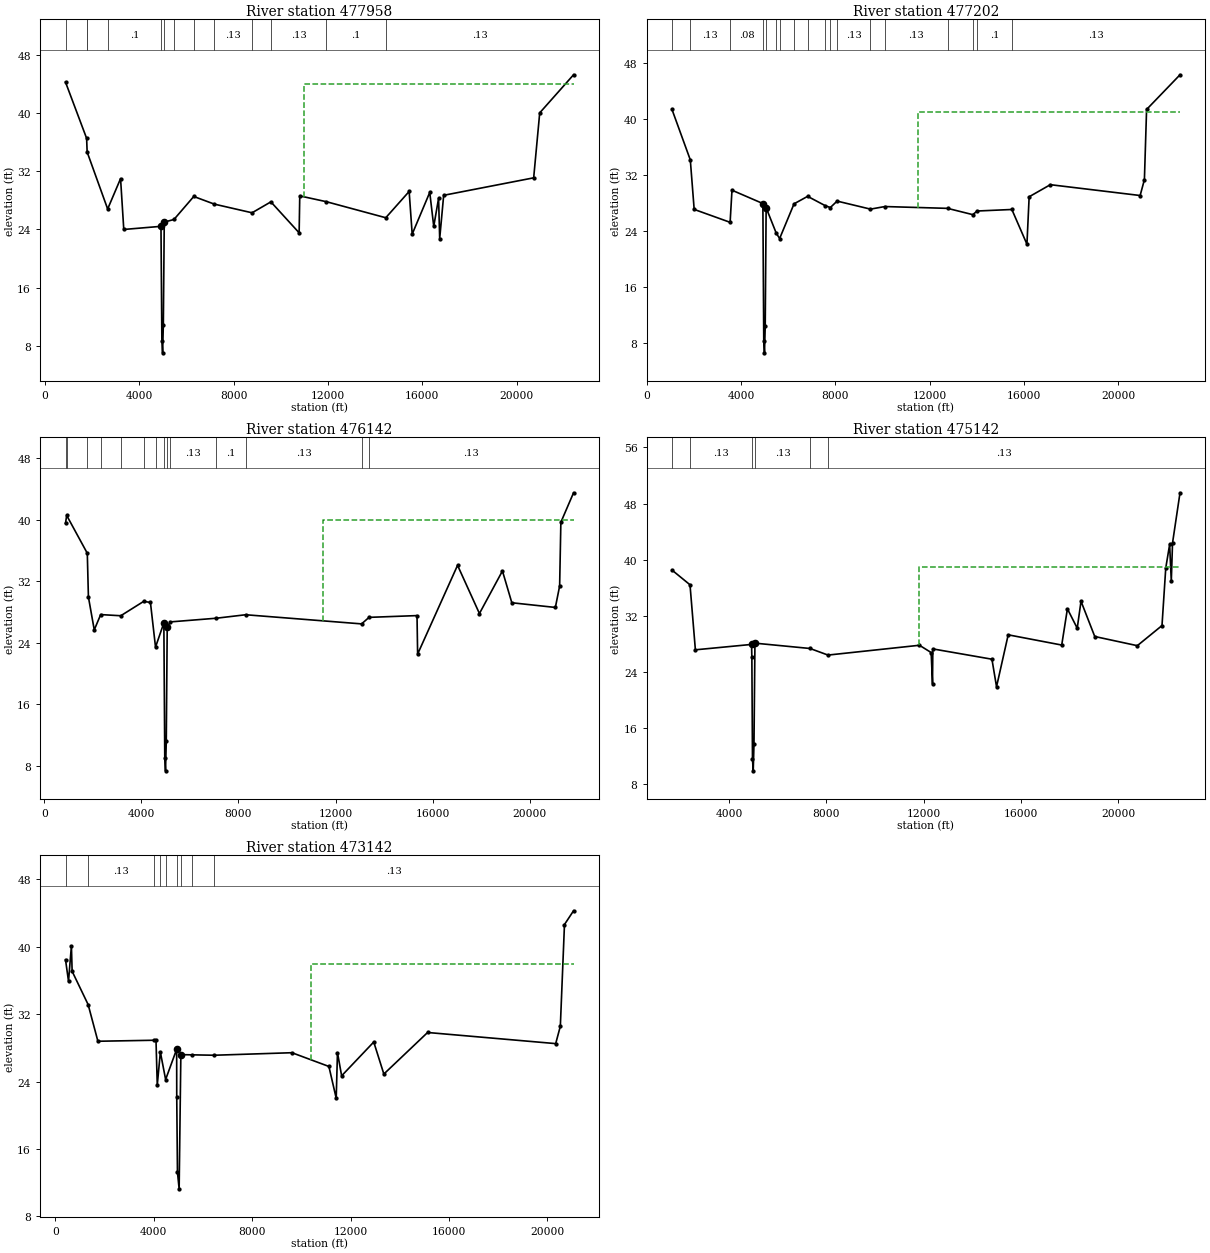
Type RM Length L Ch R = 1 ,477958  ,684,756,518
BEGIN DESCRIPTION:
Waccamaw River 116.0
END DESCRIPTION:
XS GIS Cut Line= 3
      2137372.07       124608.42      2133915.15       124400.17
      2115880.66       125524.73
#Sta/Elev= 30
     879   44.23  1774.4   36.51  1796.1   34.63  2665.6   26.81  3212.7   30.98
  3348.7      24  4925.5   24.43  4963.3    8.74  4993.8    7.06  5025.3   10.91
  5064.3   25.01  5475.6   25.37  6315.3   28.53  7186.5   27.48  8785.7   26.29
  9583.5   27.79 10781.1   23.54 10807.5   28.61 11938.3   27.81 14453.2   25.61
 15443.8   29.22 15572.8   23.36   16317   29.09 16486.6   24.42 16691.1   28.28
 16738.5   22.75 16907.1   28.69 20721.6   31.09 20977.8   40.01 22411.7   45.24
#Mann= 13 ,-1 , 0
     879     .07       0  1774.4    .035       0  1796.1     .13       0
  2665.6      .1       0  4925.5     .04       0  5064.3      .1       0
  5475.6     .13       0  6315.3      .1       0  7186.5     .13       0
  8785.7      .1       0  9583.5     .13       0 11938.3      .1       0
 14453.2     .13       0
#XS Ineff= 2 , 0
       0                   11000       0      44
Permanent Ineff=
       F       F
Bank Sta=4925.5,5064.3
XS Rating Curve= 0 ,0
Exp/Cntr=0.3,0.1

Type RM Length L Ch R = 1 ,477202  ,899,1060,709
BEGIN DESCRIPTION:
Waccamaw River 114.0
END DESCRIPTION:
XS GIS Cut Line= 3
      2137538.67       123775.42      2133748.55       123775.42
      2116047.26       125274.83
#Sta/Elev= 30
    1069   41.42  1846.9   34.19  2010.9    27.1    3536   25.25    3615   29.85
  4925.5   27.94  4963.3    8.24  4993.8    6.56  5025.3   10.41  5064.3   27.34
  5492.6    23.7  5636.5   22.93  6248.4    27.9  6824.6   28.97  7580.9   27.62
    7788   27.37    8075   28.29  9491.5   27.14 10102.6   27.51 12762.7   27.25
 13831.8   26.35 14014.9   26.87 15489.4   27.09 16129.2   22.12   16223   28.91
 17122.4   30.64 20931.9   29.09 21113.1   31.36 21205.3   41.41 22623.8   46.38
#Mann= 18 ,-1 , 0
    1069     .07       0  1846.9     .13       0    3536     .08       0
  4925.5     .04       0  5064.3     .08       0  5492.6     .08       0
  5636.5      .1       0  6248.4     .13       0  6824.6      .1       0
  7580.9     .13       0    7788      .1       0    8075     .13       0
  9491.5      .1       0 10102.6     .13       0 12762.7      .1       0
 13831.8     .13       0 14014.9      .1       0 15489.4     .13       0
#XS Ineff= 2 , 0
       0                   11500       0      41
Permanent Ineff=
       F       F
Bank Sta=4925.5,5064.3
XS Rating Curve= 0 ,0
Exp/Cntr=0.3,0.1

Type RM Length L Ch R = 1 ,476142  ,852,1000,614
BEGIN DESCRIPTION:
Waccamaw River 113.0
END DESCRIPTION:
XS GIS Cut Line= 3
      2137746.95       122775.82      2133622.98       122931.46
      2116921.95       124816.67
#Sta/Elev= 30
   873.1   39.53   921.9   40.55  1770.9   35.63  1817.1   29.94  2057.8   25.66
  2322.5   27.65    3151    27.5  4094.9   29.37  4372.5   29.23  4582.3   23.42
  4925.5   26.57  4963.3       9  4993.8    7.32  5025.3   11.17  5064.3   26.08
  5196.3    26.7  7091.9   27.18  8298.3   27.63 13073.1   26.44   13380   27.29
 15357.1   27.52 15382.2   22.51 17027.7   34.06 17929.1   27.79 18877.3   33.33
 19263.9   29.19 21057.9   28.58 21233.8   31.37 21284.4   39.66 21807.1    43.5
#Mann= 14 ,-1 , 0
   873.1     .14       0   921.9     .07       0  1770.9     .13       0
  2322.5     .13       0    3151     .13       0  4094.9     .08       0
  4582.3      .1       0  4925.5     .04       0  5064.3      .1       0
  5196.3     .13       0  7091.9      .1       0  8298.3     .13       0
 13073.1      .1       0   13380     .13       0
#XS Ineff= 2 , 0
       0                   11500       0      40
Permanent Ineff=
       F       F
Bank Sta=4925.5,5064.3
XS Rating Curve= 0 ,0
Exp/Cntr=0.3,0.1

Type RM Length L Ch R = 1 ,475142  ,873,2000,958
BEGIN DESCRIPTION:
Waccamaw River 112.0
END DESCRIPTION:
XS GIS Cut Line= 3
      2137455.39       121901.17      2134112.93       122073.43
      2116755.36       124608.42
#Sta/Elev= 30
  1653.1    38.5  2394.6    36.4  2615.6   27.12  4925.5   27.89  4937.9   26.04
  4963.3   11.53  4993.8    9.85  5025.3    13.7  5064.3   28.07  7330.1   27.31
  8068.1   26.37 11828.1   27.77 12309.7   26.73 12365.8   22.28 12377.7   27.25
 14808.8   25.78 14997.8   21.85 15477.2   29.26 17678.1    27.8 17911.8   32.97
 18315.7    30.2 18471.3   34.05 19036.2   29.02 20785.8   27.71   21801   30.58
 21955.1   38.78 22114.9   42.15 22183.1    36.9 22234.1   42.37 22541.7   49.53
#Mann= 6 ,-1 , 0
  1653.1     .07       0  2394.6     .13       0  4925.5     .04       0
  5064.3     .13       0  7330.1      .1       0  8068.1     .13       0
#XS Ineff= 2 , 0
       0                   11800       0      39
Permanent Ineff=
       F       F
Bank Sta=4925.5,5064.3
XS Rating Curve= 0 ,0
Exp/Cntr=0.3,0.1

Type RM Length L Ch R = 1 ,473142  ,861,1000,972
BEGIN DESCRIPTION:
Waccamaw River 110.0
END DESCRIPTION:
XS GIS Cut Line= 3
      2137455.43       121109.82      2132864.38       121216.93
      2117088.48       124275.23
#Sta/Elev= 30
   407.7   38.47   530.4   35.91   647.8   40.11   677.1   37.09  1328.3   33.14
  1725.6   28.79  4018.5   28.91    4088   28.91  4139.7    23.6  4265.5   27.51
  4479.3   24.25  4928.3   27.84  4931.6   22.23  4960.5   13.25  5029.1   11.28
  5098.8    27.2  5536.8   27.18  6449.8   27.13    9617   27.43 11119.7    25.8
 11417.1   22.03 11468.3   27.44 11637.9   24.69 12943.9    28.7 13354.8    24.9
 15133.8   29.83 20343.5   28.51 20532.3   30.57 20700.4   42.64 21069.6   44.27
#Mann= 9 ,-1 , 0
   407.7     .07       0  1328.3     .13       0  4018.5     .07       0
  4265.5     .13       0  4479.3     .07       0  4928.3     .04       0
  5098.8     .07       0  5536.8     .08       0  6449.8     .13       0
#XS Ineff= 2 , 0
       0                   10400       0      38
Permanent Ineff=
       F       F
Bank Sta=4928.3,5098.8
XS Rating Curve= 0 ,0
Exp/Cntr=0.3,0.1