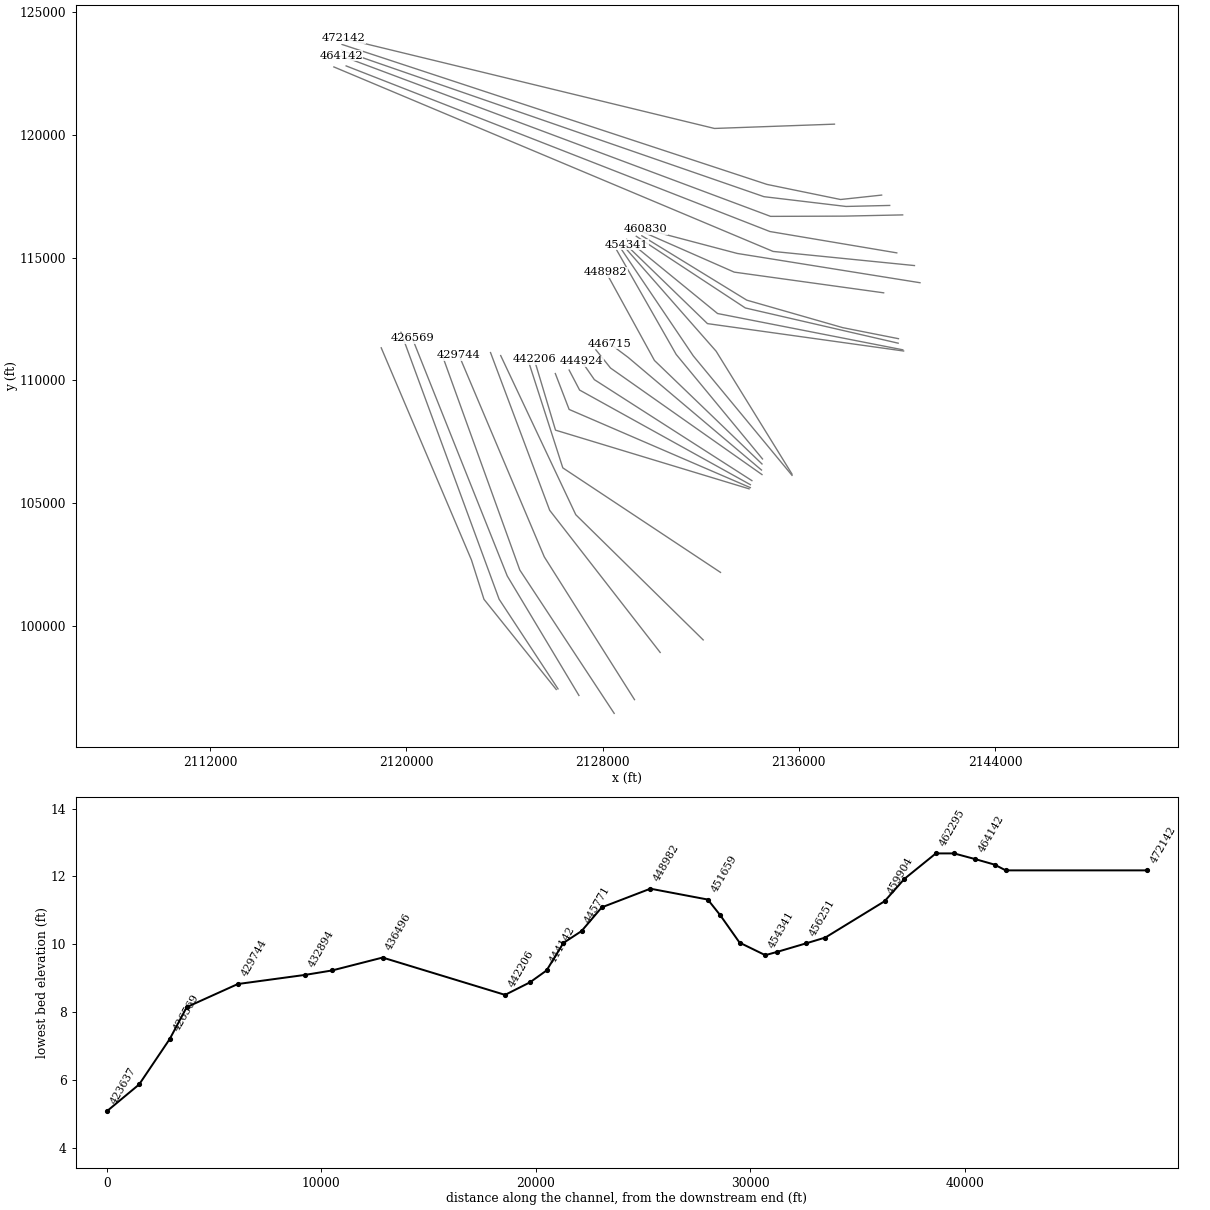
HEC-RAS study Waccamaw River.prj: Waccamaw River Detailed Study

--- Waccamaw River.g01 (geometry) --- (continued)

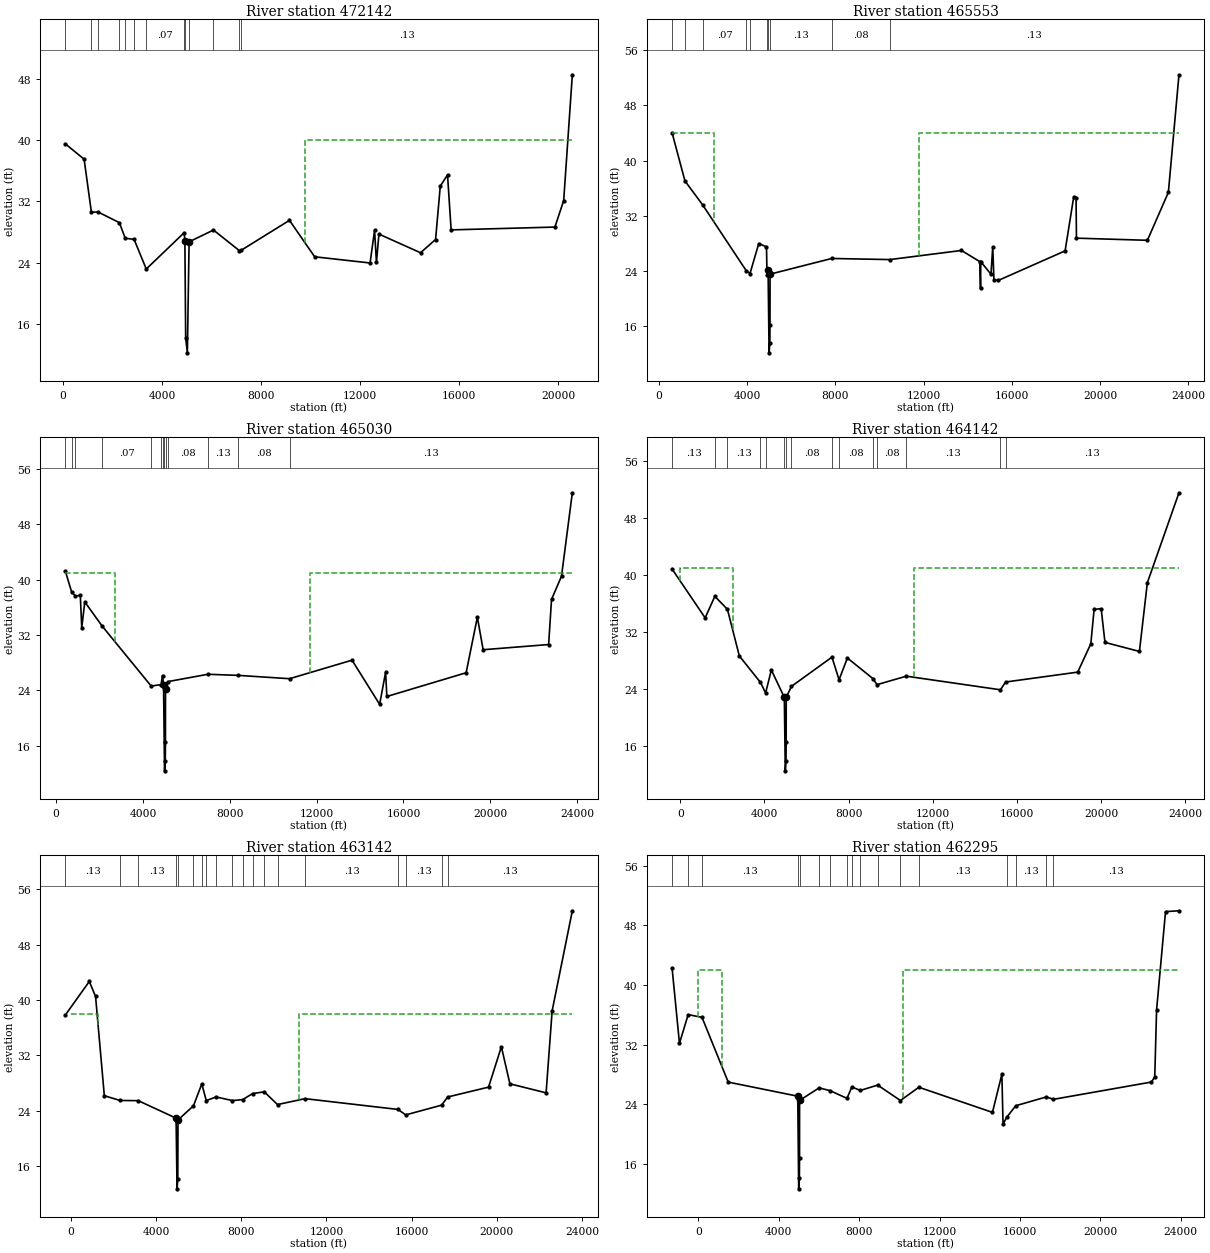
Type RM Length L Ch R = 1 ,472142  ,2872,6589,1686
BEGIN DESCRIPTION:
Waccamaw River 109.0
END DESCRIPTION:
XS GIS Cut Line= 3
      2137455.36       120443.42      2132562.31       120268.03
      2117421.69       123942.03
#Sta/Elev= 30
   103.8   39.52   857.8   37.52  1151.7   30.59  1421.9   30.61  2281.4   29.22
  2519.4   27.17  2875.6   27.04  3368.5   23.15  4898.6    27.9  4928.3   26.85
  4960.5   14.15  5029.1   12.18  5098.8   26.71  6083.7   28.25  7127.5   25.56
  7196.1   25.59  9153.2   29.52 10171.4   24.75 12409.7   23.94 12590.8   28.21
   12667   24.01 12766.7   27.72 14447.5   25.28 15055.5   27.01 15245.5      34
 15538.4   35.47 15684.1   28.27 19876.1   28.64 20230.8   32.11   20580   48.57
#Mann= 13 ,-1 , 0
   103.8     .07       0  1151.7     .13       0  1421.9     .07       0
  2281.4     .13       0  2519.4     .07       0  2875.6     .08       0
  3368.5     .07       0  4898.6     .13       0  4928.3     .04       0
  5098.8     .13       0  6083.7     .08       0  7127.5     .12       0
  7196.1     .13       0
#XS Ineff= 2 , 0
       0                    9800       0      40
Permanent Ineff=
       F       F
Bank Sta=4928.3,5098.8
XS Rating Curve= 0 ,0
Exp/Cntr=0.3,0.1

Type RM Length L Ch R = 1 ,465553  ,427,523,644
BEGIN DESCRIPTION:
Waccamaw River 103.0
END DESCRIPTION:
XS GIS Cut Line= 4
      2139378.17       117551.26      2137703.86       117371.22
       2134706.5       117986.07      2117380.03       123692.14
#Sta/Elev= 30
   593.8   44.03    1177   37.06  1987.7   33.56  3958.3   24.06  4126.7   23.66
  4523.6      28  4874.6   27.52  4898.8   23.41  4946.8   24.19  4992.5   12.18
  5026.7   13.58  5033.7   16.28  5036.8   23.57  7833.6   25.84 10468.9   25.68
 13715.8      27 14545.2   25.39 14581.1    21.5 14592.5   25.38 15055.2   23.55
 15134.1   27.53   15189   22.73 15392.1   22.67 18415.8   26.94 18806.3   34.75
 18911.9   34.66   18931   28.78 22147.7   28.47 23098.4   35.41 23579.4   52.43
#Mann= 10 ,-1 , 0
   593.8     .07       0    1177     .13       0  1987.7     .07       0
  3958.3     .13       0  4126.7     .07       0  4898.8     .13       0
  4946.8     .04       0  5036.8     .13       0  7833.6     .08       0
 10468.9     .13       0
#XS Ineff= 2 , 0
       0    2500      44   11800       0      44
Permanent Ineff=
       F       F
Bank Sta=4946.8,5036.8
XS Rating Curve= 0 ,0
Exp/Cntr=0.3,0.1

Type RM Length L Ch R = 1 ,465030  ,637,888,789
BEGIN DESCRIPTION:
Waccamaw River 102.0
END DESCRIPTION:
XS GIS Cut Line= 4
      2139706.95       117129.54      2137927.34       117087.96
      2134581.55       117486.27      2117380.09       123442.22
#Sta/Elev= 30
   427.2   41.19   712.1    38.2   885.3   37.63  1111.6   37.71  1178.6   33.06
  1318.5   36.77  2117.3   33.28  4376.3   24.61  4828.6   24.81  4899.3   26.13
  4946.8   24.77  4992.5   12.35  5026.7   13.75  5033.7   16.45  5036.8   24.21
  5129.2   25.24  6989.4   26.31  8394.6   26.15 10752.2   25.67 13630.4   28.35
 14902.4   21.96 15177.3   26.61 15234.7    23.1 18886.9   26.53 19404.7   34.56
 19670.7   29.86 22688.2   30.61 22821.9   37.13 23281.5   40.49 23780.1   52.55
#Mann= 13 ,-1 , 0
   427.2     .13       0   712.1     .07       0   885.3     .13       0
  2117.3     .07       0  4376.3     .13       0  4828.6     .07       0
  4899.3     .13       0  4946.8     .04       0  5036.8     .13       0
  5129.2     .08       0  6989.4     .13       0  8394.6     .08       0
 10752.2     .13       0
#XS Ineff= 2 , 0
       0    2700      41   11700       0      41
Permanent Ineff=
       F       F
Bank Sta=4946.8,5036.8
XS Rating Curve= 0 ,0
Exp/Cntr=0.3,0.1

Type RM Length L Ch R = 1 ,464142  ,815,1000,756
BEGIN DESCRIPTION:
Waccamaw River 101.0
END DESCRIPTION:
XS GIS Cut Line= 4
      2140235.93       116743.56      2137841.36       116693.56
      2134850.27       116683.57      2117338.38       123233.99
#Sta/Elev= 30
  -386.2   40.82  1184.2   33.97  1644.1   36.99  2241.6   35.18  2808.6   28.63
  3808.4   24.93  4058.1   23.44  4330.4   26.66  4946.8   22.81  4992.5   12.51
  5026.7   13.91  5033.7   16.61  5036.8   22.82  5284.4   24.36  7209.6   28.46
  7546.7   25.29    7943   28.34  9155.5   25.45  9350.6    24.6 10741.5   25.79
 15215.3   23.88 15458.1   24.97   18887   26.36 19508.4   30.34 19665.6   35.16
 19999.8   35.26 20180.8   30.53 21817.3   29.26 22194.3    38.9 23696.9   51.52
#Mann= 15 ,-1 , 0
  -386.2     .13       0  1644.1     .07       0  2241.6     .13       0
  3808.4     .07       0  4058.1     .13       0  4946.8     .04       0
  5036.8     .13       0  5284.4     .08       0  7209.6     .13       0
  7546.7     .08       0  9155.5     .13       0  9350.6     .08       0
 10741.5     .13       0 15215.3     .08       0 15458.1     .13       0
#XS Ineff= 2 , 0
       0    2500      41   11100       0      41
Permanent Ineff=
       F       F
Bank Sta=4946.8,5036.8
XS Rating Curve= 0 ,0
Exp/Cntr=0.3,0.1

Type RM Length L Ch R = 1 ,463142  ,746,847,885
BEGIN DESCRIPTION:
Waccamaw River 100.0
END DESCRIPTION:
XS GIS Cut Line= 3
      2139996.01       115195.52       2134822.3       116065.81
      2117546.67       122817.48
#Sta/Elev= 30
  -246.4   37.84   873.6   42.67  1167.6    40.5  1578.5   26.15  2309.1   25.46
  3172.4   25.43  4946.8    22.9  4992.5   12.68  5026.7   14.08  5036.8   22.64
  5764.3   24.69  6154.7   27.86  6363.7   25.44  6823.7   25.97    7592   25.44
    8076   25.59  8534.6   26.45  9084.6   26.71  9708.4   24.87 11001.9   25.72
 15369.1   24.16 15724.8   23.37 17408.9   24.78 17695.9   25.96 19615.6   27.39
 20217.2   33.23   20617   27.87 22316.7   26.56 22600.1   38.42 23548.1   52.89
#Mann= 19 ,-1 , 0
  -246.4     .13       0  2309.1     .07       0  3172.4     .13       0
  4946.8     .04       0  5036.8     .13       0  5764.3     .08       0
  6154.7     .13       0  6363.7     .08       0  6823.7     .13       0
    7592     .08       0    8076     .13       0  8534.6     .08       0
  9084.6     .13       0  9708.4     .08       0 11001.9     .13       0
 15369.1     .08       0 15724.8     .13       0 17408.9     .08       0
 17695.9     .13       0
#XS Ineff= 2 , 0
       0    1300      38   10700       0      38
Permanent Ineff=
       F       F
Bank Sta=4946.8,5036.8
XS Rating Curve= 0 ,0
Exp/Cntr=0.3,0.1

Type RM Length L Ch R = 1 ,462295  ,372,1465,1455
BEGIN DESCRIPTION:
Waccamaw River 99.0
END DESCRIPTION:
XS GIS Cut Line= 3
      2140716.36       114678.15      2134953.24       115254.47
       2117046.9       122775.81
#Sta/Elev= 30
 -1304.9   42.26  -938.1   32.19  -504.1   36.04   183.1   35.67  1487.2   26.99
  4946.8    25.1  4992.5   12.68  5026.7   14.08  5033.7   16.78  5036.8   24.54
  6008.6   26.21  6549.4   25.85    7394   24.81  7637.3   26.34  8056.9   25.87
  8920.3   26.59 10055.1   24.52 10969.7    26.3 14631.6   22.93 15099.8   28.04
 15157.6   21.35 15333.3   22.25 15788.7   23.82 17308.9      25 17665.4   24.68
 22542.1      27 22704.1    27.7 22795.4   36.68   23240   49.85 23908.8   49.96
#Mann= 17 ,-1 , 0
 -1304.9     .13       0  -504.1     .07       0   183.1     .13       0
  4946.8     .04       0  5036.8     .13       0  6008.6     .08       0
  6549.4     .13       0    7394     .08       0  7637.3     .13       0
  8056.9     .08       0  8920.3     .13       0 10055.1     .08       0
 10969.7     .13       0 15333.3     .08       0 15788.7     .13       0
 17308.9     .08       0 17665.4     .13       0
#XS Ineff= 2 , 0
       0    1200      42   10200       0      42
Permanent Ineff=
       F       F
Bank Sta=4946.8,5036.8
XS Rating Curve= 0 ,0
Exp/Cntr=0.3,0.1

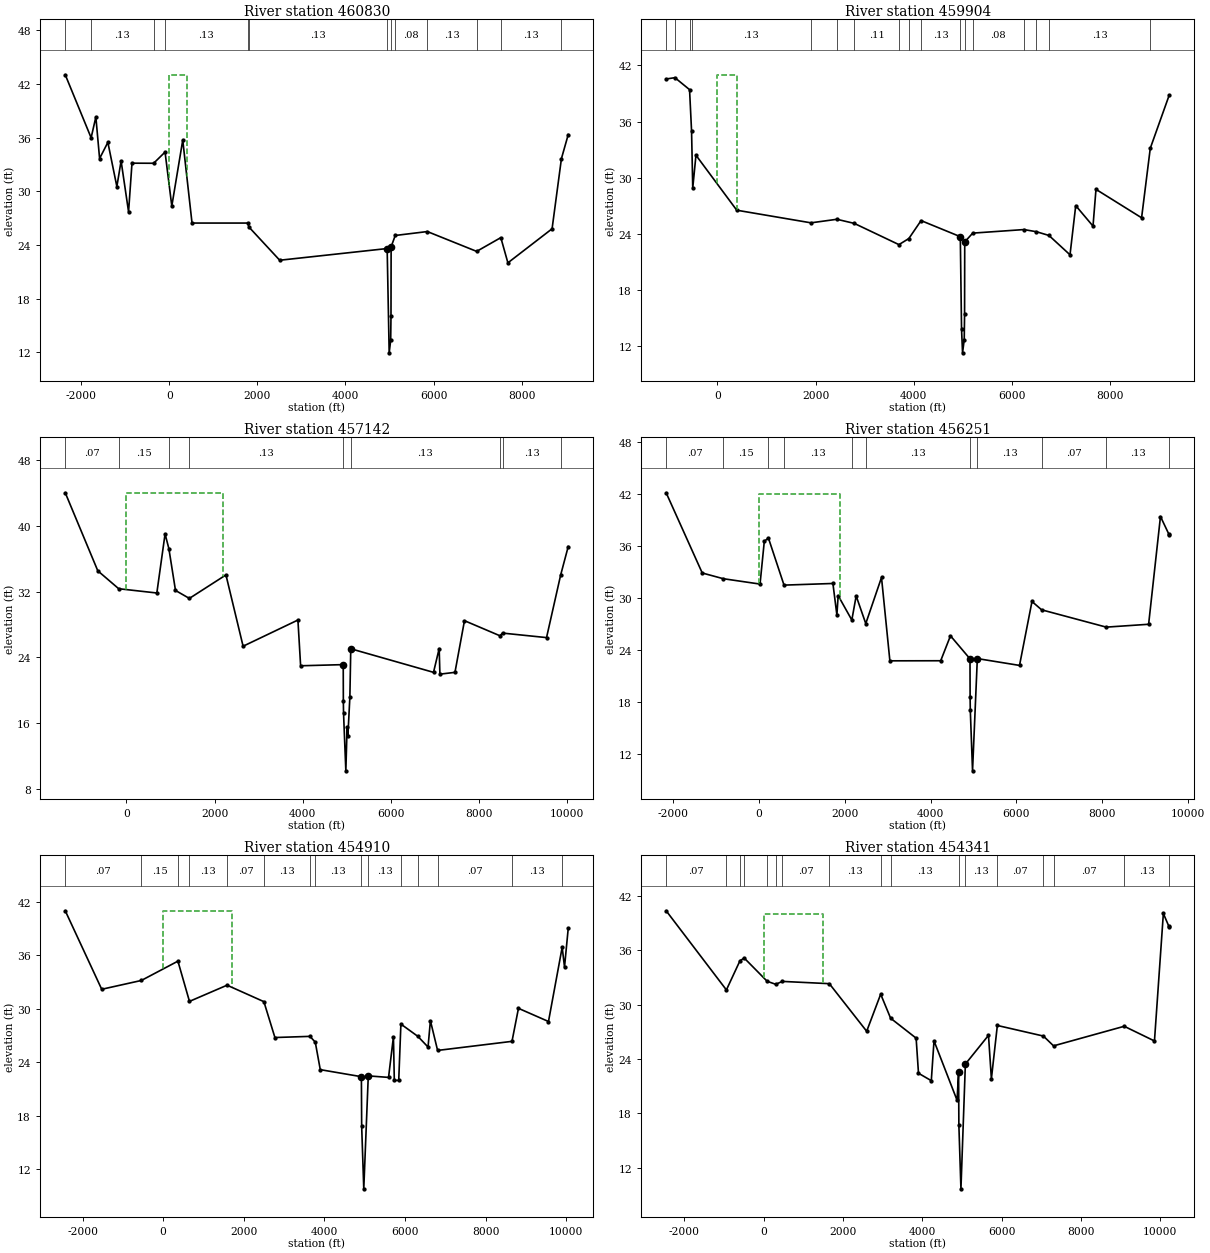
Type RM Length L Ch R = 1 ,460830  ,749,926,610
BEGIN DESCRIPTION:
Waccamaw River 98.0
END DESCRIPTION:
XS GIS Cut Line= 3
      2140942.76       113978.35      2133491.89       115172.14
      2129745.87       116160.09
#Sta/Elev= 30
   -2362   43.04 -1774.6   35.99 -1667.1   38.32 -1582.4   33.67 -1394.4   35.48
 -1190.2   30.53 -1094.1    33.4  -924.6   27.71  -846.8   33.15  -355.5   33.14
   -96.1   34.39    57.2   28.35   305.6   35.73   516.4   26.45  1781.1   26.45
  1807.3   26.01  2507.2   22.29  4946.8    23.6  4992.5   11.93  5026.7   13.33
  5033.7   16.03  5036.8   23.79  5130.2   25.06  5858.6    25.5  6978.7   23.28
  7527.3   24.82    7688      22  8691.3   25.81  8903.5   33.66    9058   36.35
#Mann= 13 ,-1 , 0
   -2362     .07       0 -1774.6     .13       0  -355.5     .07       0
   -96.1     .13       0  1781.1     .11       0  1807.3     .13       0
  4946.8     .04       0  5036.8     .13       0  5130.2     .08       0
  5858.6     .13       0  6978.7     .08       0  7527.3     .13       0
  8903.5     .07       0
#XS Ineff= 2 , 0
       0     400      43               0
Permanent Ineff=
       F       F
Bank Sta=4946.8,5036.8
XS Rating Curve= 0 ,0
Exp/Cntr=0.3,0.1

Type RM Length L Ch R = 1 ,459904  ,1350,2762,607
BEGIN DESCRIPTION:
Waccamaw River 97.0
END DESCRIPTION:
XS GIS Cut Line= 3
      2139460.75       113566.71      2133368.39       114410.59
      2129622.43       116057.16
#Sta/Elev= 30
 -1043.1   40.55  -864.7   40.69  -566.6   39.41  -525.9   35.01  -501.6   28.89
  -436.1    32.4   394.5   26.52  1905.8   25.17  2433.7   25.55  2787.5   25.11
  3697.1   22.84  3898.8   23.49  4147.8   25.41  4946.8   23.69  4971.9   13.82
  4992.5   11.27  5026.7   12.67  5033.7   15.37  5036.8   23.13  5199.5   24.07
  6241.9   24.45  6496.9   24.22    6752   23.82  7180.7   21.75  7297.2   27.01
    7649   24.82  7709.6   28.75  8638.4   25.71  8815.2   33.14  9199.3    38.8
#Mann= 17 ,-1 , 0
 -1043.1     .07       0  -864.7    .035       0  -566.6     .07       0
  -525.9     .13       0  1905.8     .11       0  2433.7     .13       0
  2787.5     .11       0  3697.1     .13       0  3898.8     .11       0
  4147.8     .13       0  4946.8     .04       0  5036.8     .13       0
  5199.5     .08       0  6241.9     .13       0  6496.9     .08       0
    6752     .13       0  8815.2     .07       0
#XS Ineff= 2 , 0
       0     400      41               0
Permanent Ineff=
       F       F
Bank Sta=4946.8,5036.8
XS Rating Curve= 0 ,0
Exp/Cntr=0.3,0.1

Type RM Length L Ch R = 1 ,457142  ,394,891,231
BEGIN DESCRIPTION:
Waccamaw River 95.0
END DESCRIPTION:
XS GIS Cut Line= 4
      2140064.41       111697.22      2137793.61       112146.52
      2133880.16       113268.04       2129601.8       115892.53
#Sta/Elev= 30
 -1385.8   44.05  -647.8   34.55  -173.8   32.37   690.8   31.85   877.5   39.04
   963.8   37.25  1113.9   32.16  1428.5   31.19  2257.8   34.05  2646.9   25.37
    3890   28.56    3951   22.99  4917.4   23.13  4919.9   18.67  4924.3   17.23
  4976.5    10.2  5004.8   15.48  5023.3   14.49    5068   19.21  5088.2   25.06
  6964.5   22.19  7092.9   25.09  7109.3   21.97  7450.8   22.19  7666.3   28.48
  8471.9   26.64  8528.7   26.97  9527.2   26.42  9846.5   34.02 10019.2   37.51
#Mann= 9 ,-1 , 0
 -1385.8     .07       0  -173.8     .15       0   963.8     .07       0
  1428.5     .13       0  4917.4     .04       0  5088.2     .13       0
  8471.9     .07       0  8528.7     .13       0  9846.5     .07       0
#XS Ineff= 2 , 0
       0    2200      44               0
Permanent Ineff=
       F       F
Bank Sta=4917.4,5088.2
XS Rating Curve= 0 ,0
Exp/Cntr=0.3,0.1

Type RM Length L Ch R = 1 ,456251  ,506,1341,660
BEGIN DESCRIPTION:
Waccamaw River 94.0
END DESCRIPTION:
XS GIS Cut Line= 4
      2140052.39       111513.78      2137752.45       112043.61
      2133821.21       112949.24      2129375.36       115871.96
#Sta/Elev= 30
 -2159.4   42.13 -1318.8   32.87  -828.6   32.21    27.2   31.59   126.8   36.54
   222.9    36.9   585.9   31.47  1724.6   31.66  1817.1   28.02  1846.6   30.26
  2165.1   27.44  2266.2   30.22  2489.8   27.03  2856.2   32.35  3051.4   22.73
    4235   22.74  4462.6   25.62  4917.4   22.96  4919.9    18.5  4924.3   17.06
  4976.5   10.03  5088.2   22.99  6070.7    22.2    6361   29.58    6585   28.62
  8091.1   26.62  9077.7   26.95  9353.6   39.39  9550.2   37.34  9555.5   37.29
#Mann= 11 ,-1 , 0
 -2159.4     .07       0  -828.6     .15       0   222.9     .07       0
   585.9     .13       0  2165.1     .07       0  2489.8     .13       0
  4917.4     .04       0  5088.2     .13       0    6585     .07       0
  8091.1     .13       0  9550.2     .07       0
#XS Ineff= 2 , 0
       0    1900      42               0
Permanent Ineff=
       F       F
Bank Sta=4917.4,5088.2
XS Rating Curve= 0 ,0
Exp/Cntr=0.3,0.1

Type RM Length L Ch R = 1 ,454910  ,413,569,461
BEGIN DESCRIPTION:
Waccamaw River 93.0
END DESCRIPTION:
XS GIS Cut Line= 4
      2140240.62         111244.      2137628.95       111755.46
      2132689.17       112722.83      2128984.34       115748.44
#Sta/Elev= 30
 -2429.4   41.02 -1524.8    32.2    -542   33.19   365.6   35.36   652.1   30.84
  1585.4   32.66  2498.4   30.81  2772.1   26.78  3641.6   26.91  3773.4   26.26
  3897.2   23.17  4917.4   22.38  4924.3   16.81  4976.5    9.78  5088.2   22.47
    5591    22.3  5712.3   26.86    5734   21.97  5843.6   21.96  5897.4   28.29
  6318.5   26.91  6570.6   25.71  6629.7   28.67    6808   25.33  8653.5   26.35
  8813.9   30.06  9558.9   28.58  9898.5   36.92  9956.5    34.7 10048.8   39.05
#Mann= 15 ,-1 , 0
 -2429.4     .07       0    -542     .15       0   365.6     .07       0
   652.1     .13       0  1585.4     .07       0  2498.4     .13       0
  3641.6     .07       0  3773.4     .13       0  4917.4     .04       0
  5088.2     .13       0  5897.4     .07       0  6318.5     .13       0
    6808     .07       0  8653.5     .13       0  9898.5     .07       0
#XS Ineff= 2 , 0
       0    1700      41               0
Permanent Ineff=
       F       F
Bank Sta=4917.4,5088.2
XS Rating Curve= 0 ,0
Exp/Cntr=0.3,0.1

Type RM Length L Ch R = 1 ,454341  ,2169,1199,371
BEGIN DESCRIPTION:
Waccamaw River 92.0
END DESCRIPTION:
XS GIS Cut Line= 4
      2140275.12       111194.53      2137731.86       111549.63
      2132277.52       112311.18      2128963.72       115522.07
#Sta/Elev= 30
 -2460.5   40.35  -940.7   31.62  -598.9   34.83  -491.7   35.14    88.5   32.57
   304.6   32.24   469.9   32.56  1656.3   32.31  2598.5   27.06  2951.7   31.15
  3202.1    28.5    3846    26.3  3905.5   22.43  4228.6   21.61  4297.1      26
  4878.8   19.45  4917.4   22.61  4924.3   16.71  4976.5    9.68  5088.2   23.44
  5671.6   26.61  5744.7   21.82    5895    27.7  7057.1   26.53  7312.9   25.45
    9096   27.61  9858.7   25.99 10083.2   40.05 10219.6   38.66 10228.9   38.56
#Mann= 17 ,-1 , 0
 -2460.5     .07       0  -940.7     .13       0  -598.9     .07       0
  -491.7     .15       0    88.5     .07       0   304.6     .13       0
   469.9     .07       0  1656.3     .13       0  2951.7     .07       0
  3202.1     .13       0  4917.4     .04       0  5088.2     .13       0
    5895     .07       0  7057.1     .13       0  7312.9     .07       0
    9096     .13       0 10219.6     .07       0
#XS Ineff= 2 , 0
       0    1500      40               0
Permanent Ineff=
       F       F
Bank Sta=4917.4,5088.2
XS Rating Curve= 0 ,0
Exp/Cntr=0.3,0.1

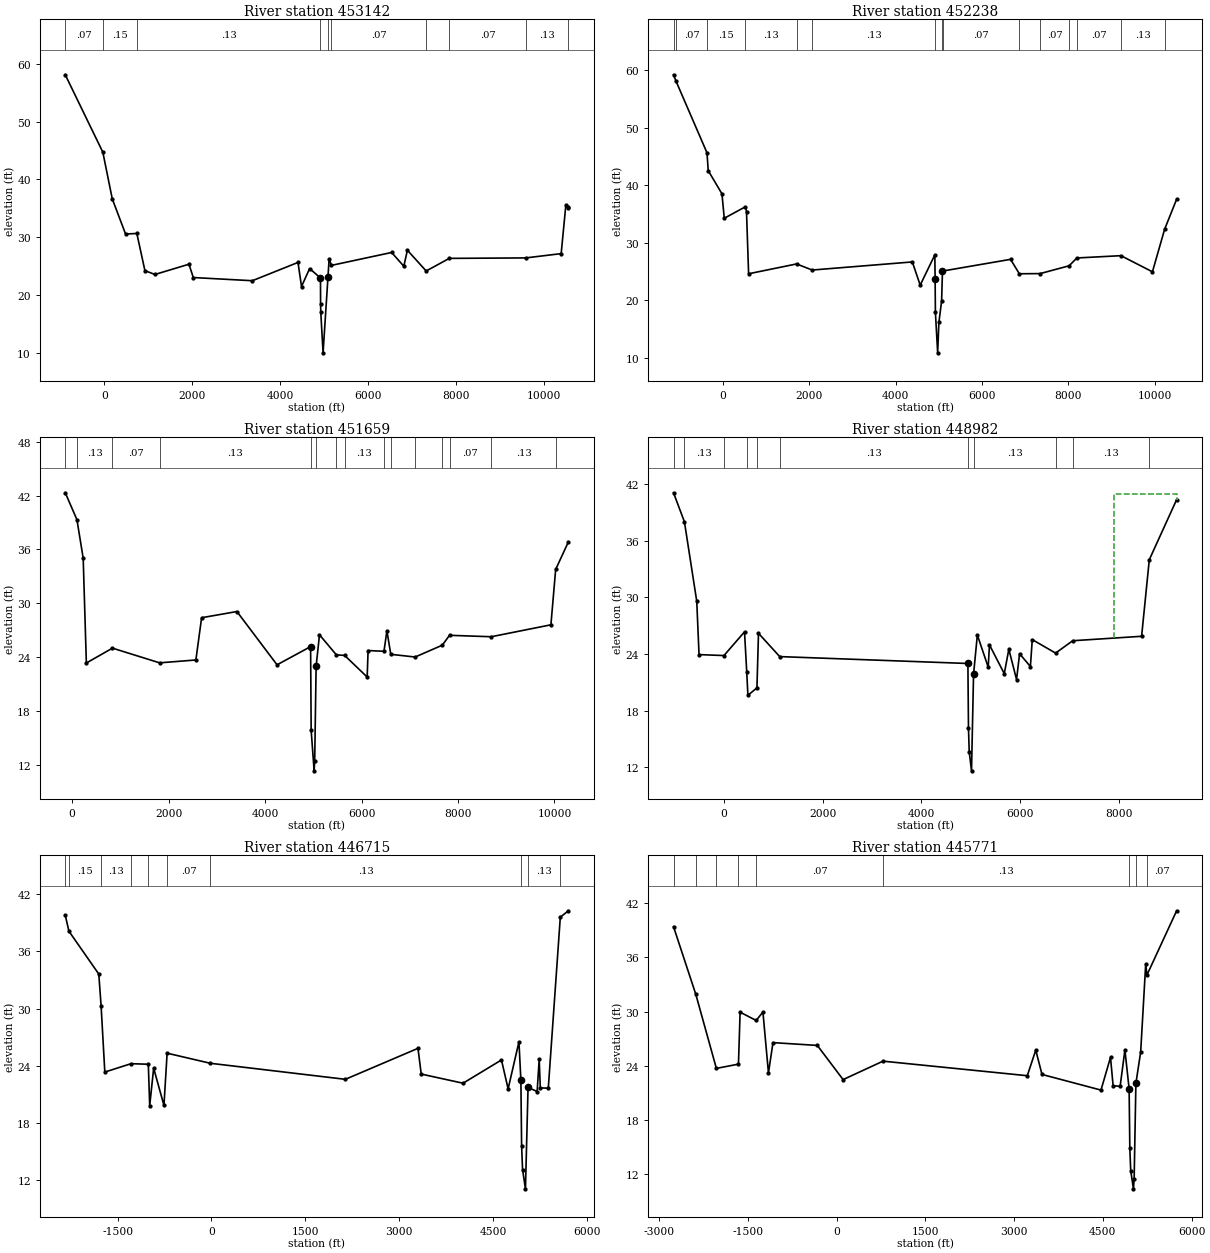
Type RM Length L Ch R = 1 ,453142  ,773,904,580
BEGIN DESCRIPTION:
Waccamaw River 91.0
END DESCRIPTION:
XS GIS Cut Line= 3
        2135725.       106175.01      2132631.73       111184.43
      2128963.72       115357.41
#Sta/Elev= 30
  -887.5   58.09   -33.1   44.72   181.3   36.66   484.2   30.58   740.6   30.67
   924.4   24.25  1151.9   23.59    1926   25.36  2024.7   23.06  3367.4   22.51
  4406.2   25.67  4486.2   21.51  4670.6   24.61  4917.4   22.98  4919.9   18.52
  4924.3   17.08  4976.5   10.05  5088.2   23.16  5114.2   26.28  5167.1   25.16
  6535.7   27.39  6813.1   25.01  6894.2   27.78  7321.5   24.19  7847.6   26.37
    9585   26.45 10392.1   27.19   10498   35.54 10545.8   35.23 10555.9   35.16
#Mann= 10 ,-1 , 0
  -887.5     .07       0   -33.1     .15       0   740.6     .13       0
  4917.4     .04       0  5088.2     .13       0  5167.1     .07       0
  7321.5     .13       0  7847.6     .07       0    9585     .13       0
 10545.8     .07       0
Bank Sta=4917.4,5088.2
XS Rating Curve= 0 ,0
Exp/Cntr=0.3,0.1

Type RM Length L Ch R = 1 ,452238  ,628,579,428
BEGIN DESCRIPTION:
Waccamaw River 90.0
END DESCRIPTION:
XS GIS Cut Line= 3
      2135725.02       106124.98      2131701.22       110993.91
      2128716.77       115419.13
#Sta/Elev= 30
 -1141.9   59.25 -1082.5   58.11  -366.7   45.67  -338.2   42.57     -20   38.53
    33.2   34.28   523.6   36.28   548.5   35.43   597.2   24.62  1708.6   26.33
  2069.8   25.27  4389.8   26.68  4571.9   22.64  4910.9   27.91  4917.4   23.79
  4924.3   17.89  4976.5   10.86  5004.8   16.14    5068   19.87  5088.2   25.17
  5103.7   25.11  6664.9   27.13  6868.1   24.62  7349.5   24.65  8022.1   26.01
  8200.5   27.37  9222.1   27.77  9951.5   24.96 10234.3   32.38 10512.1   37.59
#Mann= 15 ,-1 , 0
 -1141.9     .13       0 -1082.5     .07       0  -366.7     .15       0
   523.6     .13       0  1708.6     .07       0  2069.8     .13       0
  4917.4     .04       0  5088.2     .13       0  5103.7     .07       0
  6868.1     .13       0  7349.5     .07       0  8022.1     .13       0
  8200.5     .07       0  9222.1     .13       0 10234.3     .07       0
Bank Sta=4917.4,5088.2
XS Rating Curve= 0 ,0
Exp/Cntr=0.3,0.1

Type RM Length L Ch R = 1 ,451659  ,783,2677,869
BEGIN DESCRIPTION:
Waccamaw River 88.0
END DESCRIPTION:
XS GIS Cut Line= 3
      2134521.03       106795.06      2131001.41       111055.65
       2128572.7        115316.2
#Sta/Elev= 30
  -142.5   42.32    99.7   39.32   229.1   35.03   294.9   23.34     836      25
  1813.6   23.36  2565.5   23.68  2684.3   28.39    3416   29.08  4248.2   23.14
  4943.8   25.17  4955.6   15.84    5017   11.32  5028.7   12.42  5058.4   22.98
  5128.1   26.49  5477.7   24.25  5648.7   24.19  6116.7   21.78  6135.7   24.73
    6465   24.65  6525.9   26.93  6606.1   24.31  7110.9   24.01  7674.4   25.33
  7823.9   26.43  8689.2   26.27    9926    27.6 10024.4   33.77   10288   36.84
#Mann= 15 ,-1 , 0
  -142.5     .15       0    99.7     .13       0     836     .07       0
  1813.6     .13       0  4943.8     .04       0  5058.4     .13       0
  5477.7     .07       0  5648.7     .13       0    6465     .07       0
  6606.1     .13       0  7110.9     .07       0  7674.4     .13       0
  7823.9     .07       0  8689.2     .13       0 10024.4     .07       0
Bank Sta=4943.8,5058.4
XS Rating Curve= 0 ,0
Exp/Cntr=0.3,0.1

Type RM Length L Ch R = 1 ,448982  ,585,2267,1164
BEGIN DESCRIPTION:
Waccamaw River 86.0
END DESCRIPTION:
XS GIS Cut Line= 3
      2134500.44       106589.26      2130116.37       110808.66
      2128140.45        114410.6
#Sta/Elev= 30
 -1020.1   41.09    -799   38.01  -549.6    29.6  -503.2   23.95     1.6   23.85
     418   26.36   463.5   22.08   486.8   19.64   669.8   20.43   701.3   26.21
  1131.4   23.74  4943.8   23.01  4955.6   16.16  4970.7   13.66    5017   11.64
  5058.4   21.86  5135.2   26.03  5355.3   22.62    5381   24.98  5680.9   21.93
    5773   24.52  5929.4   21.31  5991.1   24.04  6210.1   22.69    6248   25.54
  6720.7   24.11  7067.2   25.42  8463.1   25.89  8618.8      34  9172.9   40.36
#Mann= 11 ,-1 , 0
 -1020.1     .15       0    -799     .13       0     1.6     .07       0
   463.5    .035       0   669.8     .07       0  1131.4     .13       0
  4943.8     .04       0  5058.4     .13       0  6720.7     .07       0
  7067.2     .13       0  8618.8     .07       0
#XS Ineff= 2 , 0
       0                    7900       0      41
Permanent Ineff=
       F       F
Bank Sta=4943.8,5058.4
XS Rating Curve= 0 ,0
Exp/Cntr=0.3,0.1

Type RM Length L Ch R = 1 ,446715  ,634,944,715
BEGIN DESCRIPTION:
Waccamaw River 85.0
END DESCRIPTION:
XS GIS Cut Line= 3
      2134479.86       106342.27      2129046.09       110932.16
      2128305.11       111487.89
#Sta/Elev= 30
 -2336.4   39.79 -2277.9   38.12 -1800.6   33.62   -1764   30.32 -1704.3   23.34
 -1284.9   24.22 -1009.2   24.16  -987.2   19.82  -923.8   23.75  -759.3   19.84
  -708.9   25.32   -16.6   24.26  2139.3   22.58  3299.7   25.83  3351.5   23.13
  4019.7   22.17  4633.5   24.61  4739.9   21.58  4912.9   26.51  4943.8    22.5
  4955.6   15.61  4970.7   13.11    5017   11.09  5058.4   21.73  5203.6    21.3
  5236.6   24.68  5254.2   21.68  5381.8   21.65  5573.8   39.59  5702.7   40.26
#Mann= 10 ,-1 , 0
 -2336.4     .07       0 -2277.9     .15       0   -1764     .13       0
 -1284.9     .07       0 -1009.2    .035       0  -708.9     .07       0
   -16.6     .13       0  4943.8     .04       0  5058.4     .13       0
  5573.8     .07       0
Bank Sta=4943.8,5058.4
XS Rating Curve= 0 ,0
Exp/Cntr=0.3,0.1

Type RM Length L Ch R = 1 ,445771  ,699,847,806
BEGIN DESCRIPTION:
Waccamaw River 84.0
END DESCRIPTION:
XS GIS Cut Line= 3
      2134500.42       106157.04       2128325.7       110499.93
      2127728.81       111240.89
#Sta/Elev= 30
 -2753.8   39.38 -2376.9   31.89 -2029.9   23.71 -1656.6   24.18 -1628.9   29.93
 -1357.7   29.01 -1243.3   29.94 -1149.9   23.21 -1073.4   26.56  -324.4   26.25
   111.3   22.47   785.6   24.51  3223.1    22.9  3366.4   25.73  3471.9   23.04
  4468.5   21.31  4629.3   24.93  4673.5   21.79  4792.1   21.73  4872.6   25.75
  4943.8   21.46  4955.6   14.91  4970.7   12.41    5017   10.39  5028.7   11.49
  5058.4   22.05    5139   25.53  5224.3   35.26  5244.6   34.03  5746.7   41.14
#Mann= 9 ,-1 , 0
 -2753.8     .07       0 -2376.9     .15       0 -2029.9     .13       0
 -1656.6    .035       0 -1357.7     .07       0   785.6     .13       0
  4943.8     .04       0  5058.4     .13       0  5244.6     .07       0
Bank Sta=4943.8,5058.4
XS Rating Curve= 0 ,0
Exp/Cntr=0.3,0.1

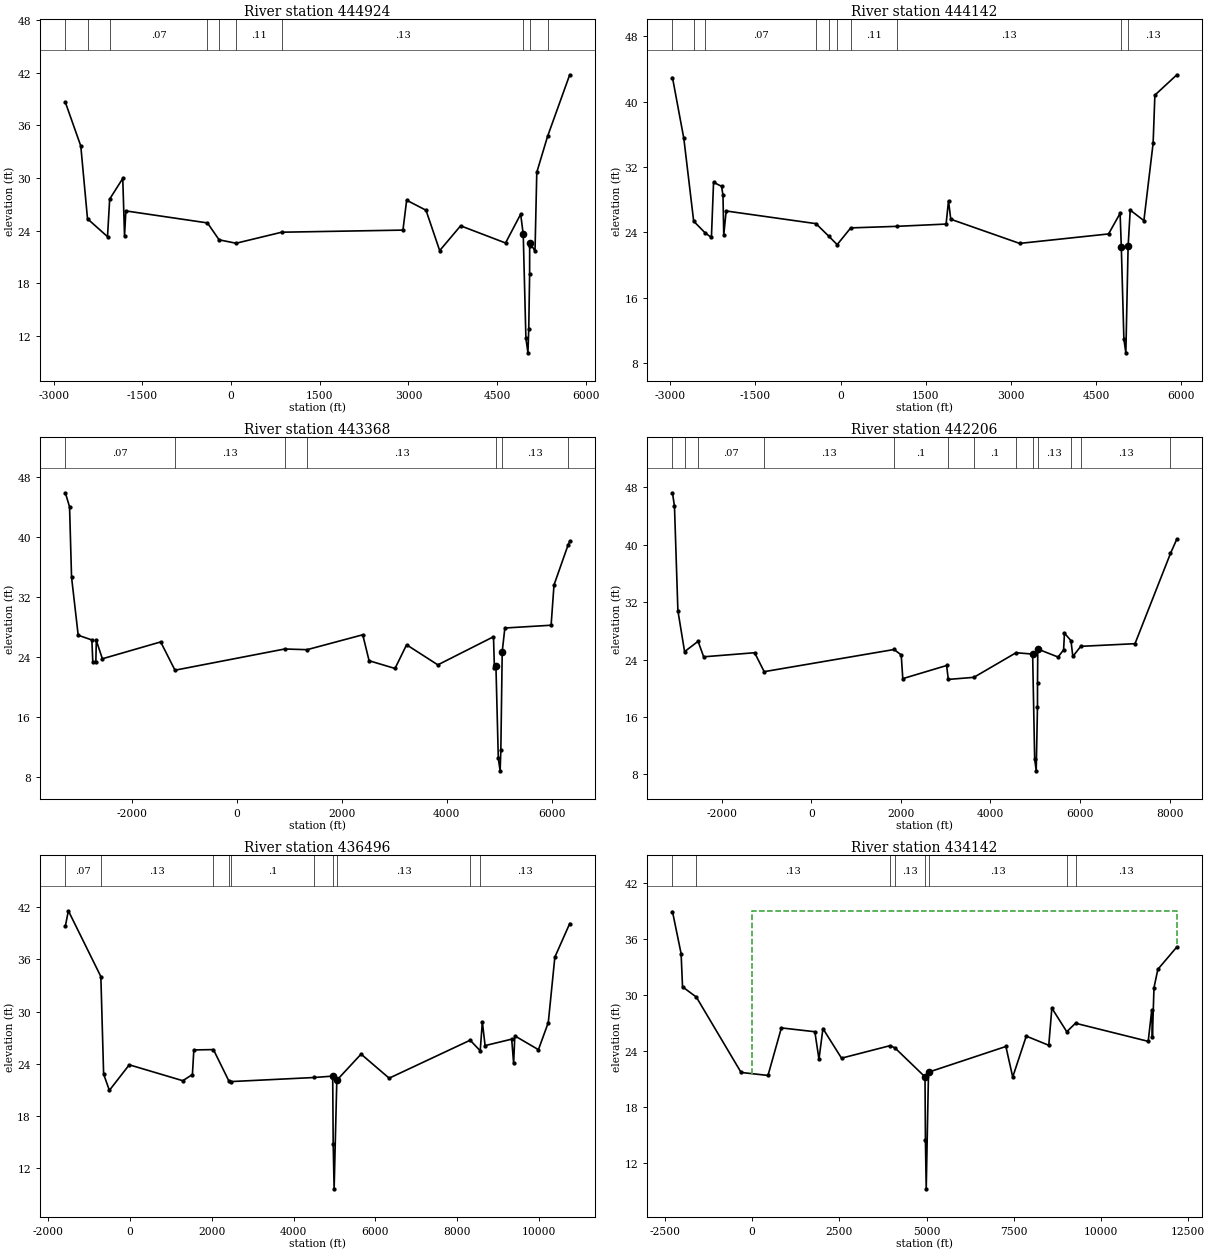
Type RM Length L Ch R = 1 ,444924  ,540,782,735
BEGIN DESCRIPTION:
Waccamaw River 83.0
END DESCRIPTION:
XS GIS Cut Line= 3
      2134088.81       105910.03      2127667.06       110026.53
      2127152.49       110767.52
#Sta/Elev= 30
 -2802.7   38.65 -2541.2   33.65 -2427.6   25.34 -2089.2    23.3 -2052.6   27.59
 -1831.3   29.95 -1801.5   23.39   -1779   26.24  -399.2   24.87  -202.1   22.94
    85.5   22.55   856.9   23.81  2906.8   24.05  2969.6   27.46  3296.6   26.32
  3528.2   21.71  3882.2   24.54    4642   22.58  4897.7   25.87  4941.1   23.58
  4986.2   11.71  5020.8   10.04  5034.4   12.77  5049.1   18.99  5049.9   22.26
  5060.8   22.56  5140.2   21.64  5170.3   30.65  5352.8   34.75  5727.3   41.78
#Mann= 10 ,-1 , 0
 -2802.7     .07       0 -2427.6     .15       0 -2052.6     .07       0
  -399.2     .13       0  -202.1     .07       0    85.5     .11       0
   856.9     .13       0  4941.1     .04       0  5060.8     .13       0
  5352.8     .07       0
Bank Sta=4941.1,5060.8
XS Rating Curve= 0 ,0
Exp/Cntr=0.3,0.1

Type RM Length L Ch R = 1 ,444142  ,695,774,719
BEGIN DESCRIPTION:
Waccamaw River 82.0
END DESCRIPTION:
XS GIS Cut Line= 3
      2134027.03       105745.39      2127063.98       109603.14
      2126637.92       110417.64
#Sta/Elev= 30
 -2960.3   42.94 -2760.5   35.48 -2587.2   25.35 -2382.8    23.9 -2274.7   23.36
 -2237.4   30.11 -2095.9   29.62 -2071.2   28.51 -2057.7   23.66 -2015.4    26.6
  -434.1   25.05  -204.1   23.48   -61.1   22.48   177.5   24.53     989   24.72
  1856.7      25  1898.9   27.86  1938.4   25.59  3150.7   22.63  4716.4   23.79
  4919.7   26.31  4941.1   22.17  4986.2    10.9  5020.8    9.23  5060.8   22.26
  5097.7   26.71  5338.4   25.42    5501    34.9    5532   40.79  5919.2   43.28
#Mann= 10 ,-1 , 0
 -2960.3     .07       0 -2587.2     .15       0 -2382.8     .07       0
  -434.1     .13       0  -204.1     .07       0   -61.1     .13       0
   177.5     .11       0     989     .13       0  4941.1     .04       0
  5060.8     .13       0
Bank Sta=4941.1,5060.8
XS Rating Curve= 0 ,0
Exp/Cntr=0.3,0.1

Type RM Length L Ch R = 1 ,443368  ,731,1162,859
BEGIN DESCRIPTION:
Waccamaw River 81.0
END DESCRIPTION:
XS GIS Cut Line= 3
      2134024.98       105625.01      2126637.94       108812.17
      2126074.99       110275.02
#Sta/Elev= 30
 -3265.5   45.85 -3184.9   43.98 -3146.8   34.63 -3020.2   26.91 -2759.6   26.28
 -2741.4    23.3 -2684.3    23.3 -2674.8   26.21 -2559.4   23.78 -1448.2   26.02
 -1175.7   22.26   914.9   25.08  1342.1   24.99  2402.7   26.97  2523.6   23.52
  3017.7   22.49  3238.1   25.64  3833.9   22.97  4894.5   26.71  4911.7    22.6
  4941.1   22.76  4986.2   10.55  5020.8    8.88  5034.4   11.61  5060.8   24.72
  5110.9   27.87  5992.5   28.24  6047.5   33.59  6318.5   38.96  6347.2    39.4
#Mann= 7 ,-1 , 0
 -3265.5     .07       0 -1175.7     .13       0   914.9     .11       0
  1342.1     .13       0  4941.1     .04       0  5060.8     .13       0
  6318.5     .07       0
Bank Sta=4941.1,5060.8
XS Rating Curve= 0 ,0
Exp/Cntr=0.3,0.1

Type RM Length L Ch R = 1 ,442206  ,2444,5710,313
BEGIN DESCRIPTION:
Waccamaw River 80.0
END DESCRIPTION:
XS GIS Cut Line= 3
      2133975.03       105574.99      2126082.22       107968.29
      2125217.76       110849.83
#Sta/Elev= 30
 -3096.1   47.26 -3051.5   45.36 -2975.4   30.84   -2826   25.12 -2525.1   26.56
 -2400.1    24.4 -1263.1   24.97 -1049.6   22.33  1849.6   25.42  2008.5   24.66
  2043.4   21.36  3021.4   23.19  3058.8   21.25  3629.6   21.54  4571.4   24.97
  4941.1   24.78  4986.2   10.18  5020.8    8.51  5049.1   17.46  5049.9   20.73
    5056   25.48  5508.9   24.37  5632.1   25.37  5651.3    27.7  5796.4   26.65
  5838.1   24.45  6015.3   25.86  7225.5   26.23  8017.4   38.81    8160   40.82
#Mann= 13 ,-1 , 0
 -3096.1     .07       0   -2826     .13       0 -2525.1     .07       0
 -1049.6     .13       0  1849.6      .1       0  3058.8     .13       0
  3629.6      .1       0  4571.4     .13       0  4941.1     .04       0
    5056     .13       0  5796.4     .14       0  6015.3     .13       0
  8017.4     .07       0
Bank Sta=4941.1,5056
XS Rating Curve= 0 ,0
Exp/Cntr=0.3,0.1

Type RM Length L Ch R = 1 ,436496  ,1700,2354,799
BEGIN DESCRIPTION:
Waccamaw River 75.0
END DESCRIPTION:
XS GIS Cut Line= 3
      2132809.25       102168.47      2126379.98        106430.3
      2124967.49       110813.91
#Sta/Elev= 30
 -1574.4   39.81 -1500.4    41.6  -706.6   34.03  -639.1   22.81  -498.3   20.94
   -12.9   23.88  1294.2   22.05  1529.7   22.76  1564.4   25.59    2043   25.63
  2414.7   22.07    2473   21.95  4509.1   22.42  4955.8   22.58  4967.8    14.8
  4990.6    9.61  5056.3    22.1    5649   25.11  6334.6   22.34  8313.4   26.71
  8558.6   25.49  8610.5    28.8  8677.9   26.09  9327.2   26.83    9375   24.04
  9403.5   27.21  9980.5   25.62 10221.2   28.74 10381.5   36.27 10744.7   40.13
#Mann= 10 ,-1 , 0
 -1574.4     .07       0  -706.6     .13       0    2043      .1       0
  2414.7     .13       0    2473      .1       0  4509.1     .13       0
  4955.8     .04       0  5056.3     .13       0  8313.4     .14       0
  8558.6     .13       0
Bank Sta=4955.8,5056.3
XS Rating Curve= 0 ,0
Exp/Cntr=0.3,0.1

Type RM Length L Ch R = 1 ,434142  ,1077,1248,803
BEGIN DESCRIPTION:
Waccamaw River 73.0
END DESCRIPTION:
XS GIS Cut Line= 3
      2132103.06         99416.5      2126909.02       104520.09
      2123847.21       111008.77
#Sta/Elev= 30
 -2281.8   38.91 -2034.4   34.41 -1994.1   30.86 -1597.8   29.76  -315.3   21.69
   455.8   21.37     839   26.46  1798.6   26.05  1916.8   23.11  2030.3   26.39
    2563   23.22    3955   24.56  4093.6   24.32  4955.8   21.22  4967.8   14.42
  4990.6    9.23  5056.3   21.72  7273.8   24.47  7469.5    21.2  7858.4   25.58
  8502.9    24.6  8591.3   28.58  9018.6   26.05  9269.2   26.96 11352.9   25.02
 11455.7    28.4 11473.5   25.46 11518.6   30.76 11629.3   32.73 12174.8   35.13
#Mann= 8 ,-1 , 0
 -2281.8     .07       0 -1597.8     .13       0    3955      .1       0
  4093.6     .13       0  4955.8     .04       0  5056.3     .13       0
  9018.6     .14       0  9269.2     .13       0
#XS Ineff= 2 , 0
       0   -1200      39               0
Permanent Ineff=
       F       F
Bank Sta=4955.8,5056.3
XS Rating Curve= 0 ,0
Exp/Cntr=0.3,0.1

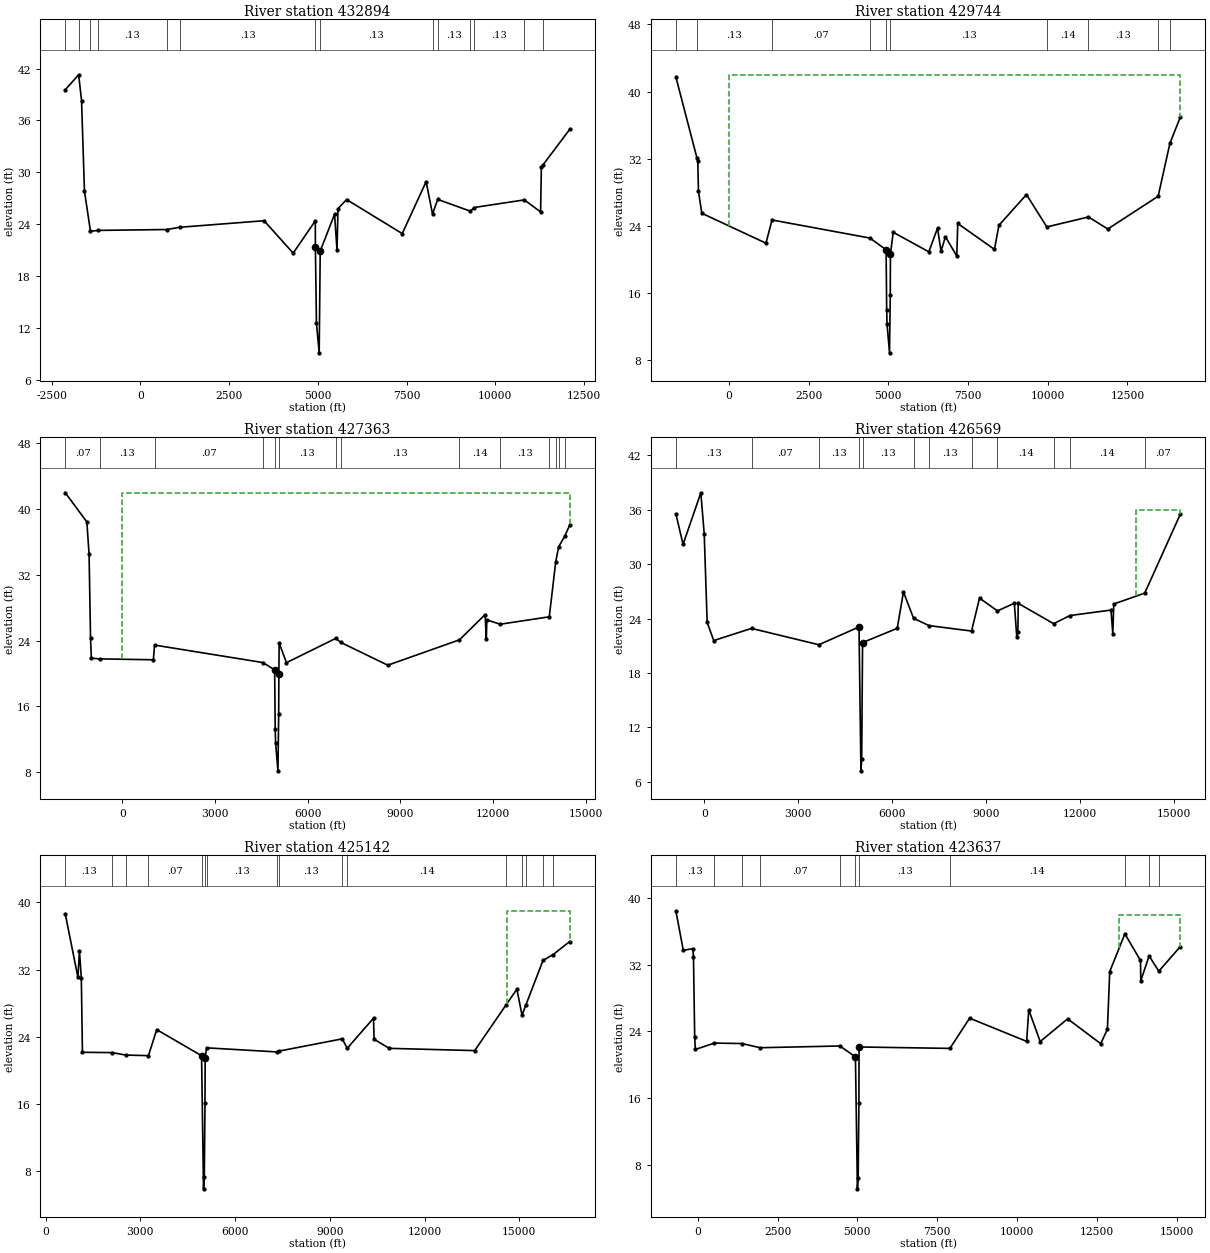
Type RM Length L Ch R = 1 ,432894  ,1548,3150,1145
BEGIN DESCRIPTION:
Waccamaw River 72.0
END DESCRIPTION:
XS GIS Cut Line= 3
      2130349.61        98905.08      2125844.21       104701.21
      2123433.23       111130.48
#Sta/Elev= 30
 -2114.5   39.56   -1739   41.28 -1656.8   38.28 -1575.7   27.82 -1405.9   23.17
   -1191   23.27   739.1   23.37  1103.1   23.63  3484.8   24.39  4304.5   20.64
  4928.6   24.38  4930.4   21.39  4960.4   12.52  5037.3     9.1  5066.7   20.88
  5470.5   25.14  5539.2      21  5567.7   25.79  5809.3   26.84  7376.8    22.9
    8050   28.91  8230.5   25.17  8375.7   26.86  9298.3   25.49  9402.3   25.92
 10817.1    26.8 11275.2   25.41 11296.5   30.58 11342.1   30.85 12093.2   34.95
#Mann= 14 ,-1 , 0
 -2114.5     .07       0   -1739     .13       0 -1405.9     .07       0
   -1191     .13       0   739.1     .07       0  1103.1     .13       0
  4930.4     .04       0  5066.7     .13       0  8230.5     .14       0
  8375.7     .13       0  9298.3     .14       0  9402.3     .13       0
 10817.1     .13       0 11342.1     .07       0
Bank Sta=4930.4,5066.7
XS Rating Curve= 0 ,0
Exp/Cntr=0.3,0.1

Type RM Length L Ch R = 1 ,429744  ,1107,2381,974
BEGIN DESCRIPTION:
Waccamaw River 69.0
END DESCRIPTION:
XS GIS Cut Line= 3
      2129302.36        96981.23      2125625.03       102801.65
      2122142.49        111033.1
#Sta/Elev= 30
 -1665.2   41.73 -1007.1   32.12  -977.7   31.69  -957.1   28.12  -852.2   25.48
  1161.6   21.91  1350.6   24.68  4425.8   22.52  4930.4   21.12  4948.1   13.98
  4960.4   12.25  5037.3    8.83  5060.7   15.73  5066.7   20.61  5152.9   23.21
    6271   20.88  6543.6    23.7  6653.5   20.95  6791.3   22.68  7148.1   20.38
  7178.1   24.26  8329.7   21.17  8469.9   24.04  9334.3   27.71  9973.2   23.85
 11280.3   25.04 11884.8    23.6 13465.9   27.51 13834.3   33.82 14157.4   36.92
#Mann= 10 ,-1 , 0
 -1665.2     .07       0 -1007.1     .13       0  1350.6     .07       0
  4425.8     .13       0  4930.4     .04       0  5066.7     .13       0
  9973.2     .14       0 11280.3     .13       0 13465.9     .14       0
 13834.3     .07       0
#XS Ineff= 2 , 0
       0    -500      42               0
Permanent Ineff=
       F       F
Bank Sta=4930.4,5066.7
XS Rating Curve= 0 ,0
Exp/Cntr=0.3,0.1

Type RM Length L Ch R = 1 ,427363  ,657,794,708
BEGIN DESCRIPTION:
Waccamaw River 67.0
END DESCRIPTION:
XS GIS Cut Line= 3
       2128474.4        96421.03      2124626.54       102265.87
      2121460.59       111033.13
#Sta/Elev= 30
 -1843.2      42 -1146.3   38.45 -1074.4    34.5 -1027.2   24.28 -1000.4   21.86
  -730.5   21.78  1005.3   21.67  1045.2   23.46  4552.9   21.33  4930.4   20.44
  4948.1    13.3  4960.4   11.57  5037.3    8.15  5060.7   15.05  5066.7   19.93
    5076    23.7  5313.1   21.32  6911.7   24.28  7065.7   23.79  8591.6   21.01
 10911.3    24.1 11742.2   27.18 11779.5   24.16 11795.9   26.52 12230.1      26
 13817.1    26.9 14025.6   33.59 14121.4   35.44 14313.5   36.68 14475.9   38.04
#Mann= 14 ,-1 , 0
 -1843.2     .07       0  -730.5     .13       0  1045.2     .07       0
  4552.9     .13       0  4930.4     .04       0  5066.7     .13       0
  6911.7     .07       0  7065.7     .13       0 10911.3     .14       0
 12230.1     .13       0 13817.1     .14       0 14025.6     .07       0
 14121.4     .14       0 14313.5     .07       0
#XS Ineff= 2 , 0
       0    -100      42               0
Permanent Ineff=
       F       F
Bank Sta=4930.4,5066.7
XS Rating Curve= 0 ,0
Exp/Cntr=0.3,0.1

Type RM Length L Ch R = 1 ,426569  ,730,1427,551
BEGIN DESCRIPTION:
Waccamaw River 66.0
END DESCRIPTION:
XS GIS Cut Line= 3
      2127037.52        97151.67      2124115.12       102022.34
      2120242.94       111714.97
#Sta/Elev= 30
  -912.2   35.54  -682.7   32.17  -114.3   37.86    -6.3   33.32    87.6   23.57
   297.8   21.57  1505.3   22.91  3657.5   21.11  4940.5   23.07    5002    7.21
  5026.2    8.57  5054.2   21.35  6161.9   22.92  6361.1   26.93  6684.1   24.02
  7177.4   23.22  8536.9   22.62  8792.2   26.25  9365.9   24.84  9904.3   25.68
  9982.2   21.98 10017.9   22.54 10028.7   25.67 11160.6   23.43 11681.8   24.33
 12993.9   24.93 13051.7   22.34 13082.4    25.6 14072.3    26.8 15205.4   35.47
#Mann= 12 ,-1 , 0
  -912.2     .13       0  1505.3     .07       0  3657.5     .13       0
  4940.5     .04       0  5054.2     .13       0  6684.1     .07       0
  7177.4     .13       0  8536.9     .12       0  9365.9     .14       0
 11160.6     .13       0 11681.8     .14       0 14072.3     .07       0
#XS Ineff= 2 , 0
       0                   13800       0      36
Permanent Ineff=
       F       F
Bank Sta=4940.5,5054.2
XS Rating Curve= 0 ,0
Exp/Cntr=0.3,0.1

Type RM Length L Ch R = 1 ,425142  ,387,1505,612
BEGIN DESCRIPTION:
Waccamaw River 65.0
END DESCRIPTION:
XS GIS Cut Line= 3
      2126185.15        97419.57      2123783.19       101075.28
      2119780.21       111958.55
#Sta/Elev= 30
   625.8   38.59  1024.5   31.08    1074   34.19  1132.7   30.97  1167.9   22.14
  2117.2    22.1  2535.4   21.81  3258.4   21.74  3520.7   24.84  4940.5   21.73
    5002    5.87  5026.2    7.23  5048.9   16.14  5054.2   21.46  5098.8   22.67
  7338.6   22.18  7406.4   22.29  9393.9   23.74  9553.5   22.62 10384.9    26.2
 10404.6   23.69 10883.2   22.61 13589.6   22.34 14570.5   27.72 14924.9   29.66
 15088.8   26.55 15213.9   27.81 15751.8   33.08 16075.8   33.79 16596.1   35.33
#Mann= 16 ,-1 , 0
   625.8     .13       0  2117.2     .07       0  2535.4     .13       0
  3258.4     .07       0  4940.5     .04       0  5054.2     .07       0
  5098.8     .13       0  7338.6     .07       0  7406.4     .13       0
  9393.9     .12       0  9553.5     .14       0 14570.5     .07       0
 15088.8     .14       0 15213.9     .07       0 15751.8     .14       0
 16075.8     .07       0
#XS Ineff= 2 , 0
       0                   14600       0      39
Permanent Ineff=
       F       F
Bank Sta=4940.5,5054.2
XS Rating Curve= 0 ,0
Exp/Cntr=0.3,0.1

Type RM Length L Ch R = 1 ,423637  ,598,1352,1578
BEGIN DESCRIPTION:
Waccamaw River 63.0
END DESCRIPTION:
XS GIS Cut Line= 4
      2126112.08        97395.22      2123165.34       101072.56
      2122653.92       102679.88      2118976.56       111325.33
#Sta/Elev= 30
  -682.8   38.48    -451   33.73  -152.6   33.93  -131.7   32.97   -93.5    23.3
   -73.5   21.82     525   22.59  1393.5   22.53  1953.4   22.03  4452.2   22.24
  4940.5   20.94    5002    5.08  5026.2    6.44  5048.9   15.35  5054.2   22.12
  7900.1   21.95  8516.3   25.58 10302.8   22.79 10368.1   26.59 10726.3   22.77
   11586    25.5 12621.1   22.52 12831.2   24.24   12905   31.18 13378.8   35.71
 13867.6   32.51 13877.4   30.09 14138.5   33.06 14440.6   31.22 15111.3   34.16
#Mann= 11 ,-1 , 0
  -682.8     .13       0     525     .07       0  1393.5     .13       0
  1953.4     .07       0  4452.2     .13       0  4940.5     .04       0
  5054.2     .13       0  7900.1     .14       0 13378.8     .07       0
 14138.5     .14       0 14440.6     .07       0
#XS Ineff= 2 , 0
       0                   13200       0      38
Permanent Ineff=
       F       F
Bank Sta=4940.5,5054.2
XS Rating Curve= 0 ,0
Exp/Cntr=0.3,0.1