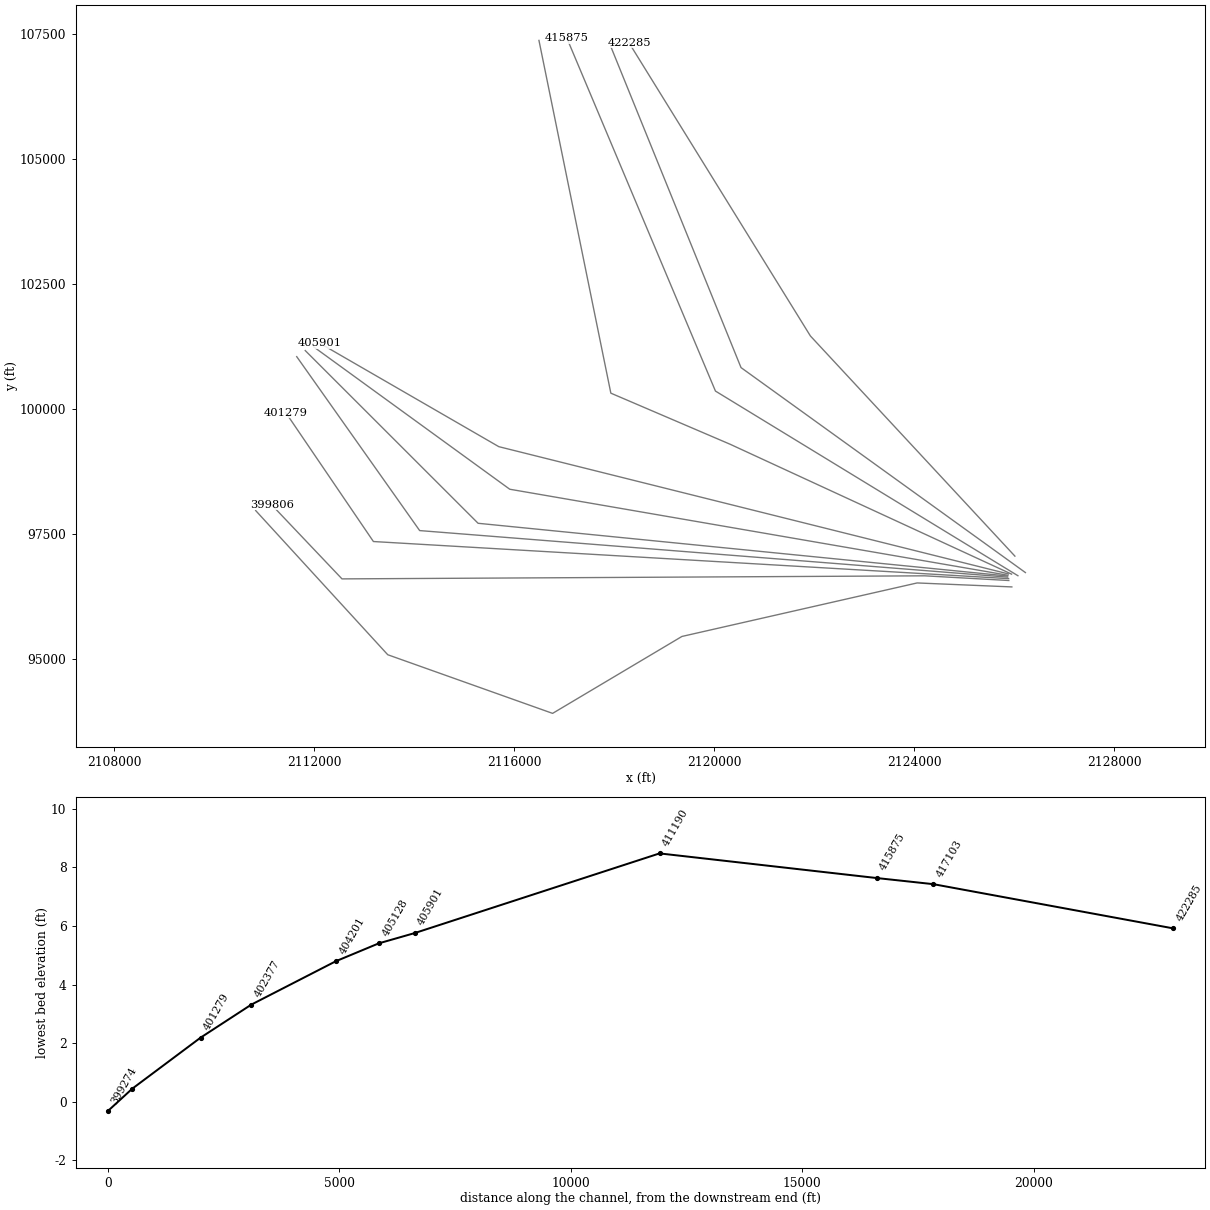
HEC-RAS study Waccamaw River.prj: Waccamaw River Detailed Study

--- Waccamaw River.g01 (geometry) --- (continued)

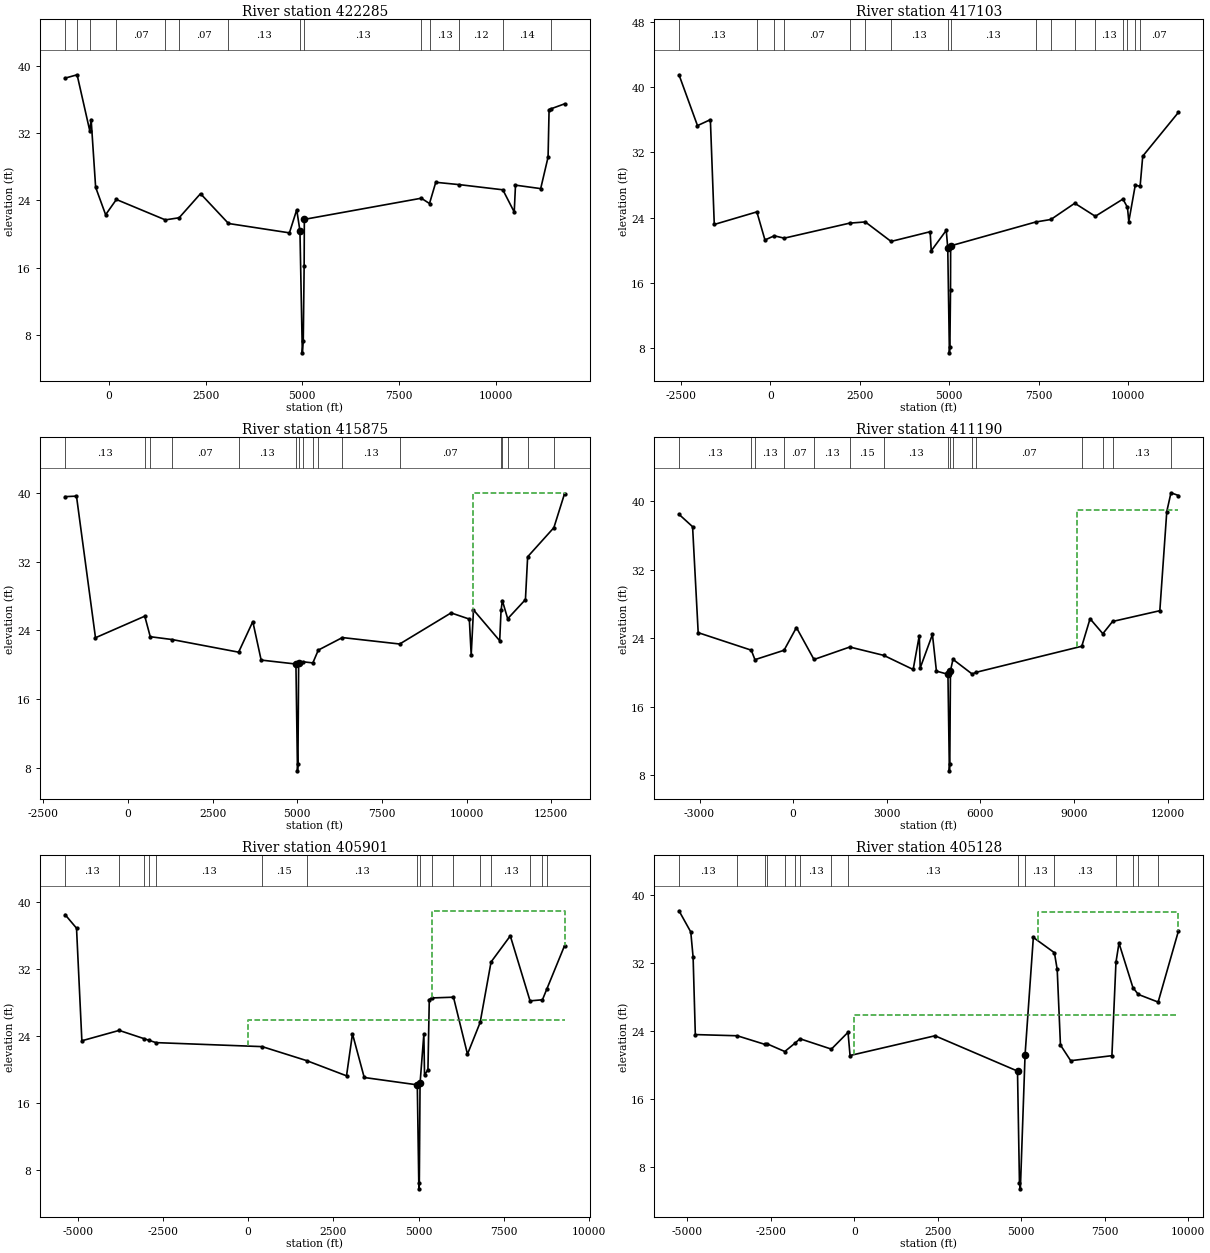
Type RM Length L Ch R = 1 ,422285  ,1077,5182,1054
BEGIN DESCRIPTION:
Waccamaw River 62.0
END DESCRIPTION:
XS GIS Cut Line= 3
      2126014.67        97054.27      2121923.32       101462.21
      2118294.65       107331.39
#Sta/Elev= 30
 -1132.1   38.52  -821.2   38.92  -494.5   32.29  -458.4   33.61  -342.1   25.57
   -83.7   22.31     194   24.12  1459.6    21.7  1816.8   21.95  2369.6   24.81
  3092.9   21.27  4668.5   20.16  4857.2    22.9  4940.5    20.4    5002    5.92
  5026.2    7.28  5048.9   16.19  5054.2   21.76  8077.9   24.27  8290.2   23.64
  8452.4   26.16  9065.8   25.88 10186.2   25.27 10480.9   22.63 10513.6   25.82
 11164.9   25.41 11355.9   29.15   11382   34.78 11442.1    34.9 11782.3   35.47
#Mann= 14 ,-1 , 0
 -1132.1     .13       0  -821.2     .07       0  -494.5     .13       0
     194     .07       0  1459.6     .13       0  1816.8     .07       0
  3092.9     .13       0  4940.5     .04       0  5054.2     .13       0
  8077.9     .07       0  8290.2     .13       0  9065.8     .12       0
 10186.2     .14       0 11442.1     .07       0
Bank Sta=4940.5,5054.2
XS Rating Curve= 0 ,0
Exp/Cntr=0.3,0.1

Type RM Length L Ch R = 1 ,417103  ,614,1228,691
BEGIN DESCRIPTION:
Waccamaw River 59.0
END DESCRIPTION:
XS GIS Cut Line= 3
      2126225.03        96724.98      2120535.18       100829.02
      2117929.37       107258.29
#Sta/Elev= 30
 -2548.3    41.5 -2031.7   35.27 -1671.7      36 -1562.6   23.16  -373.1    24.7
  -146.8   21.26   114.1   21.77     391   21.48  2216.3   23.32  2655.7   23.47
  3375.8   21.08  4467.2   22.27  4498.5   19.93  4917.6   22.44  4959.5   20.29
  5005.4    7.43    5019    8.18  5036.8   15.19  5040.2   20.54  7415.2   23.46
  7840.3   23.77  8507.6   25.76  9081.1   24.16  9853.2   26.27  9979.5   25.25
 10016.9   23.52 10197.3   27.97 10332.8   27.84 10406.2   31.53 11404.5    36.9
#Mann= 17 ,-1 , 0
 -2548.3     .13       0  -373.1     .07       0   114.1     .13       0
     391     .07       0  2216.3     .13       0  2655.7     .07       0
  3375.8     .13       0  4959.5     .04       0  5040.2     .13       0
  7415.2     .07       0  7840.3     .13       0  8507.6     .07       0
  9081.1     .13       0  9853.2     .07       0  9979.5     .14       0
 10197.3    .035       0 10332.8     .07       0
Bank Sta=4959.5,5040.2
XS Rating Curve= 0 ,0
Exp/Cntr=0.3,0.1

Type RM Length L Ch R = 1 ,415875  ,827,4685,1527
BEGIN DESCRIPTION:
Waccamaw River 57.0
END DESCRIPTION:
XS GIS Cut Line= 3
        2126075.        96661.85      2120023.76       100358.99
      2117052.64       107421.49
#Sta/Elev= 30
 -1859.1   39.55 -1522.2   39.61  -960.9   23.13   494.9   25.64   656.7   23.25
  1301.6   22.92    3267   21.45  3685.9   25.01  3932.2   20.53  4959.5   20.07
  5005.4    7.64    5019    8.39  5040.2   20.24  5173.9   20.33  5459.1    20.2
    5620   21.69  6331.6   23.15  8024.4    22.4  9542.2   26.02   10081    25.3
 10136.3   21.12 10204.1   26.37 10978.3   22.78 11018.2    26.3 11056.7   27.46
 11214.1   25.34 11738.6   27.57 11803.5   32.55 12578.4   35.94 12894.2    39.9
#Mann= 17 ,-1 , 0
 -1859.1     .13       0   494.9     .07       0   656.7     .13       0
  1301.6     .07       0    3267     .13       0  4959.5     .04       0
  5040.2     .13       0  5173.9     .07       0  5459.1     .13       0
    5620     .07       0  6331.6     .13       0  8024.4     .07       0
 11018.2    .035       0 11056.7     .07       0 11214.1     .13       0
 11803.5     .07       0 12578.4     .13       0
#XS Ineff= 2 , 0
       0                   10200       0      40
Permanent Ineff=
       F       F
Bank Sta=4959.5,5040.2
XS Rating Curve= 0 ,0
Exp/Cntr=0.3,0.1

Type RM Length L Ch R = 1 ,411190  ,1609,5289,3855
BEGIN DESCRIPTION:
Waccamaw River 54.0
END DESCRIPTION:
XS GIS Cut Line= 4
      2125948.27        96693.55        2120316.        99294.76
      2117930.78       100317.12      2116492.52       107380.05
#Sta/Elev= 30
 -3659.6    38.5   -3224   37.05 -3044.3   24.65 -1342.9    22.6 -1225.7   21.49
  -292.8   22.59   103.8   25.25   667.1   21.51  1814.2   22.97  2904.3   21.99
    3845   20.34  4041.1   24.31  4070.7   20.52  4462.7   24.44  4590.2   20.15
  4959.5   19.78  5005.4    8.48    5019    9.23  5040.2   20.18  5120.1   21.53
  5735.6   19.81  5860.9   20.01  9248.6   23.06  9513.9   26.28  9923.7   24.53
 10235.6   25.96 11749.7   27.22 11972.5   38.82 12106.9   41.02 12347.3    40.7
#Mann= 16 ,-1 , 0
 -3659.6     .13       0 -1342.9     .07       0 -1225.7     .13       0
  -292.8     .07       0   667.1     .13       0  1814.2     .15       0
  2904.3     .13       0  4959.5     .04       0  5040.2     .13       0
  5120.1     .07       0  5735.6     .13       0  5860.9     .07       0
  9248.6     .13       0  9923.7     .07       0 10235.6     .13       0
 12106.9     .07       0
#XS Ineff= 2 , 0
       0                    9100       0      39
Permanent Ineff=
       F       F
Bank Sta=4959.5,5040.2
XS Rating Curve= 0 ,0
Exp/Cntr=0.3,0.1

Type RM Length L Ch R = 1 ,405901  ,789,773,507
BEGIN DESCRIPTION:
Waccamaw River 51.0
END DESCRIPTION:
XS GIS Cut Line= 3
      2125885.32        96697.52      2115688.86        99246.06
      2112108.89       101316.11
#Sta/Elev= 30
   -5368   38.54 -5032.4   36.92 -4875.6   23.46 -3781.3    24.7 -3043.2    23.7
 -2904.2   23.51   -2703   23.24   411.8   22.76  1712.6   21.09  2884.3   19.27
  3058.6   24.29  3403.5   19.07  4959.5   18.19  5005.4    5.76    5019    6.51
  5040.2   18.36  5151.5   24.26  5171.6   19.37  5271.7      20  5310.8   28.39
  5383.3   28.58  6020.4   28.67  6430.9   21.86  6802.2   25.65  7122.3   32.88
  7686.4      36  8265.3   28.23  8628.9   28.36  8753.8   29.61  9277.5   34.83
#Mann= 16 ,-1 , 0
   -5368     .13       0 -3781.3     .07       0 -3043.2     .13       0
 -2904.2     .07       0   -2703     .13       0   411.8     .15       0
  1712.6     .13       0  4959.5     .04       0  5040.2     .13       0
  5383.3     .07       0  6020.4     .13       0  6802.2     .07       0
  7122.3     .13       0  8265.3     .07       0  8628.9     .13       0
  8753.8     .07       0
#XS Ineff= 2 , 0
       0   -2800    25.9    5400       0      39
Permanent Ineff=
       F       F
Bank Sta=4959.5,5040.2
XS Rating Curve= 0 ,0
Exp/Cntr=0.3,0.1

Type RM Length L Ch R = 1 ,405128  ,900,927,681
BEGIN DESCRIPTION:
Waccamaw River 50.0
END DESCRIPTION:
XS GIS Cut Line= 3
      2125873.99        96671.23      2115908.04        98393.69
      2111987.13       101243.04
#Sta/Elev= 30
 -5251.3   38.09 -4898.4    35.6 -4828.3   32.63 -4762.2   23.54 -3506.1    23.4
 -2687.9    22.4 -2628.1   22.48 -2082.5   21.55 -1770.3   22.55 -1628.3   23.05
  -686.7   21.83  -188.5   23.81  -127.6   21.08  2416.8    23.4  4887.8   19.25
  4946.5     6.1    4974    5.41  5114.5   21.17  5362.2   34.96  5993.6   33.16
  6076.9   31.19  6174.5   22.31  6480.7   20.47  7715.6   21.06  7836.8   32.04
  7927.5   34.29    8345   29.06  8505.5   28.26  9100.1   27.36  9709.3   35.73
#Mann= 16 ,-1 , 0
 -5251.3     .13       0 -3506.1     .07       0 -2687.9     .13       0
 -2628.1     .07       0 -2082.5     .13       0 -1770.3      .1       0
 -1628.3     .13       0  -686.7      .1       0  -188.5     .13       0
  4887.8     .04       0  5114.5     .13       0  5993.6     .13       0
  7836.8     .07       0    8345     .13       0  8505.5     .07       0
  9100.1     .13       0
#XS Ineff= 2 , 0
       0   -1800    25.8    5500       0      38
Permanent Ineff=
       F       F
Bank Sta=4887.8,5114.5
XS Rating Curve= 0 ,0
Exp/Cntr=0.3,0.1

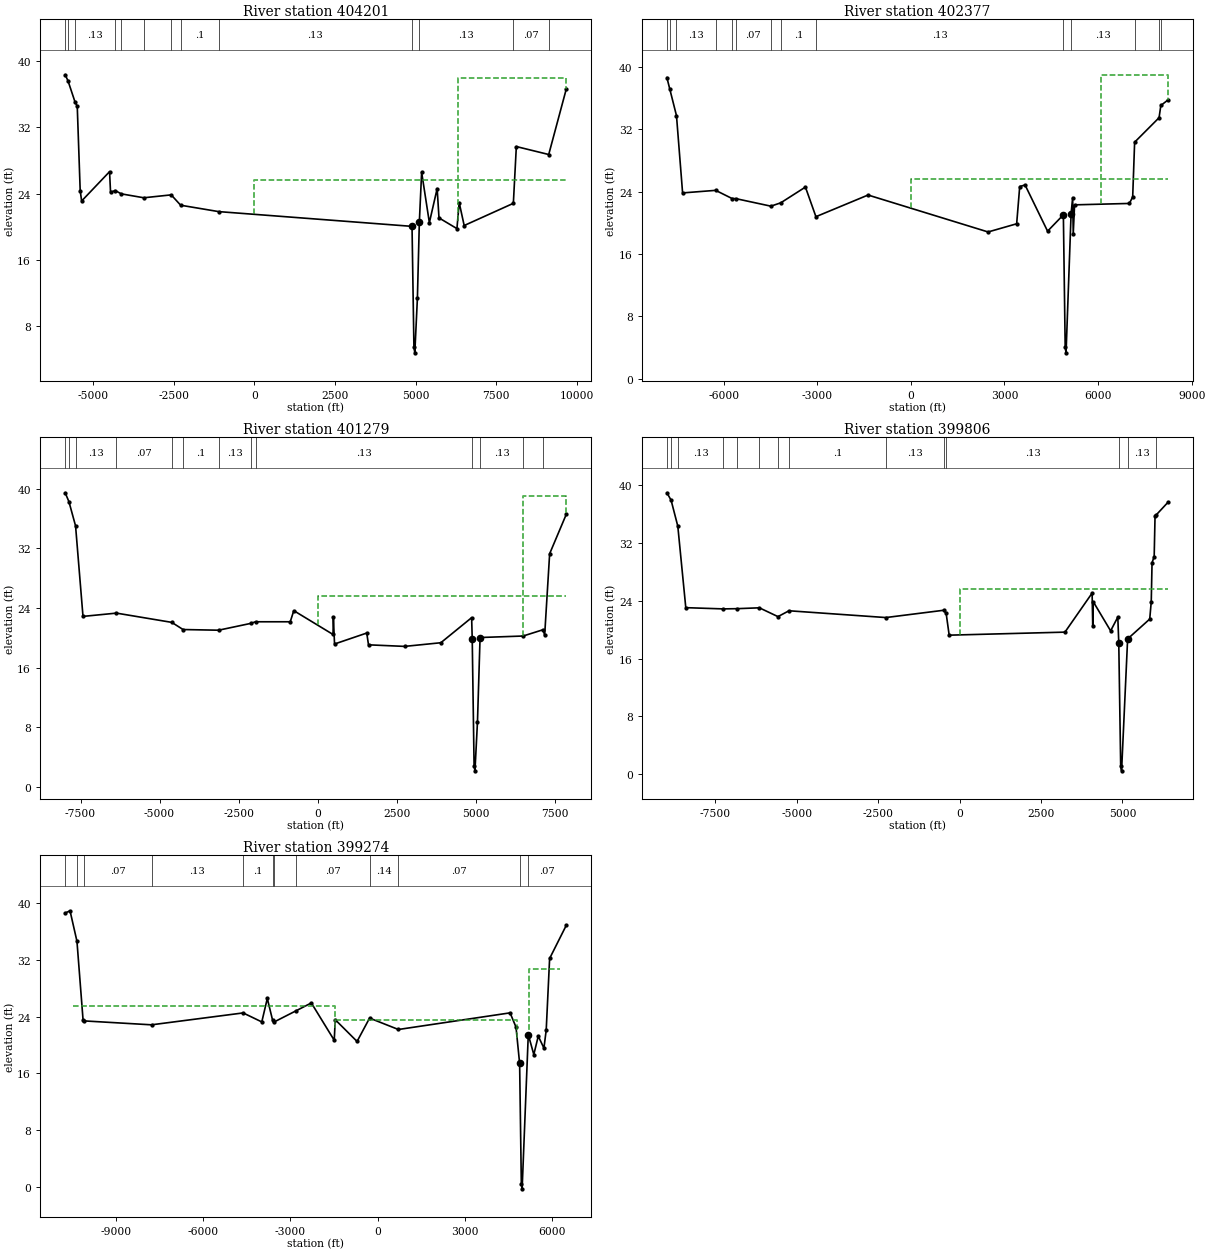
Type RM Length L Ch R = 1 ,404201  ,320,1824,763
BEGIN DESCRIPTION:
Waccamaw River 49.0
END DESCRIPTION:
XS GIS Cut Line= 3
      2125866.47        96656.19      2115274.85        97711.79
      2111816.67       101169.98
#Sta/Elev= 30
 -5863.3   38.35 -5775.5   37.62 -5560.5    35.1 -5488.7   34.55 -5397.6   24.38
 -5352.9   23.12 -4487.3   26.66 -4456.7   24.18 -4312.1   24.38 -4122.1   23.98
 -3425.4   23.51 -2576.7   23.86 -2283.2   22.61 -1104.7   21.84  4887.8   20.06
  4946.5    5.49    4974     4.8  5053.9   11.36  5114.5   20.56  5185.5   26.59
  5425.2   20.51  5666.4   24.62  5723.5   21.08  6279.6   19.79  6349.5   22.93
  6504.2   20.16  8028.3   22.84  8120.7   29.69  9124.4   28.73  9671.4   36.67
#Mann= 13 ,-1 , 0
 -5863.3     .13       0 -5775.5     .07       0 -5560.5     .13       0
 -4312.1     .07       0 -4122.1     .13       0 -3425.4     .07       0
 -2576.7     .13       0 -2283.2      .1       0 -1104.7     .13       0
  4887.8     .04       0  5114.5     .13       0  8028.3     .07       0
  9124.4     .13       0
#XS Ineff= 2 , 0
       0   -1900    25.7    6300       0      38
Permanent Ineff=
       F       F
Bank Sta=4887.8,5114.5
XS Rating Curve= 0 ,0
Exp/Cntr=0.3,0.1

Type RM Length L Ch R = 1 ,402377  ,359,1098,874
BEGIN DESCRIPTION:
Waccamaw River 48.0
END DESCRIPTION:
XS GIS Cut Line= 3
      2125870.22        96633.64      2114105.89        97565.67
      2111646.18       101048.23
#Sta/Elev= 30
 -7820.5   38.64 -7725.2   37.13 -7512.5   33.75 -7316.8   23.84 -6257.7   24.17
 -5730.6   23.12   -5613   23.11 -4487.1   22.14 -4170.6   22.57   -3380   24.59
 -3043.5   20.79 -1372.3   23.57  2474.7   18.83  3390.8   19.88  3488.6   24.66
  3660.2   24.86  4381.8   18.93  4887.8   21.03  4946.5    4.01    4974    3.32
  5135.6   21.19  5185.7   23.24  5204.6   18.62  5246.9   22.31  7003.3   22.49
  7109.7   23.32    7172   30.35  7955.2   33.49  8011.9   35.06  8244.3   35.78
#Mann= 14 ,-1 , 0
 -7820.5     .13       0 -7725.2     .07       0 -7512.5     .13       0
 -6257.7     .07       0 -5730.6     .13       0   -5613     .07       0
 -4487.1     .13       0 -4170.6      .1       0 -3043.5     .13       0
  4887.8     .04       0  5135.6     .13       0    7172     .07       0
  7955.2     .13       0  8011.9     .07       0
#XS Ineff= 2 , 0
       0   -3500    25.6    6100       0      39
Permanent Ineff=
       F       F
Bank Sta=4887.8,5135.6
XS Rating Curve= 0 ,0
Exp/Cntr=0.3,0.1

Type RM Length L Ch R = 1 ,401279  ,708,1473,1163
BEGIN DESCRIPTION:
Waccamaw River 47.0
END DESCRIPTION:
XS GIS Cut Line= 3
      2125889.02        96603.58      2113180.46        97346.49
      2111427.02        99927.94
#Sta/Elev= 30
 -7985.8   39.46 -7866.8   38.27 -7656.9   35.02 -7421.9   22.89 -6362.8   23.33
 -4614.2   22.09 -4257.3   21.13 -3134.5   21.04 -2119.7   21.95 -1964.7   22.17
    -867   22.17  -755.6   23.66     485   20.47     497   22.75   533.2   19.19
    1552   20.66  1607.7   19.08  2750.1   18.87  3894.9   19.36  4869.1   22.72
  4887.8    19.9  4946.5    2.88    4974    2.19  5053.9    8.75  5135.6   20.06
  6496.6   20.26  7131.6   21.11  7178.5   20.36  7336.3   31.29  7865.1    36.6
#Mann= 13 ,-1 , 0
 -7985.8     .13       0 -7866.8     .07       0 -7656.9     .13       0
 -6362.8     .07       0 -4614.2     .13       0 -4257.3      .1       0
 -3134.5     .13       0 -2119.7      .1       0 -1964.7     .13       0
  4887.8     .04       0  5135.6     .13       0  6496.6     .07       0
  7131.6     .13       0
#XS Ineff= 2 , 0
       0   -3500    25.6    6500       0      39
Permanent Ineff=
       F       F
Bank Sta=4887.8,5135.6
XS Rating Curve= 0 ,0
Exp/Cntr=0.3,0.1

Type RM Length L Ch R = 1 ,399806  ,3117,532,440
BEGIN DESCRIPTION:
Waccamaw River 45.0
END DESCRIPTION:
XS GIS Cut Line= 4
      2125892.78          96566.      2124209.17        96659.95
      2112551.88        96598.53      2111146.99         98079.5
#Sta/Elev= 30
 -8983.5   38.98 -8854.7   37.96 -8648.1   34.35 -8403.2   23.06   -7254   22.89
   -6838   22.92 -6144.8   23.04 -5573.8   21.82 -5234.7   22.63 -2262.6   21.69
  -488.1    22.7  -410.8   22.27  -318.3   19.25  3235.7   19.67  4069.5   25.08
  4089.1   20.48  4106.4   23.87  4637.5   19.85  4858.4   21.75  4887.8   18.16
  4946.5    1.14    4974     .45  5159.6   18.73  5838.1   21.48  5884.9   23.89
  5909.1   29.28  5974.8   30.15    6001   35.74  6028.7   35.87  6401.5   37.68
#Mann= 14 ,-1 , 0
 -8983.5     .13       0 -8854.7     .07       0 -8648.1     .13       0
   -7254     .07       0   -6838     .13       0 -6144.8     .07       0
 -5573.8     .13       0 -5234.7      .1       0 -2262.6     .13       0
  -488.1     .15       0  -410.8     .13       0  4887.8     .04       0
  5159.6     .13       0  6028.7     .07       0
#XS Ineff= 2 , 0
       0   -4000    25.6               0
Permanent Ineff=
       F       F
Bank Sta=4887.8,5159.6
XS Rating Curve= 0 ,0
Exp/Cntr=0.5,0.3

Type RM Length L Ch R = 1 ,399274  ,99,131,129
BEGIN DESCRIPTION:
Pireway Road (WR) us
END DESCRIPTION:
XS GIS Cut Line= 6
      2125953.62        96437.73      2124058.57        96517.28
      2119352.62        95445.79      2116765.37        93905.77
      2113467.32        95079.84      2110824.85        97966.65
#Sta/Elev= 30
-10751.3   38.64  -10584   38.96-10345.4   34.65-10136.5    23.6-10087.2    23.4
 -7780.3   22.85 -4627.3   24.53   -3985   23.26 -3795.5   26.57 -3611.9   23.48
 -3575.5   23.22   -2802   24.84   -2280   25.94 -1492.2   20.67 -1456.6   23.57
  -706.3    20.5  -275.8    23.8   715.7   22.19  4559.4   24.54  4763.4   22.52
  4887.8   17.39  4946.5     .37    4974    -.32  5185.5   21.47  5375.6   18.65
  5528.9   21.25    5724   19.56  5802.4    22.1  5919.9   32.22  6496.1   36.93
#Mann= 12 ,-1 , 0
-10751.3     .07       0-10345.4     .13       0-10087.2     .07       0
 -7780.3     .13       0 -4627.3      .1       0 -3611.9     .14       0
 -3575.5      .1       0   -2802     .07       0  -275.8     .14       0
   715.7     .07       0  4887.8     .04       0  5185.5     .07       0
#XS Ineff= 3 ,-1
-10489.2 -1471.8   25.48 -1471.7  4806.7   23.56  5221.6  6262.8   30.73
Permanent Ineff=
       F       F       F
Bank Sta=4887.8,5185.5
XS Rating Curve= 0 ,0
Exp/Cntr=0.5,0.3