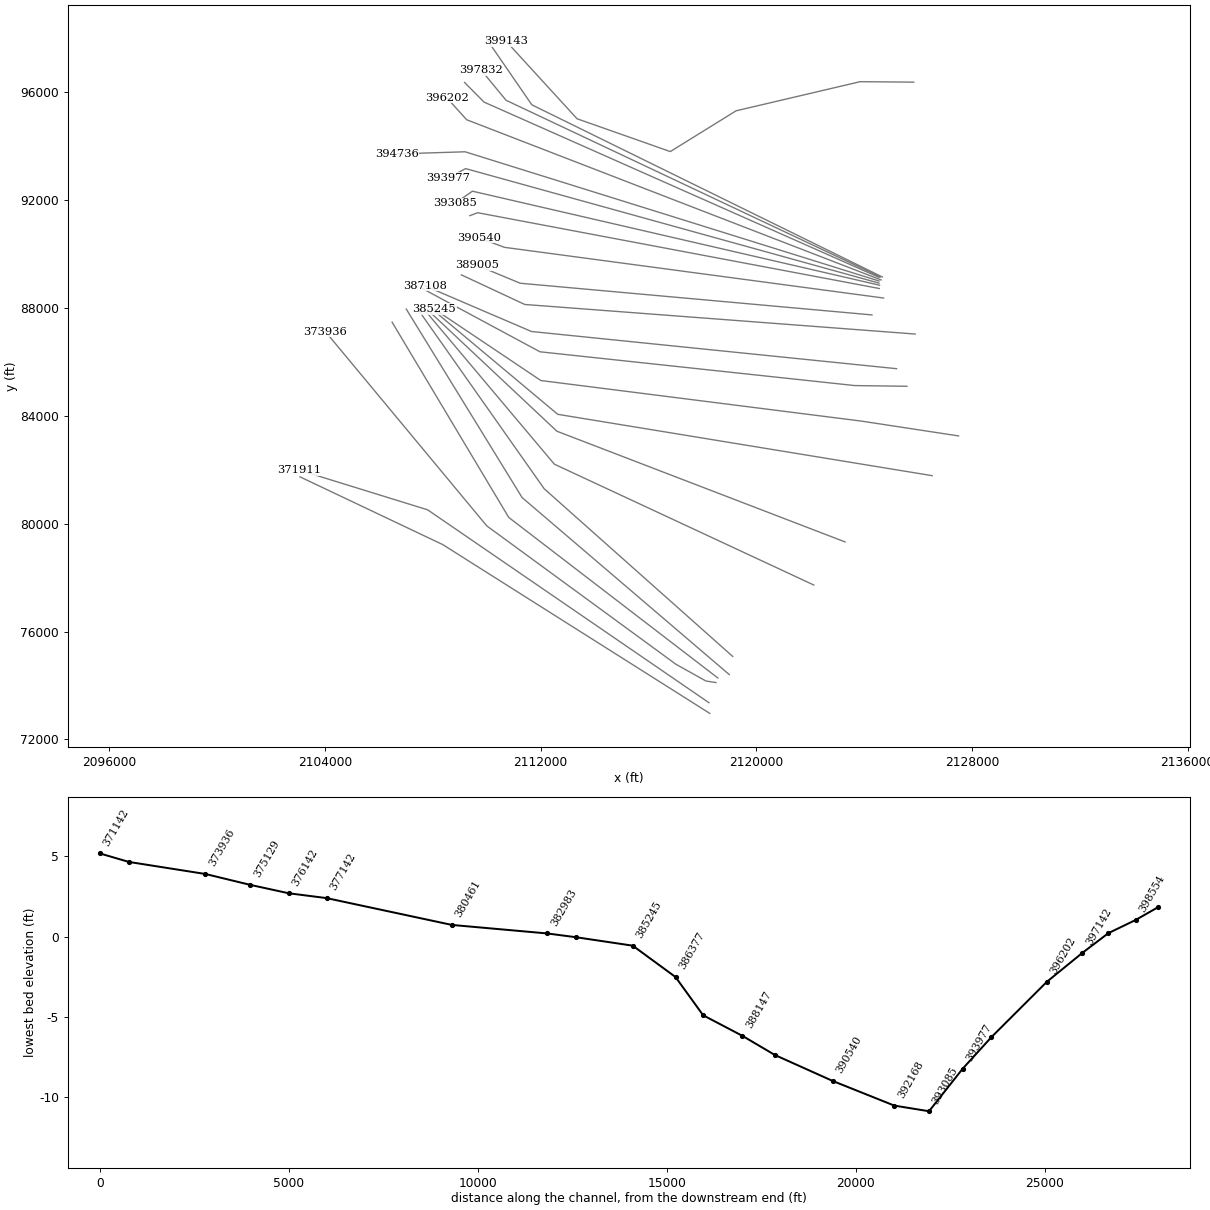
HEC-RAS study Waccamaw River.prj: Waccamaw River Detailed Study

--- Waccamaw River.g01 (geometry) --- (continued)

Type RM Length L Ch R = 3 ,399209  ,,,
BEGIN DESCRIPTION:
Pireway Road (WR) tor
Structure ID: BK_WAC_01
Detailed Survey Structure
END DESCRIPTION:
Bridge Culvert--1,0,-1,-1, 0
Deck Dist Width WeirC Skew NumUp NumDn MinLoCord MaxHiCord MaxSubmerge Is_Ogee
49,32,3,0, 32, 32, , , 0.95, 0, 1,1,,
-10769.3-10239.6-10135.8 -9781.2 -8480.8   -6726 -5884.4 -5440.3   -3549 -1491.3
  -700.6   972.3  2134.4    3635  4259.8  4557.1  4569.7  4569.7  4852.8  4855.7
  4855.7  4856.6  5172.2  5172.6  5172.6  5176.4  5446.4  5446.4  5454.9    5725
  5972.2  6497.8
   39.23   28.72   27.01   26.34   25.12   25.46   26.21   25.59    25.6   25.51
   24.83   23.56   24.64    25.7   26.12   30.81   30.95   32.82   34.56   34.93
   34.93   35.05   35.03   34.98   34.98   34.49   33.85   31.88   31.83   30.71
   31.33   38.55
  -20.32  -20.32  -20.32  -20.32  -20.32  -20.32  -20.32  -20.32  -20.32  -20.32
  -20.32  -20.32  -20.32  -20.32  -20.32  -20.32  -20.32  -20.32  -20.32  -20.32
   27.37   27.37   27.37   27.37  -20.32  -20.32  -20.32  -20.32  -20.32  -20.32
  -20.32  -20.32
-10769.3-10239.6-10135.8 -9781.2 -8480.8   -6726 -5884.4 -5440.3   -3549 -1491.3
  -700.6   972.3  2134.4    3635  4259.8  4557.1  4569.7  4569.7  4852.8  4855.7
  4855.7  4856.6  5172.2  5172.6  5172.6  5176.4  5446.4  5446.4  5454.9    5725
  5972.2  6497.8
   39.23   28.72   27.01   26.34   25.12   25.46   26.21   25.59    25.6   25.51
   24.83   23.56   24.64    25.7   26.12   30.81   30.95   32.82   34.56   34.93
   34.93   35.05   35.03   34.98   34.98   34.49   33.85   31.88   31.83   30.71
   31.33   38.55
  -20.32  -20.32  -20.32  -20.32  -20.32  -20.32  -20.32  -20.32  -20.32  -20.32
  -20.32  -20.32  -20.32  -20.32  -20.32  -20.32  -20.32  -20.32  -20.32  -20.32
   27.37   27.37   27.37   27.37  -20.32  -20.32  -20.32  -20.32  -20.32  -20.32
  -20.32  -20.32
Pier Skew, UpSta & Num, DnSta & Num=  ,4956.2, 2 ,4956.2, 2 , 0 , 0 , 0 ,0,0
       4       4
    -.15   27.37
       4       4
       2   27.37
Pier Skew, UpSta & Num, DnSta & Num=  ,5076.4, 2 ,5076.4, 2 , 0 , 0 , 0 ,0,0
       4       4
   10.65   27.37
       4       4
    12.8   27.37
Abutment Skew #Up #Dn= , 2 , 2
  4855.7  4858.8
   27.37   19.08
  4855.7  4858.8
   27.37   21.23
BR Coef= 1 , 1 , 0 ,1.25, 0 ,,,0.8,0,2,0,
WSPro=,,,, 1 ,,,, 0 ,,,, 0 ,,,,-1 ,-1 ,-1 , 0 , 0 , 0 , 0 , 0
BC Design=,, 0 ,, 0 ,,,,,,
BC HTab HWMax=39
BC Use User HTab Curves=0
BC User HTab FreeFlow(D)= 0

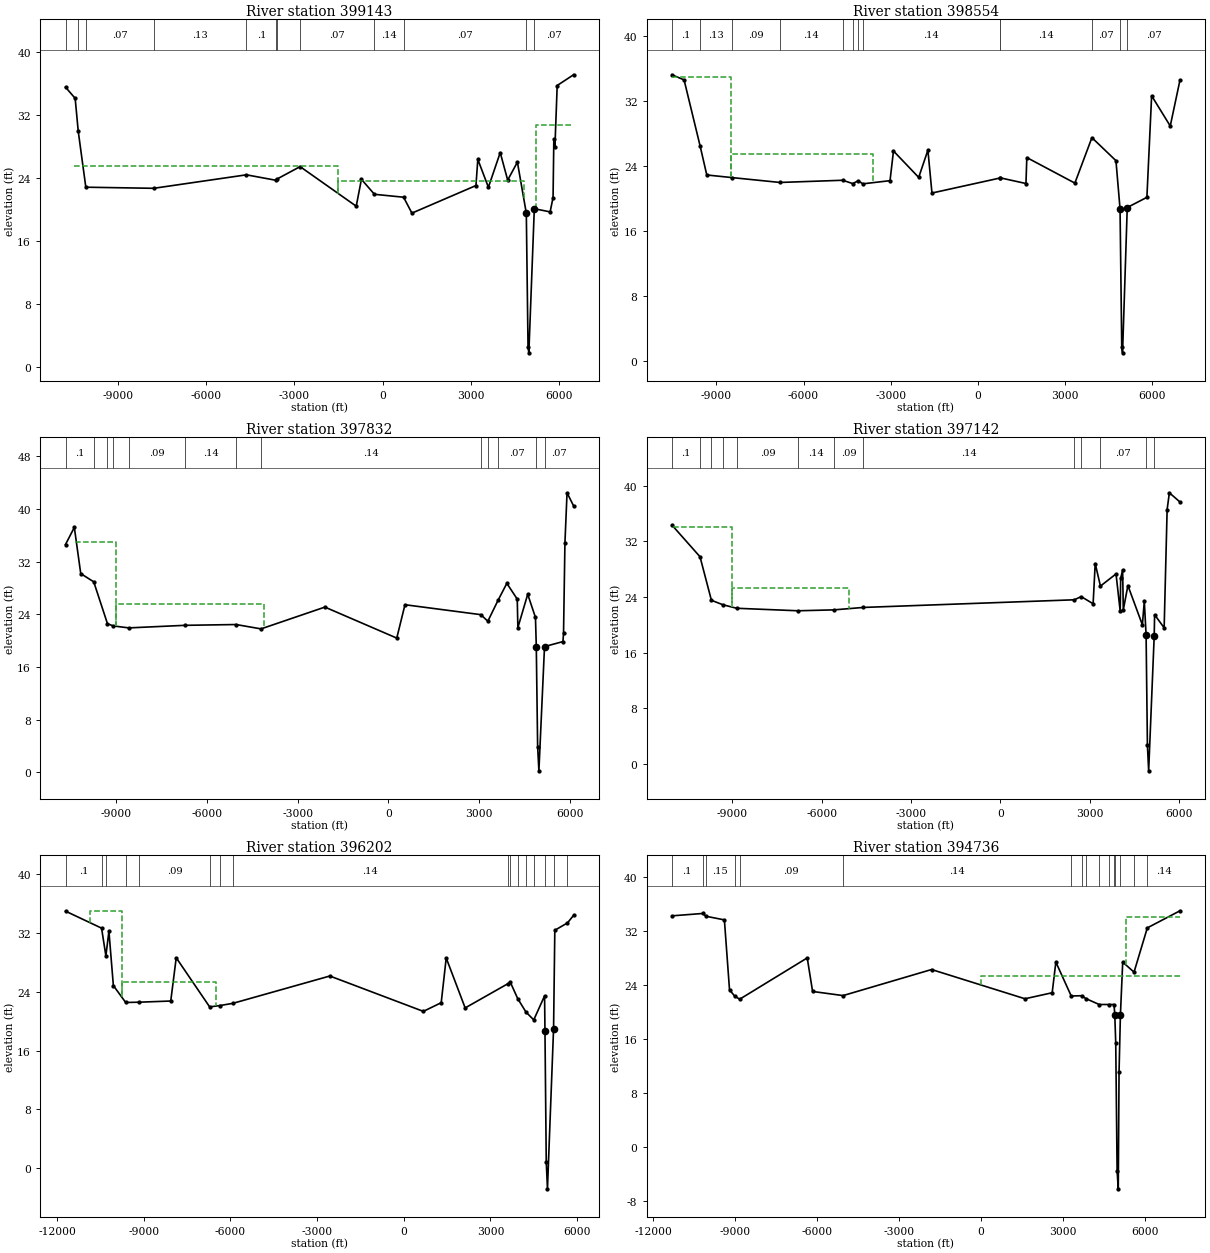
Type RM Length L Ch R = 1 ,399143  ,371,589,583
BEGIN DESCRIPTION:
Pireway Road (WR) ds
END DESCRIPTION:
XS GIS Cut Line= 6
       2125838.3        96376.36      2123853.24        96394.08
      2119249.95        95313.26      2116810.18        93801.23
      2113351.95        95018.47      2110709.49        97905.27
#Sta/Elev= 30
-10777.8   35.53-10449.5   34.11-10345.4   29.95-10087.2   22.84 -7780.3    22.7
 -4627.3   24.41 -3611.9   23.71 -3575.5    23.9   -2802   25.45  -894.3   20.43
  -717.8   23.84  -275.8   21.94   715.7   21.57   998.1   19.55  3176.1   23.05
  3238.9   26.37  3598.9   22.83    4001   27.23  4254.3   23.74  4584.9   26.02
  4887.8   19.54  4946.5    2.52    4974    1.83  5159.6   20.11  5697.2   19.71
    5797   21.53  5823.5   28.95  5860.9      28  5937.5   35.74  6493.6    37.1
#Mann= 12 ,-1 , 0
-10777.8     .07       0-10345.4     .13       0-10087.2     .07       0
 -7780.3     .13       0 -4627.3      .1       0 -3611.9     .14       0
 -3575.5      .1       0   -2802     .07       0  -275.8     .14       0
   715.7     .07       0  4887.8     .04       0  5159.6     .07       0
#XS Ineff= 3 ,-1
-10486.4 -1504.6   25.57 -1504.5  4805.7   23.64  5222.6  6433.2    30.7
Permanent Ineff=
       F       F       F
Bank Sta=4887.8,5159.6
XS Rating Curve= 0 ,0
Exp/Cntr=0.5,0.3

Type RM Length L Ch R = 1 ,398554  ,208,722,755
BEGIN DESCRIPTION:
Waccamaw River 44.0
END DESCRIPTION:
XS GIS Cut Line= 3
      2124674.57        89150.04      2111673.85        95535.84
        2109978.        98001.59
#Sta/Elev= 30
-10526.3   35.23-10109.6    34.6   -9560    26.5 -9328.8   22.91   -8465   22.59
 -6812.2   21.99 -4652.9   22.26 -4307.2   21.85 -4119.2    22.2 -3961.2   21.82
 -3025.1   22.21 -2906.5   25.86 -2038.8   22.61 -1721.9   25.96 -1582.5   20.69
   750.3   22.53   764.6   22.56  1651.4   21.86  1680.7   25.05  3333.7   21.91
  3919.9    27.5  4746.8   24.67  4887.8   18.75  4946.5    1.73    4974    1.04
  5135.6   18.91  5811.5   20.16  5974.1   32.65  6614.9   28.93  6950.7    34.6
#Mann= 13 ,-1 , 0
-10526.3      .1       0   -9560     .13       0   -8465     .09       0
 -6812.2     .14       0 -4652.9     .09       0 -4307.2     .14       0
 -4119.2     .09       0 -3961.2     .14       0   750.3     .07       0
   764.6     .14       0  3919.9     .07       0  4887.8     .04       0
  5135.6     .07       0
#XS Ineff= 2 ,-1
-10552.9   -8500      35 -8499.1   -3600    25.5
Permanent Ineff=
       F       F
Bank Sta=4887.8,5135.6
XS Rating Curve= 0 ,0
Exp/Cntr=0.3,0.1

Type RM Length L Ch R = 1 ,397832  ,305,690,701
BEGIN DESCRIPTION:
Waccamaw River 43.0
END DESCRIPTION:
XS GIS Cut Line= 3
      2124604.08        89150.05      2110720.23        95702.72
      2109802.64        96813.17
#Sta/Elev= 30
-10673.8   34.61-10381.9   37.21-10170.2   30.19 -9740.6   28.94 -9287.2   22.58
   -9098   22.24 -8582.4   21.94 -6725.1   22.33 -5034.7   22.45 -4210.8   21.79
   -2100    25.1   275.8   20.39   546.6   25.46  3055.1   23.95  3285.8   22.95
  3626.8   26.16  3914.3   28.71  4258.2   26.31  4278.7   21.98  4604.4   27.05
  4860.7   23.52  4887.8    19.1  4932.1     3.9    4974     .22  5159.6    19.1
  5768.4   19.86  5788.2   21.12  5834.3   34.82    5904   42.47  6119.2   40.49
#Mann= 13 ,-1 , 0
-10673.8      .1       0 -9740.6     .13       0 -9287.2     .15       0
   -9098     .13       0 -8582.4     .09       0 -6725.1     .14       0
 -5034.7     .09       0 -4210.8     .14       0  3055.1     .07       0
  3285.8     .14       0  3626.8     .07       0  4887.8     .04       0
  5159.6     .07       0
#XS Ineff= 2 ,-1
-10362.4   -9000      35 -8999.9   -4100    25.5
Permanent Ineff=
       F       F
Bank Sta=4887.8,5159.6
XS Rating Curve= 0 ,0
Exp/Cntr=0.3,0.1

Type RM Length L Ch R = 1 ,397142  ,615,940,909
BEGIN DESCRIPTION:
Waccamaw River 42.0
END DESCRIPTION:
XS GIS Cut Line= 3
      2124551.09        89136.96      2109901.87        95636.38
      2109179.17        96365.08
#Sta/Elev= 30
-11026.3   34.33-10085.2   29.78 -9703.1   23.52 -9313.7   22.87 -8851.3   22.37
 -6796.6   22.01 -5590.3   22.14 -4602.6   22.49  2480.1   23.59  2708.2   24.05
  3109.5   23.02  3180.1    28.8  3355.1   25.56  3878.8   27.31  4018.4   21.95
  4034.7   26.66  4099.8   27.89  4122.5   22.14    4277   25.64  4762.6   19.99
  4827.8   23.37  4887.8   18.53  4932.1    2.67    4974   -1.01  5159.6   18.34
  5173.7   21.44  5493.9   19.56    5594   36.57  5668.9   38.98  6026.3   37.65
#Mann= 13 ,-1 , 0
-11026.3      .1       0-10085.2     .13       0 -9703.1     .15       0
 -9313.7     .13       0 -8851.3     .09       0 -6796.6     .14       0
 -5590.3     .09       0 -4602.6     .14       0  2480.1     .07       0
  2708.2     .14       0  3355.1     .07       0  4887.8     .04       0
  5159.6     .07       0
#XS Ineff= 2 ,-1
-10995.2   -9000      34 -8999.9   -5100    25.3
Permanent Ineff=
       F       F
Bank Sta=4887.8,5159.6
XS Rating Curve= 0 ,0
Exp/Cntr=0.3,0.1

Type RM Length L Ch R = 1 ,396202  ,845,1466,1506
BEGIN DESCRIPTION:
Waccamaw River 41.0
END DESCRIPTION:
XS GIS Cut Line= 3
      2124628.93        89039.58      2109257.13        94981.78
      2108516.82        95800.03
#Sta/Elev= 30
  -11707   34.95  -10459   32.64-10309.5   28.87-10204.3   32.22-10050.7   24.83
 -9623.9   22.53 -9154.4   22.57 -8064.5   22.73 -7874.9   28.61 -6717.9   21.93
 -6352.4   22.12 -5917.4   22.41 -2558.2   26.13   678.4   21.32  1296.5    22.5
  1469.6   28.58  2125.4   21.79  3598.7   25.07  3689.3   25.28  3942.6   23.07
  4227.8   21.24  4499.2   20.16  4874.3   23.43  4887.8   18.61  4932.1     .87
    4974   -2.81  5185.5   18.98  5228.6   32.35  5666.3   33.35  5876.8   34.37
#Mann= 16 ,-1 , 0
  -11707      .1       0  -10459     .13       0-10309.5     .15       0
 -9623.9     .13       0 -9154.4     .09       0 -6717.9     .14       0
 -6352.4     .09       0 -5917.4     .14       0  3598.7     .07       0
  3689.3     .14       0  3942.6     .07       0  4227.8     .14       0
  4499.2     .07       0  4887.8     .04       0  5185.5     .07       0
  5666.3     .14       0
#XS Ineff= 2 ,-1
-10851.9   -9750      35 -9749.9   -6500    25.3
Permanent Ineff=
       F       F
Bank Sta=4887.8,5185.5
XS Rating Curve= 0 ,0
Exp/Cntr=0.3,0.1

Type RM Length L Ch R = 1 ,394736  ,484,759,790
BEGIN DESCRIPTION:
Waccamaw River 40.0
END DESCRIPTION:
XS GIS Cut Line= 4
      2124551.05         89000.6      2109198.69        93793.34
      2107951.79        93754.37       2106667.7        93714.24
#Sta/Elev= 30
-11319.4   34.18  -10197   34.53-10060.5   34.11 -9398.5   33.58 -9210.9   23.22
 -9027.1   22.32 -8838.8   21.83 -6363.1   27.95 -6166.8   22.98 -5051.1   22.37
 -1806.7   26.23  1614.4    21.9  2611.9   22.79  2746.3   27.33  3309.9   22.31
  3689.4   22.35  3844.9   21.93  4333.6   21.05  4695.5   21.05  4878.4   21.05
  4905.3   19.55  4940.6   15.39  4991.1   -3.59  5033.3   -6.25    5062   11.06
  5112.3   19.55  5196.4   27.33  5611.1   25.84  6098.3    32.4  7295.9   34.93
#Mann= 16 ,-1 , 0
-11319.4      .1       0  -10197     .13       0-10060.5     .15       0
 -9027.1     .13       0 -8838.8     .09       0 -5051.1     .14       0
  3309.9     .07       0  3689.4     .14       0  3844.9     .07       0
  4333.6     .14       0  4695.5     .07       0  4878.4     .13       0
  4905.3     .04       0  5112.3     .13       0  5611.1     .07       0
  6098.3     .14       0
#XS Ineff= 2 , 0
       0   -7000    25.2    5300       0      34
Permanent Ineff=
       F       F
Bank Sta=4905.3,5112.3
XS Rating Curve= 0 ,0
Exp/Cntr=0.3,0.1

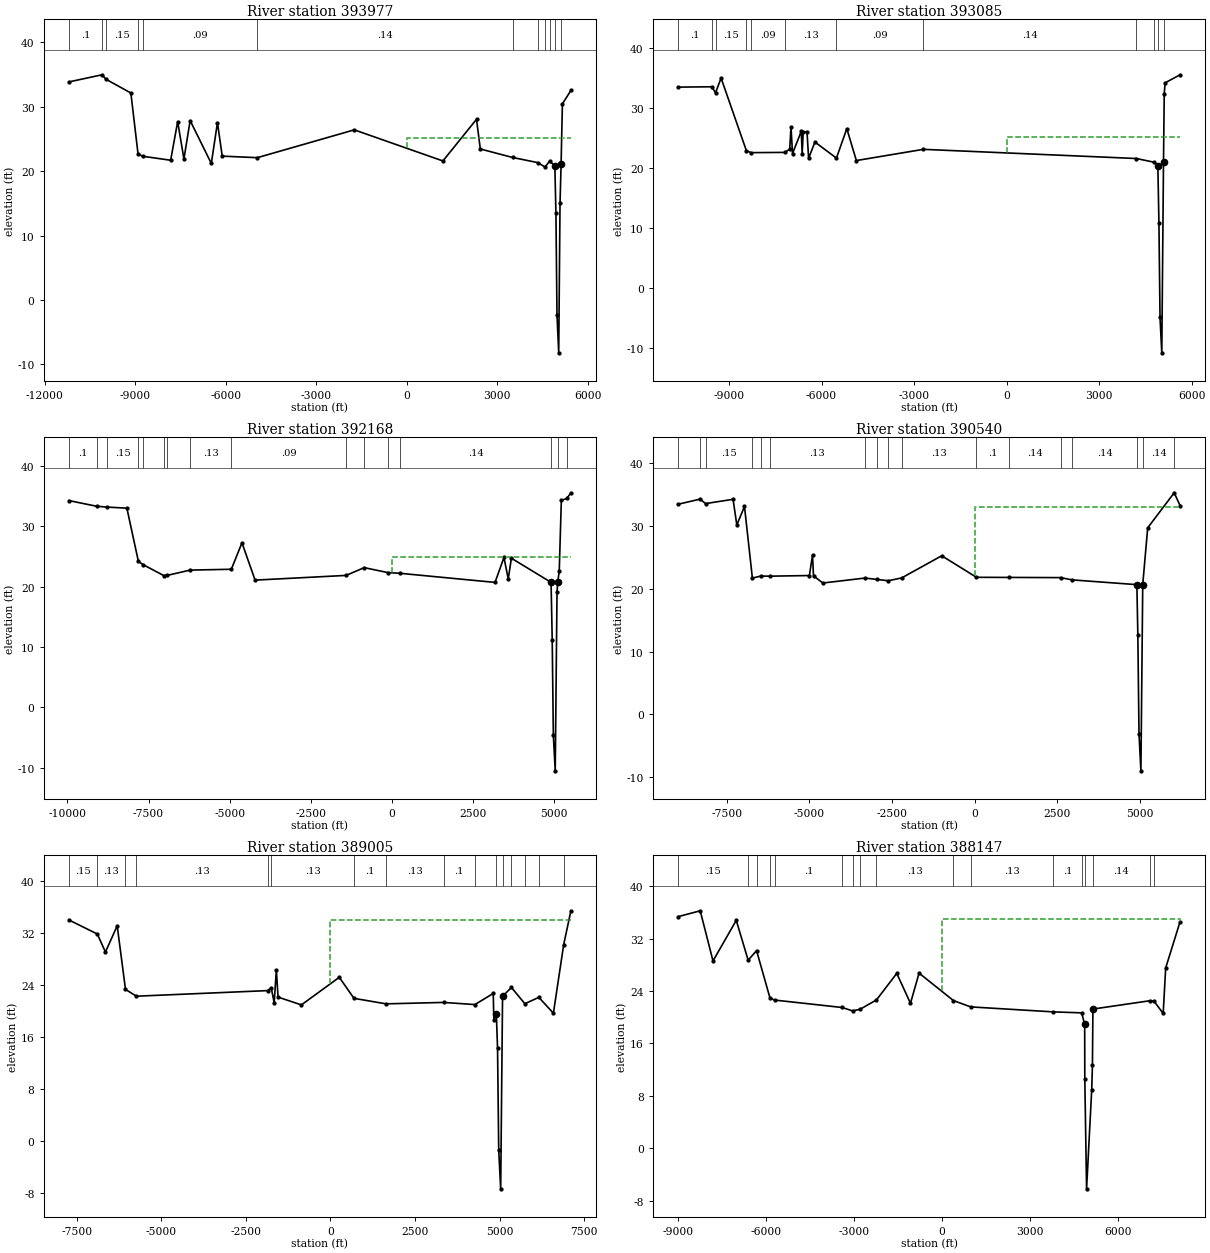
Type RM Length L Ch R = 1 ,393977  ,606,892,889
BEGIN DESCRIPTION:
Waccamaw River 39.0
END DESCRIPTION:
XS GIS Cut Line= 3
      2124551.01        88922.67      2109218.17        93169.89
      2108575.02        92825.01
#Sta/Elev= 30
-11202.8   33.85-10101.4   34.96 -9974.4   34.27 -9146.9   32.13 -8908.9   22.66
 -8755.7   22.31 -7828.1   21.69 -7595.6   27.69 -7388.5   21.89 -7182.2   27.85
 -6480.4   21.19 -6277.6   27.53 -6118.6   22.33 -4957.1   22.09 -1742.6   26.41
    1195   21.58  2308.4   28.05  2434.7   23.44  3504.3   22.12  4342.6   21.32
  4578.9   20.64    4731   21.54  4905.3   20.82  4940.6   13.43  4975.6   -2.29
  5033.3   -8.21  5076.8    15.1  5112.3   21.12    5155   30.45  5437.2   32.52
#Mann= 12 ,-1 , 0
-11202.8      .1       0-10101.4     .13       0 -9974.4     .15       0
 -8908.9     .13       0 -8755.7     .09       0 -4957.1     .14       0
  3504.3     .07       0  4342.6     .14       0  4578.9     .07       0
    4731     .13       0  4905.3     .04       0  5112.3     .07       0
#XS Ineff= 2 , 0
       0   -7500    25.1               0
Permanent Ineff=
       F       F
Bank Sta=4905.3,5112.3
XS Rating Curve= 0 ,0
Exp/Cntr=0.3,0.1

Type RM Length L Ch R = 1 ,393085  ,604,917,860
BEGIN DESCRIPTION:
Waccamaw River 38.0
END DESCRIPTION:
XS GIS Cut Line= 3
      2124570.56        88844.73      2109471.44        92332.14
      2108828.51        91884.03
#Sta/Elev= 30
-10653.3   33.47 -9554.6   33.53 -9437.7   32.51 -9256.9   34.98 -8438.2   22.89
   -8292   22.54 -7193.6   22.58 -7031.6   23.13 -6990.7   26.86 -6940.7   22.39
 -6656.6    26.1 -6627.6   22.36 -6593.9   26.01 -6470.9      26 -6418.6   21.59
 -6214.9   24.31 -5516.7   21.63 -5180.6   26.54 -4870.5   21.22 -2698.8   23.09
  4209.4   21.56  4775.5   20.95  4905.3   20.39  4940.6   10.78  4975.6   -4.94
  5033.3  -10.86  5088.7   20.94  5112.3   32.33  5140.9   34.19    5627   35.53
#Mann= 12 ,-1 , 0
-10653.3      .1       0 -9554.6     .13       0 -9437.7     .15       0
 -8438.2     .13       0   -8292     .09       0 -7193.6     .13       0
 -5516.7     .09       0 -2698.8     .14       0  4209.4     .07       0
  4775.5     .14       0  4905.3     .04       0  5088.7     .07       0
#XS Ineff= 2 , 0
       0   -7500    25.1               0
Permanent Ineff=
       F       F
Bank Sta=4905.3,5088.7
XS Rating Curve= 0 ,0
Exp/Cntr=0.3,0.1

Type RM Length L Ch R = 1 ,392168  ,1003,1628,1625
BEGIN DESCRIPTION:
Waccamaw River 37.0
END DESCRIPTION:
XS GIS Cut Line= 3
       2124564.8         88721.8      2109666.27        91533.35
      2109374.97        91424.99
#Sta/Elev= 30
 -9955.7    34.3 -9103.1   33.36 -8782.2   33.22 -8166.9   33.04   -7812   24.21
 -7665.9   23.67 -7032.6   21.87 -6920.2    21.9   -6219   22.77 -4948.1   22.91
 -4620.3   27.29 -4215.9   21.11 -1411.3   21.89  -853.8   23.18  -126.2   22.36
   248.9   22.24  3178.5   20.73  3453.3   24.86  3585.3   21.31  3682.4   24.74
  4905.3   20.74  4940.6   11.13  4975.6   -4.59  5033.3  -10.51  5088.7   19.16
  5112.3   20.87  5156.8   22.58  5221.7   34.33  5392.1   34.65  5516.6   35.59
#Mann= 16 ,-1 , 0
 -9955.7      .1       0 -9103.1     .13       0 -8782.2     .15       0
   -7812     .13       0 -7665.9     .09       0 -7032.6     .13       0
 -6920.2     .09       0   -6219     .13       0 -4948.1     .09       0
 -1411.3     .13       0  -853.8     .14       0  -126.2      .1       0
   248.9     .14       0  4905.3     .04       0  5112.3     .14       0
  5392.1     .07       0
#XS Ineff= 2 , 0
       0   -6600      25               0
Permanent Ineff=
       F       F
Bank Sta=4905.3,5112.3
XS Rating Curve= 0 ,0
Exp/Cntr=0.3,0.1

Type RM Length L Ch R = 1 ,390540  ,1225,1535,1256
BEGIN DESCRIPTION:
Waccamaw River 36.0
END DESCRIPTION:
XS GIS Cut Line= 3
      2124721.53        88369.19      2110656.39        90249.77
      2109716.13        90602.37
#Sta/Elev= 30
   -8975   33.47 -8306.9   34.29 -8142.3   33.58 -7309.6   34.26 -7195.7   30.18
 -6963.7   33.12 -6724.5   21.71 -6469.2   22.04 -6204.4   22.02 -4999.3   22.12
 -4904.9   25.38 -4875.1   22.07 -4593.1   20.93 -3318.2   21.72 -2968.2   21.51
 -2613.7   21.29 -2206.8   21.74  -994.4   25.27    56.8   21.84  1050.2   21.82
  2604.8   21.79  2949.1   21.43  4911.3   20.67  4940.6   12.66  4975.6   -3.06
  5033.3   -8.98  5088.7   20.69  5238.8   29.72  6040.9    35.3  6219.5   33.25
#Mann= 17 ,-1 , 0
   -8975     .15       0 -8306.9     .13       0 -8142.3     .15       0
 -6724.5     .13       0 -6469.2     .09       0 -6204.4     .13       0
 -3318.2     .09       0 -2968.2     .13       0 -2613.7     .09       0
 -2206.8     .13       0    56.8      .1       0  1050.2     .14       0
  2604.8      .1       0  2949.1     .14       0  4911.3     .04       0
  5088.7     .14       0  6040.9     .14       0
#XS Ineff= 2 , 0
       0   -7000      33               0
Permanent Ineff=
       F       F
Bank Sta=4911.3,5088.7
XS Rating Curve= 0 ,0
Exp/Cntr=0.3,0.1

Type RM Length L Ch R = 1 ,389005  ,801,858,685
BEGIN DESCRIPTION:
Waccamaw River 34.0
END DESCRIPTION:
XS GIS Cut Line= 3
      2124290.54        87742.34      2111244.07         88917.7
      2109637.78        89583.72
#Sta/Elev= 30
 -7729.4   34.07 -6887.7    31.9 -6647.5   29.12   -6300   33.17 -6054.9   23.37
 -5733.2   22.32 -1857.1   23.18 -1748.3   23.62 -1660.1    21.3 -1596.3   26.39
 -1546.3   22.18  -856.4   20.98   263.5   25.23   697.6   21.99  1644.9   21.14
  3344.1   21.36  4270.7   21.03  4813.4   22.74  4831.6   18.69  4905.3   19.57
  4940.6   14.28  4975.6   -1.44  5033.3   -7.36  5088.7   22.31  5350.4   23.66
  5748.5   21.16  6160.3   22.14  6591.3    19.7  6895.3   30.26  7108.8   35.48
#Mann= 16 ,-1 , 0
 -7729.4     .15       0 -6887.7     .13       0 -6054.9      .1       0
 -5733.2     .13       0 -1857.1     .09       0 -1748.3     .13       0
   697.6      .1       0  1644.9     .13       0  3344.1      .1       0
  4270.7     .14       0  4905.3     .04       0  5088.7     .14       0
  5350.4     .14       0  5748.5     .07       0  6160.3     .14       0
  6895.3     .07       0
#XS Ineff= 2 , 0
       0   -6100      34               0
Permanent Ineff=
       F       F
Bank Sta=4905.3,5088.7
XS Rating Curve= 0 ,0
Exp/Cntr=0.3,0.1

Type RM Length L Ch R = 1 ,388147  ,1168,1039,904
BEGIN DESCRIPTION:
Waccamaw River 33.0
END DESCRIPTION:
XS GIS Cut Line= 3
      2125892.95        87033.21      2111412.54        88130.21
      2109061.81        89227.22
#Sta/Elev= 30
 -8996.4   35.34 -8240.3   36.24 -7804.2   28.59   -7011   34.78 -6605.7    28.7
 -6318.5   30.16 -5858.9   22.89 -5699.3   22.62 -3406.2   21.49 -3042.7   20.97
 -2789.8   21.22 -2230.4   22.65 -1539.9   26.69 -1072.1   22.13  -779.3   26.73
   394.3   22.54   980.5   21.58    3797   20.82  4765.4   20.67  4866.5    18.9
  4870.8   10.61  4931.3   -6.17  5106.4    8.95  5131.3   12.68  5146.9   21.25
  7091.3   22.52  7233.6   22.43  7542.8   20.58  7627.8   27.52  8119.6   34.59
#Mann= 17 ,-1 , 0
 -8996.4     .15       0 -6605.7     .07       0 -6318.5     .15       0
 -5858.9     .13       0 -5699.3      .1       0 -3406.2      .1       0
 -3042.7     .13       0 -2789.8      .1       0 -2230.4     .13       0
   394.3      .1       0   980.5     .13       0    3797      .1       0
  4765.4     .14       0  4866.5     .04       0  5146.9     .14       0
  7091.3     .07       0  7233.6     .14       0
#XS Ineff= 2 , 0
       0   -5700      35               0
Permanent Ineff=
       F       F
Bank Sta=4866.5,5146.9
XS Rating Curve= 0 ,0
Exp/Cntr=0.3,0.1

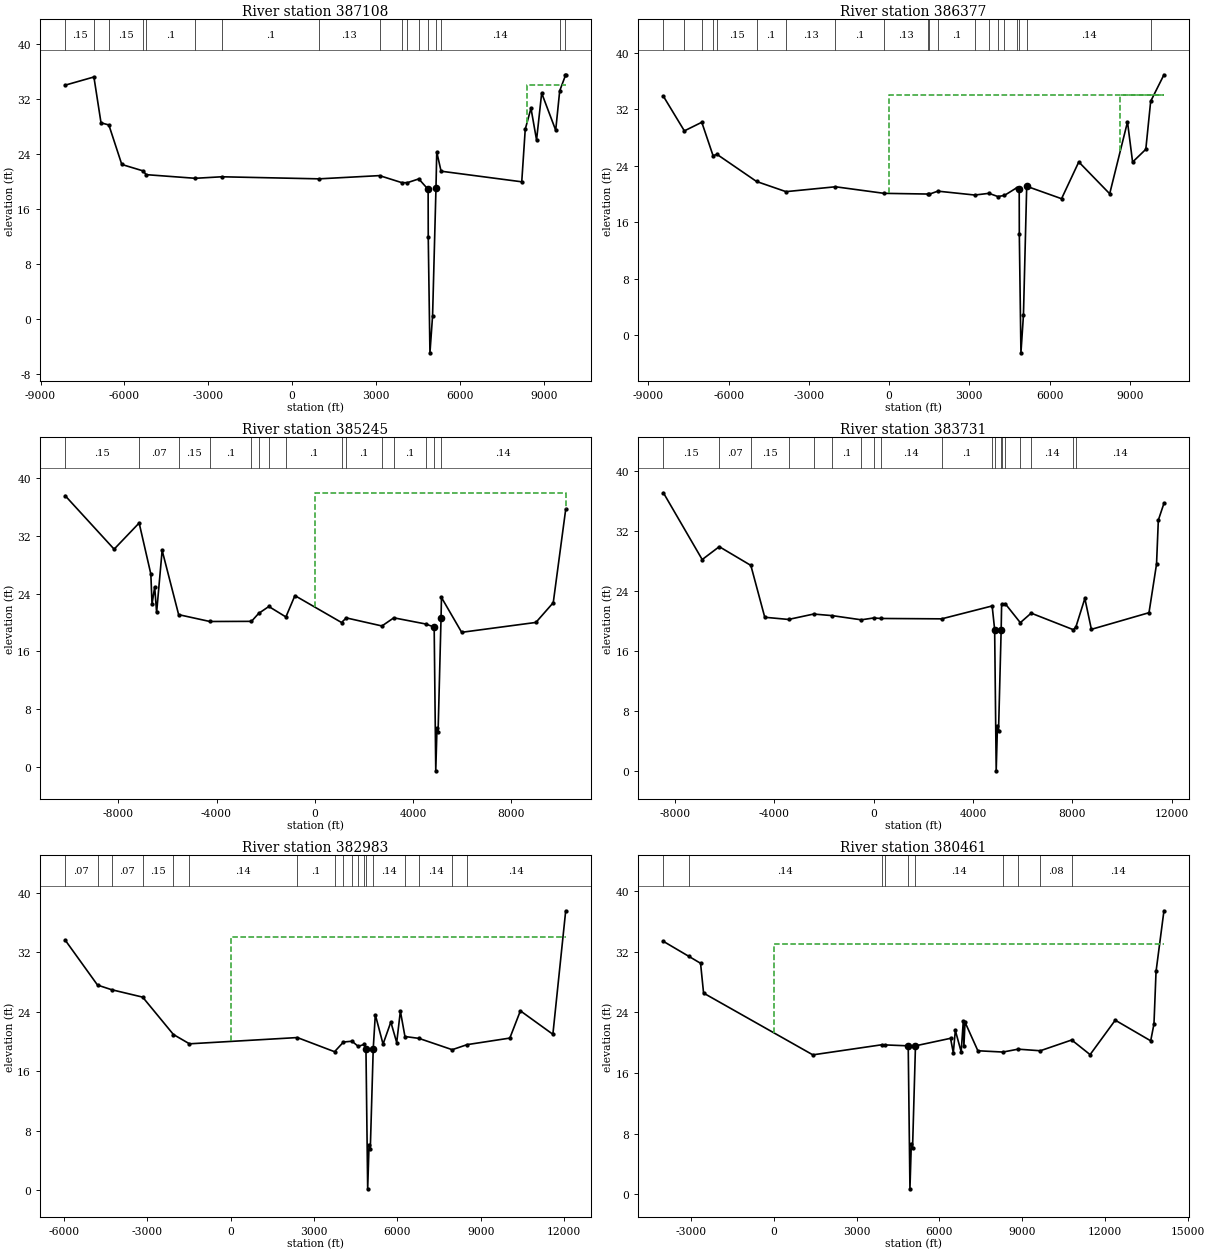
Type RM Length L Ch R = 1 ,387108  ,784,731,484
BEGIN DESCRIPTION:
Waccamaw River 32.0
END DESCRIPTION:
XS GIS Cut Line= 3
      2125203.36        85748.16      2111663.28        87127.24
      2107714.11        88819.74
#Sta/Elev= 30
 -8118.9      34 -7089.6   35.19 -6835.2   28.53 -6554.8   28.22 -6091.9   22.48
 -5327.1   21.54 -5222.8      21 -3463.9   20.47   -2516   20.69   962.5   20.39
  3127.8   20.86  3923.6   19.84    4121   19.83  4532.1   20.38  4866.5   18.86
  4870.8   11.89  4931.3   -4.89  5025.7     .49  5146.9   19.01  5174.6   24.29
  5329.7    21.5  8215.4   19.96  8340.6    27.6  8545.5   30.65  8745.3   26.04
  8928.2   32.85  9430.1   27.45  9573.4   33.18  9779.2   35.42  9787.8   35.51
#Mann= 17 ,-1 , 0
 -8118.9     .15       0 -7089.6     .07       0 -6554.8     .15       0
 -5327.1     .13       0 -5222.8      .1       0 -3463.9     .13       0
   -2516      .1       0   962.5     .13       0  3127.8      .1       0
  3923.6     .14       0    4121      .1       0  4532.1     .14       0
  4866.5     .04       0  5146.9     .14       0  5329.7     .14       0
  9573.4     .07       0  9779.2     .14       0
#XS Ineff= 2 , 0
       0                    8400       0      34
Permanent Ineff=
       F       F
Bank Sta=4866.5,5146.9
XS Rating Curve= 0 ,0
Exp/Cntr=0.3,0.1

Type RM Length L Ch R = 1 ,386377  ,1199,1132,796
BEGIN DESCRIPTION:
Waccamaw River 31.0
END DESCRIPTION:
XS GIS Cut Line= 4
      2125588.24        85095.75      2123650.76        85122.19
      2111976.71        86375.01      2107539.32        88761.98
#Sta/Elev= 30
 -8438.6   33.85 -7654.1   28.94 -7002.7   30.16 -6580.9   25.43 -6432.3   25.61
   -4954   21.77   -3855   20.33 -2003.1   21.02  -186.7   20.09  1462.4   19.99
  1505.5   19.97    1824    20.4    3207   19.85    3734   20.09  4067.7   19.64
  4312.3   19.79  4778.5   20.89  4866.5   20.65  4870.8   14.27  4931.3   -2.51
  5025.7    2.87  5146.9   21.09  6449.7   19.33  7094.2   24.54    8250   20.03
  8915.9   30.21  9106.4   24.52  9600.4   26.33  9782.4   33.13 10278.8   36.89
#Mann= 20 ,-1 , 0
 -8438.6     .15       0 -7654.1     .07       0 -7002.7     .15       0
 -6580.9     .07       0 -6432.3     .15       0   -4954      .1       0
   -3855     .13       0 -2003.1      .1       0  -186.7     .13       0
  1462.4      .1       0  1505.5     .13       0    1824      .1       0
    3207     .14       0    3734      .1       0  4067.7     .14       0
  4312.3      .1       0  4778.5     .14       0  4866.5     .04       0
  5146.9     .14       0  9782.4     .07       0
#XS Ineff= 2 , 0
       0   -6400      34    8650       0      34
Permanent Ineff=
       F       F
Bank Sta=4866.5,5146.9
XS Rating Curve= 0 ,0
Exp/Cntr=0.3,0.1

Type RM Length L Ch R = 1 ,385245  ,1322,1514,436
BEGIN DESCRIPTION:
Waccamaw River 30.0
END DESCRIPTION:
XS GIS Cut Line= 4
      2127502.77        83254.34       2123896.4         83804.5
      2112008.05        85309.35      2108055.34        87960.73
#Sta/Elev= 30
-10166.5    37.6 -8170.9   30.18 -7151.5   33.81 -6675.1   26.73 -6626.7   22.57
 -6518.4   24.94   -6440    21.4 -6214.8   30.01 -5542.7    21.1 -4270.9   20.15
 -2575.9   20.17 -2283.7   21.27 -1867.8   22.23 -1173.3   20.78  -806.3   23.74
  1093.3   20.01    1286   20.65  2738.8   19.53  3222.6   20.66    4527    19.8
  4866.5   19.37  4931.3    -.56    4981    5.39  5025.7    4.82  5146.9   20.69
  5163.5   23.48  5986.3   18.65    9010   20.02  9717.3   22.76 10224.4    35.7
#Mann= 15 ,-1 , 0
-10166.5     .15       0 -7151.5     .07       0 -5542.7     .15       0
 -4270.9      .1       0 -2575.9     .13       0 -2283.7      .1       0
 -1867.8     .14       0 -1173.3      .1       0  1093.3     .14       0
    1286      .1       0  2738.8     .14       0  3222.6      .1       0
    4527     .14       0  4866.5     .04       0  5146.9     .14       0
#XS Ineff= 2 , 0
       0   -6100      38               0
Permanent Ineff=
       F       F
Bank Sta=4866.5,5146.9
XS Rating Curve= 0 ,0
Exp/Cntr=0.3,0.1

Type RM Length L Ch R = 1 ,383731  ,1462,748,377
BEGIN DESCRIPTION:
Waccamaw River 29.0
END DESCRIPTION:
XS GIS Cut Line= 4
      2126522.23        81780.32      2123730.27        82237.76
      2112634.91        84055.64      2107975.67         87956.5
#Sta/Elev= 30
 -8465.5   37.07 -6902.8   28.16 -6215.8   29.88 -4944.8   27.38 -4384.5   20.46
   -3428   20.17   -2417   20.89 -1674.2   20.68    -498   20.12     2.1   20.37
   281.3    20.3  2736.1   20.25  4768.4   21.97  4868.7   18.82  4931.3    -.03
    4981    5.92  5025.7    5.35  5131.3   18.82  5149.3   22.17    5295   22.27
  5901.6   19.74    6339   21.01  8037.6    18.8  8139.6   19.17  8499.5   22.97
  8763.1   18.85   11082   21.07 11385.3   27.55 11457.7   33.42 11683.6   35.66
#Mann= 19 ,-1 , 0
 -8465.5     .15       0 -6215.8     .07       0 -4944.8     .15       0
   -3428      .1       0   -2417     .14       0 -1674.2      .1       0
    -498     .14       0     2.1      .1       0   281.3     .14       0
  2736.1      .1       0  4768.4     .14       0  4868.7     .04       0
  5131.3     .14       0  5149.3     .07       0    5295     .14       0
  5901.6     .08       0    6339     .14       0  8037.6     .08       0
  8139.6     .14       0
Bank Sta=4868.7,5131.3
XS Rating Curve= 0 ,0
Exp/Cntr=0.3,0.1

Type RM Length L Ch R = 1 ,382983  ,1432,2522,628
BEGIN DESCRIPTION:
Waccamaw River 28.0
END DESCRIPTION:
XS GIS Cut Line= 3
      2123291.49        79322.87      2112603.57        83428.79
      2107807.86        87931.34
#Sta/Elev= 30
 -5964.9   33.62 -4797.9   27.57 -4292.7   26.95 -3172.3   25.95 -2064.8   20.93
   -1487   19.68  2397.8   20.52  3738.3   18.62  4059.5   19.92  4367.4   20.03
  4591.1   19.33  4799.6    19.6  4868.7   19.05  4931.3      .2    4981    6.15
  5025.7    5.58  5131.3   19.05  5206.1   23.59  5484.6   19.64  5765.5    22.6
  5976.3   19.85  6108.6   24.07  6273.4   20.66  6778.3   20.41  7975.5   18.89
  8512.6   19.57 10050.6   20.45 10430.4   24.11 11600.7   20.96 12062.7   37.55
#Mann= 18 ,-1 , 0
 -5964.9     .07       0 -4797.9     .14       0 -4292.7     .07       0
 -3172.3     .15       0 -2064.8      .1       0   -1487     .14       0
  2397.8      .1       0  3738.3     .14       0  4059.5      .1       0
  4367.4     .14       0  4591.1      .1       0  4799.6     .14       0
  4868.7     .04       0  5131.3     .14       0  6273.4     .08       0
  6778.3     .14       0  7975.5     .08       0  8512.6     .14       0
#XS Ineff= 2 , 0
       0   -3000      34               0
Permanent Ineff=
       F       F
Bank Sta=4868.7,5131.3
XS Rating Curve= 0 ,0
Exp/Cntr=0.3,0.1

Type RM Length L Ch R = 1 ,380461  ,2045,3319,567
BEGIN DESCRIPTION:
Waccamaw River 25.0
END DESCRIPTION:
XS GIS Cut Line= 3
      2122131.77         77724.4      2112509.54        82206.41
      2107682.76        87942.13
#Sta/Elev= 30
 -3989.8   33.35 -3071.1   31.38 -2644.4   30.46 -2535.5   26.53  1417.6   18.39
  3914.2   19.72  4025.8    19.7  4868.7   19.58  4931.3     .73    4981    6.68
  5025.7    6.11  5131.3   19.58  6400.2   20.57  6500.2   18.67    6574   21.61
  6785.3   18.78  6861.3   22.83  6883.7   19.56  6923.8    22.7  7388.8   18.93
    8295   18.76  8845.7   19.14  9647.2   18.93 10784.1   20.35 11449.4   18.42
 12359.5   22.96 13642.4   20.24 13760.6   22.47 13835.5   29.38 14121.5   37.38
#Mann= 10 ,-1 , 0
 -3989.8     .07       0 -3071.1     .14       0  3914.2      .1       0
  4025.8     .14       0  4868.7     .04       0  5131.3     .14       0
    8295     .08       0  8845.7     .14       0  9647.2     .08       0
 10784.1     .14       0
#XS Ineff= 2 , 0
       0   -1600      33               0
Permanent Ineff=
       F       F
Bank Sta=4868.7,5131.3
XS Rating Curve= 0 ,0
Exp/Cntr=0.3,0.1

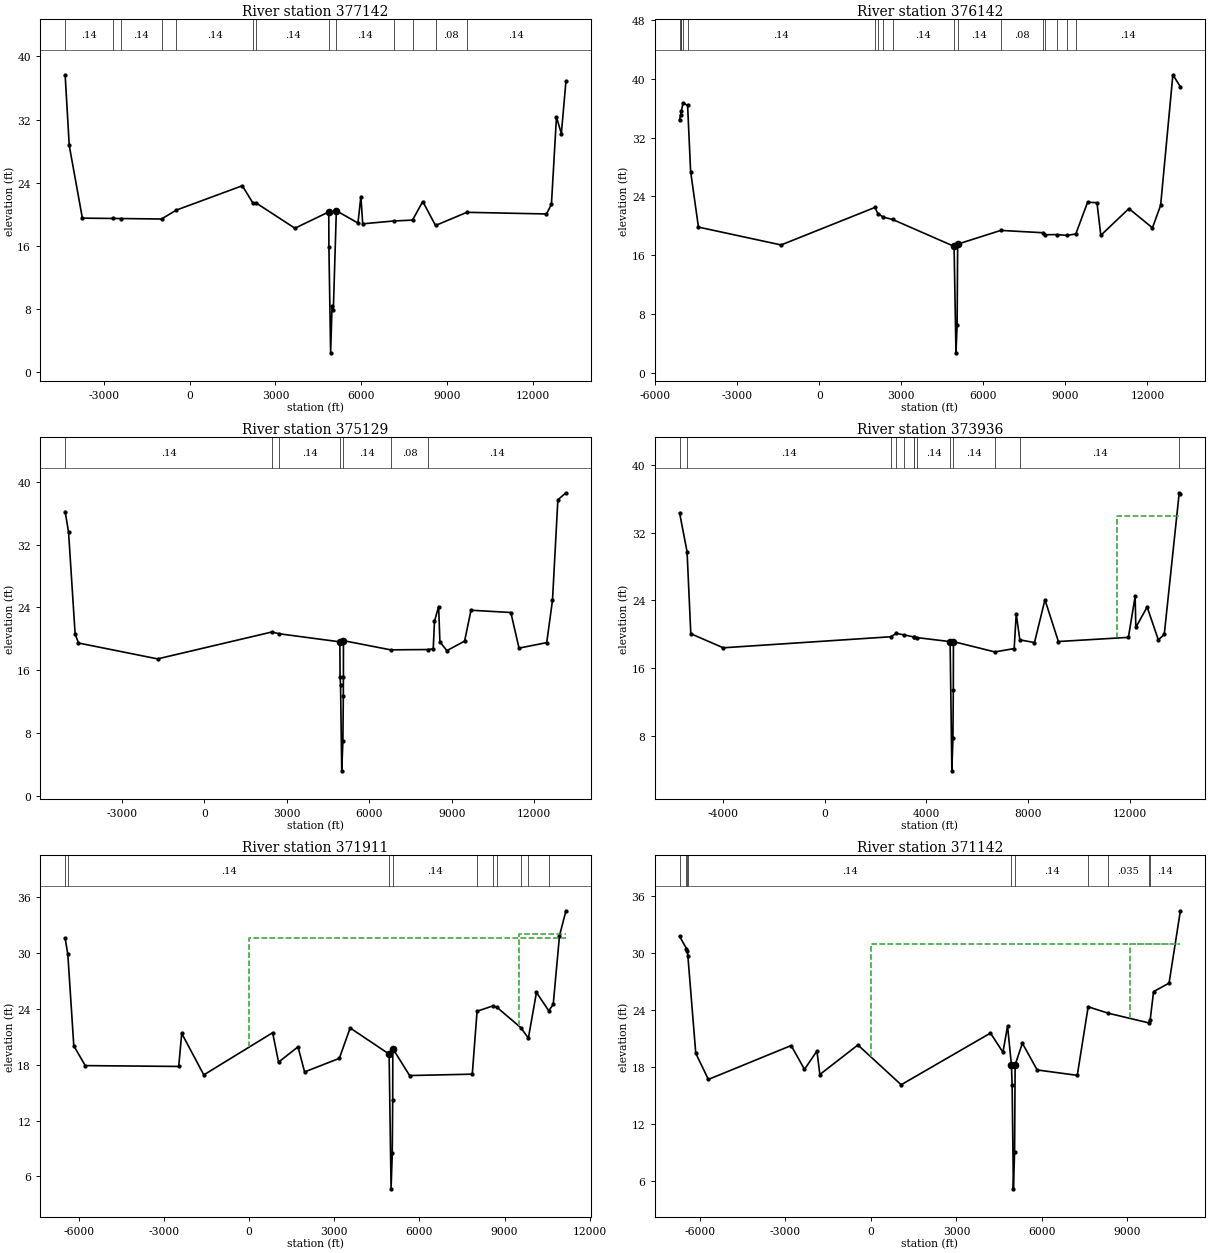
Type RM Length L Ch R = 1 ,377142  ,761,1000,684
BEGIN DESCRIPTION:
Waccamaw River 22.0
END DESCRIPTION:
XS GIS Cut Line= 3
      2119124.97        75075.02      2112131.57        81295.06
      2107432.02        87973.46
#Sta/Elev= 30
 -4359.3   37.68   -4216   28.71 -3756.6   19.49 -2667.4   19.45 -2412.1   19.44
  -986.9   19.38  -468.1   20.51  1840.1    23.6  2201.1   21.47  2330.6    21.4
  3680.9   18.21  4866.5   20.28  4870.8   15.88  4931.3     2.4    4981    8.35
  5025.7    7.78  5131.3   20.43  5887.8   18.87  5990.5   22.23  6053.9   18.77
  7137.6   19.13  7796.9   19.24    8156    21.6  8602.4   18.56  9699.5   20.23
 12484.3   20.02 12658.3   21.24 12834.3   32.31   13006   30.22 13166.2   36.87
#Mann= 13 ,-1 , 0
 -4359.3     .14       0 -2667.4     .07       0 -2412.1     .14       0
  -986.9     .07       0  -468.1     .14       0  2201.1      .1       0
  2330.6     .14       0  4866.5     .04       0  5131.3     .14       0
  7137.6     .08       0  7796.9     .14       0  8602.4     .08       0
  9699.5     .14       0
Bank Sta=4866.5,5131.3
XS Rating Curve= 0 ,0
Exp/Cntr=0.3,0.1

Type RM Length L Ch R = 1 ,376142  ,745,1013,823
BEGIN DESCRIPTION:
Waccamaw River 21.0
END DESCRIPTION:
XS GIS Cut Line= 3
      2118997.54        74402.02       2111312.7        80968.37
        2107015.        87960.71
#Sta/Elev= 30
 -5108.1   34.43   -5068   35.15 -5039.5   35.66 -4982.2   36.68 -4814.8   36.41
 -4704.2   27.39 -4418.4   19.82 -1395.5   17.39  2038.6    22.5  2141.1   21.67
  2345.8   21.17  2682.2   20.86  4931.3    17.2  5000.6     2.7  5042.4    6.53
  5061.8    17.5  6638.9   19.37  8197.1   19.05  8260.3   18.78  8706.8    18.8
  9052.9   18.69  9382.1   18.88  9814.7   23.21 10157.6   23.14 10297.6    18.7
 11325.2   22.34 12186.4   19.72 12485.4   22.79 12933.1   40.56 13207.5   38.93
#Mann= 17 ,-1 , 0
 -5108.1     .14       0   -5068     .07       0 -5039.5     .14       0
 -4982.2     .07       0 -4814.8     .14       0  2038.6      .1       0
  2141.1     .14       0  2345.8      .1       0  2682.2     .14       0
  4931.3     .04       0  5061.8     .14       0  6638.9     .08       0
  8197.1     .14       0  8260.3     .08       0  8706.8     .14       0
  9052.9     .08       0  9382.1     .14       0
Bank Sta=4931.3,5061.8
XS Rating Curve= 0 ,0
Exp/Cntr=0.3,0.1

Type RM Length L Ch R = 1 ,375129  ,677,1193,1372
BEGIN DESCRIPTION:
Waccamaw River 20.0
END DESCRIPTION:
XS GIS Cut Line= 3
      2118574.96        74275.03      2110817.02        80231.82
      2106491.73        87471.98
#Sta/Elev= 30
 -5060.1    36.2 -4935.7   33.57 -4697.3   20.64 -4574.9   19.48 -1698.7   17.46
  2457.3   20.88  2734.4   20.65  4931.3   19.63  4939.5   15.21  4956.7   14.12
  5000.6    3.22  5042.4    7.05  5057.9   12.78  5060.5   15.22  5061.8   19.78
  6777.7   18.61  8154.5   18.65  8328.1   18.75  8372.9   22.25  8523.7   24.12
  8571.2   19.62  8824.6   18.51  9468.2   19.72    9702   23.65 11150.7   23.36
 11447.8   18.83 12455.6   19.53 12665.2    24.9 12861.1    37.7 13154.7   38.59
#Mann= 7 ,-1 , 0
 -5060.1     .14       0  2457.3      .1       0  2734.4     .14       0
  4931.3     .04       0  5061.8     .14       0  6777.7     .08       0
  8154.5     .14       0
Bank Sta=4931.3,5061.8
XS Rating Curve= 0 ,0
Exp/Cntr=0.3,0.1

Type RM Length L Ch R = 1 ,373936  ,656,2025,1803
BEGIN DESCRIPTION:
Waccamaw River 19.0
END DESCRIPTION:
XS GIS Cut Line= 5
      2118502.52        74105.59      2118132.15        74163.46
      2117018.57        74785.02      2110002.11        79918.39
      2104015.65        87127.22
#Sta/Elev= 30
 -5718.2   34.32 -5423.3   29.74 -5276.4   20.07 -3998.6   18.41  2586.7   19.71
  2815.6   20.11    3116   19.93  3501.9   19.69  3528.4   19.67  3630.7   19.61
  4931.3   19.14  5000.6     3.9  5042.4    7.73  5057.9   13.46  5061.8   19.14
  6695.7   17.92    7453   18.32  7534.9    22.4  7676.9   19.34  8253.5   19.03
  8664.6   24.07  9194.5   19.15 11950.8   19.64 12215.4   24.48 12242.6   20.82
 12687.3   23.22   13129   19.34 13361.9   19.99 13950.9   36.69 13996.2   36.55
#Mann= 13 ,-1 , 0
 -5718.2     .07       0 -5423.3     .14       0  2586.7      .1       0
  2815.6     .14       0    3116      .1       0  3501.9     .14       0
  3528.4      .1       0  3630.7     .14       0  4931.3     .04       0
  5061.8     .14       0  6695.7     .08       0  7676.9     .14       0
 13950.9     .07       0
#XS Ineff= 2 , 0
       0                   11500       0   33.91
Permanent Ineff=
       F       F
Bank Sta=4931.3,5061.8
XS Rating Curve= 0 ,0
Exp/Cntr=0.3,0.1

Type RM Length L Ch R = 1 ,371911  ,601,769,812
BEGIN DESCRIPTION:
Waccamaw River 18.0
END DESCRIPTION:
XS GIS Cut Line= 3
      2118243.74        73358.78      2107808.11         80513.9
      2103044.05          81987.
#Sta/Elev= 30
 -6479.6   31.61 -6385.2   29.88 -6174.6   20.04 -5772.2   17.91 -2479.1   17.82
 -2373.6   21.38   -1596   16.91   828.8   21.45  1037.6   18.28  1722.6   19.93
  1954.6   17.23  3177.9   18.69  3559.1   21.96  4931.3   19.15  5000.6    4.65
  5042.4    8.48  5057.9   14.21  5061.8   19.74  5653.9   16.84  7860.9   16.99
  8029.9   23.76  8591.7   24.34  8726.7   24.19  9569.1      22  9836.3   20.86
 10121.8   25.79 10554.1   23.81 10712.1   24.49 10932.5   31.88   11160   34.57
#Mann= 10 ,-1 , 0
 -6479.6     .07       0 -6385.2     .14       0  4931.3     .04       0
  5061.8     .14       0  8029.9     .07       0  8591.7    .035       0
  8726.7     .07       0  9569.1    .035       0  9836.3     .07       0
 10554.1     .14       0
#XS Ineff= 2 , 0
       0   -6300   31.69    9500       0   32.02
Permanent Ineff=
       F       F
Bank Sta=4931.3,5061.8
XS Rating Curve= 0 ,0
Exp/Cntr=0.3,0.1

Type RM Length L Ch R = 1 ,371142  ,639,1000,505
BEGIN DESCRIPTION:
Waccamaw River 17.0
END DESCRIPTION:
XS GIS Cut Line= 3
       2118273.6         72963.1      2108370.56        79222.71
      2103075.36        81736.27
#Sta/Elev= 30
 -6715.5   31.77 -6473.7   30.48 -6446.5   30.24 -6422.8   29.65 -6147.6   19.46
 -5705.9    16.7 -2798.8   20.27 -2331.6   17.76 -1894.5   19.69 -1792.3   17.22
  -456.6   20.33  1061.4   16.14  4196.3   21.58  4634.5   19.56  4795.6   22.32
  4931.3   18.26  4956.7   16.08  5000.6    5.18  5042.4    9.01  5061.8   18.24
  5316.1   20.51  5834.8    17.7  7242.7   17.13  7624.4   24.35  8334.1   23.67
  9745.1   22.66  9800.6   22.94  9920.8   25.95 10464.5   26.84 10861.5   34.46
#Mann= 10 ,-1 , 0
 -6715.5     .07       0 -6473.7     .14       0 -6446.5     .07       0
 -6422.8     .14       0  4931.3     .04       0  5061.8     .14       0
  7624.4     .07       0  8334.1    .035       0  9745.1     .07       0
  9800.6     .14       0
#XS Ineff= 2 , 0
       0   -6300      31    9100       0      31
Permanent Ineff=
       F       F
Bank Sta=4931.3,5061.8
XS Rating Curve= 0 ,0
Exp/Cntr=0.3,0.1