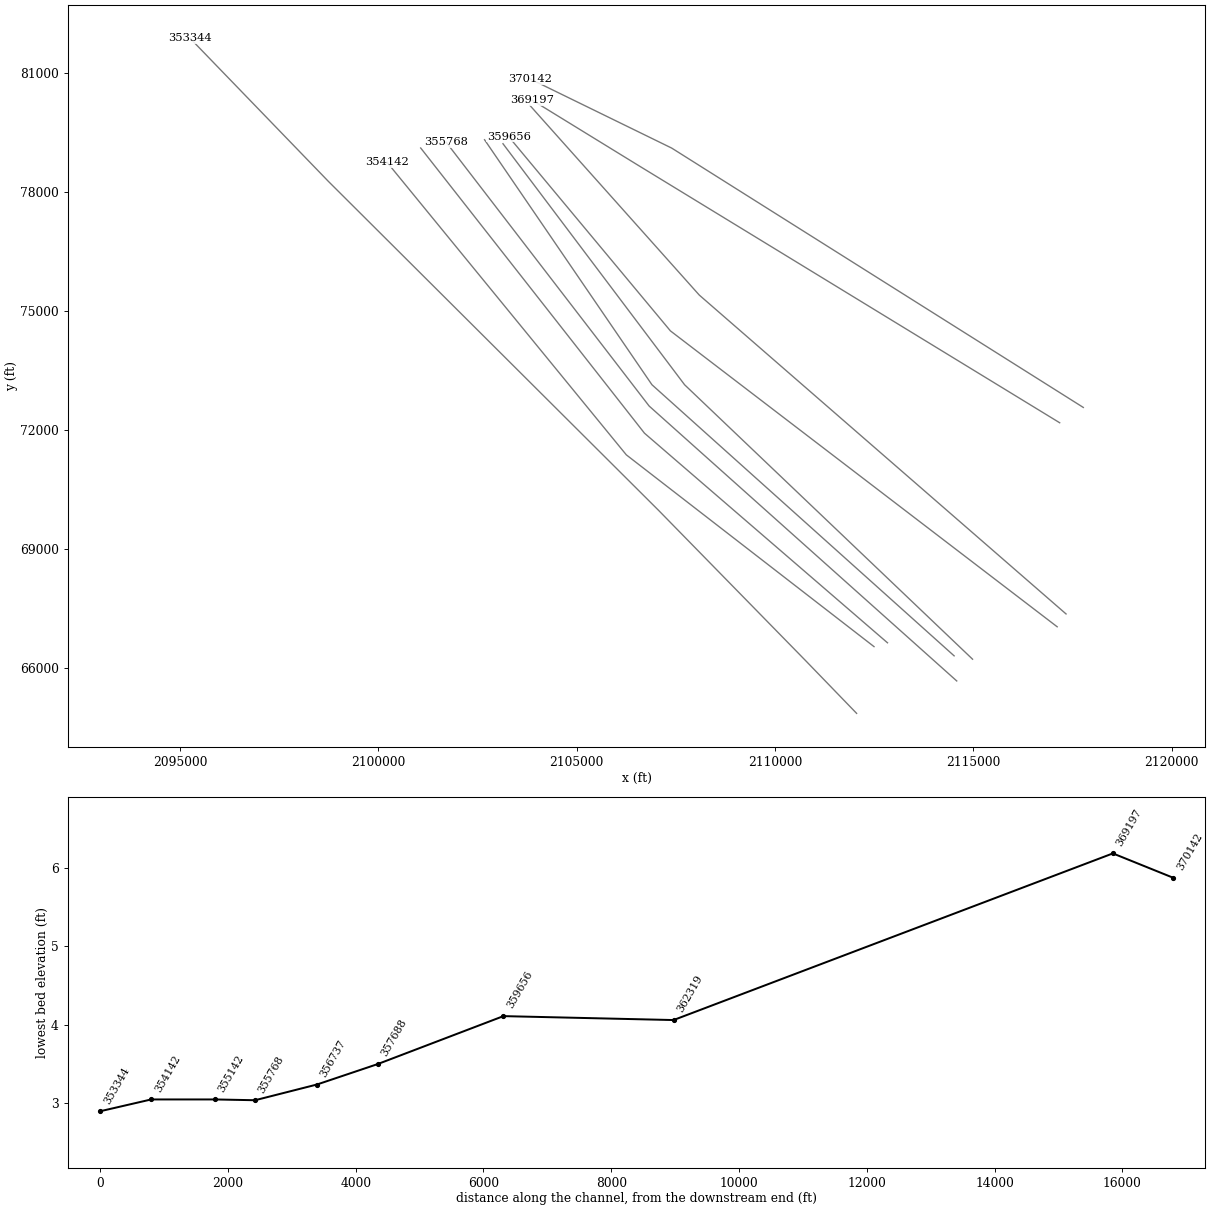
HEC-RAS study Waccamaw River.prj: Waccamaw River Detailed Study

--- Waccamaw River.g01 (geometry) --- (continued)

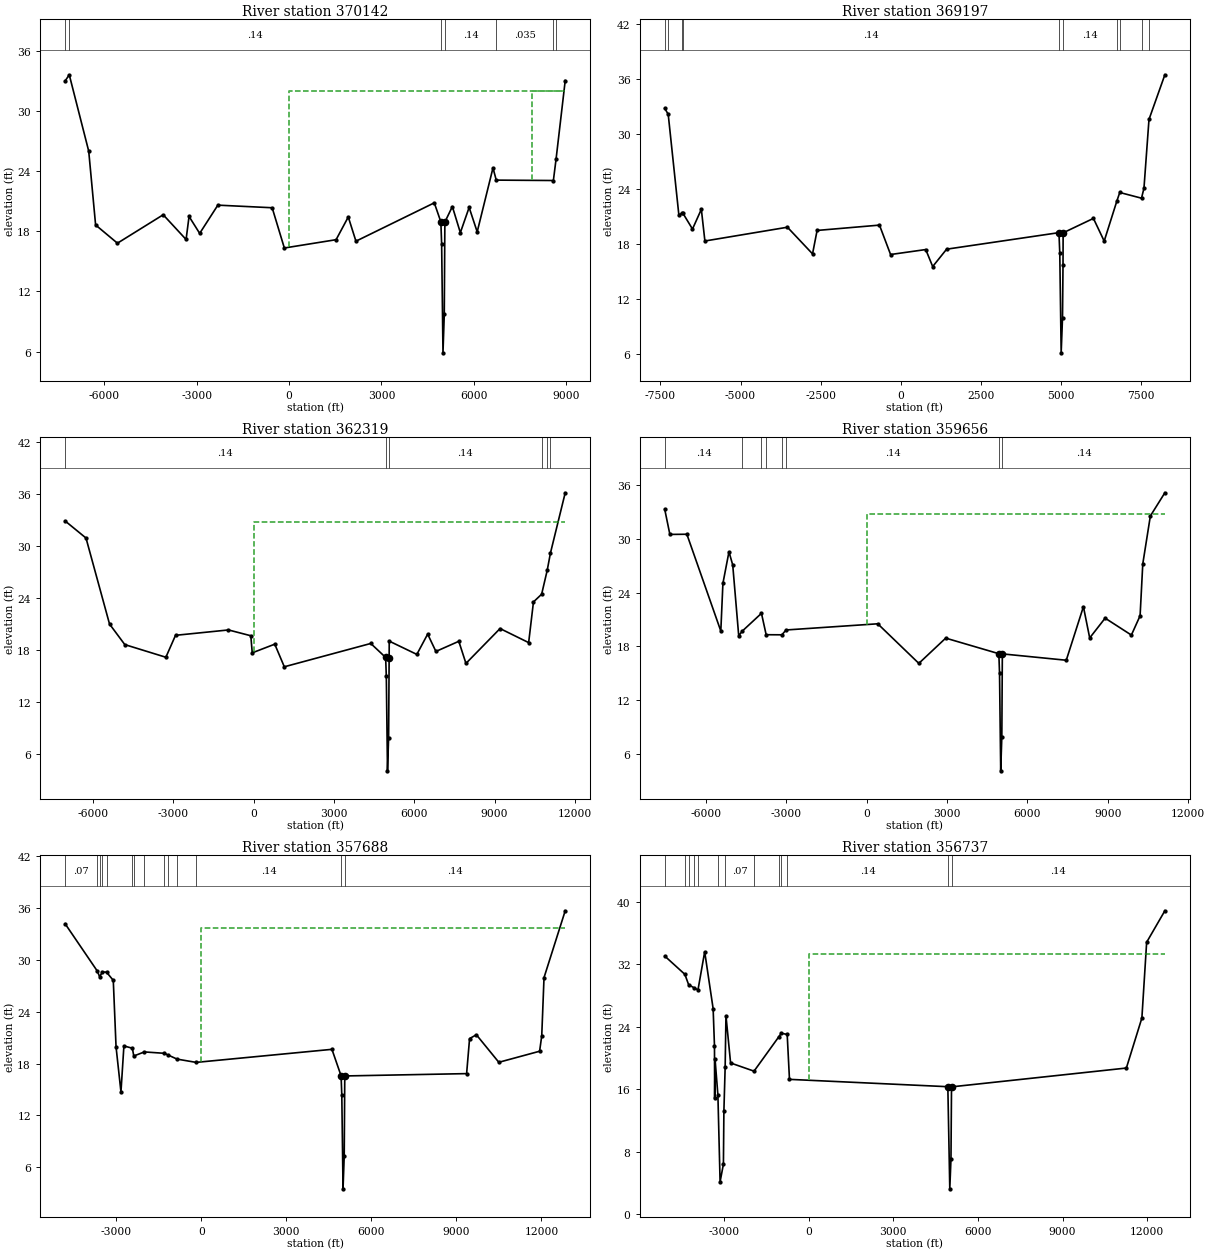
Type RM Length L Ch R = 1 ,370142  ,763,945,732
BEGIN DESCRIPTION:
Waccamaw River 16.0
END DESCRIPTION:
XS GIS Cut Line= 3
       2117774.8        72569.03      2107394.56        79114.66
      2103827.58        80858.67
#Sta/Elev= 30
 -7271.7   33.02 -7136.8   33.64 -6504.7   26.01 -6281.3   18.64 -5572.5   16.82
   -4086   19.66 -3342.9   17.19 -3246.4   19.49 -2901.2    17.8 -2311.1   20.62
  -547.2   20.36  -151.7   16.34    1529   17.17  1924.7   19.44  2173.7   17.02
  4718.1   20.85  4931.3   18.95  4956.7   16.77  5000.6    5.87  5042.4     9.7
  5061.8   18.93  5305.2   20.48  5564.6   17.87  5849.8   20.39  6111.8   17.95
  6624.4   24.34  6730.6   23.12    8586   23.08  8674.6   25.25  8970.5   33.06
#Mann= 7 ,-1 , 0
 -7271.7     .07       0 -7136.8     .14       0  4931.3     .04       0
  5061.8     .14       0  6730.6    .035       0    8586     .14       0
  8674.6     .07       0
#XS Ineff= 2 , 0
       0   -6700      32    7900       0      32
Permanent Ineff=
       F       F
Bank Sta=4931.3,5061.8
XS Rating Curve= 0 ,0
Exp/Cntr=0.3,0.1

Type RM Length L Ch R = 1 ,369197  ,2676,6878,2560
BEGIN DESCRIPTION:
Waccamaw River 15.0
END DESCRIPTION:
XS GIS Cut Line= 3
      2117178.87        72182.68      2106523.06        78696.02
      2103874.98        80325.01
#Sta/Elev= 30
 -7363.2   32.78 -7255.4   32.14 -6922.5   21.16 -6811.1   21.41 -6794.9   21.36
 -6498.1   19.65   -6222    21.8 -6111.1   18.35   -3537   19.85 -2753.9   16.95
 -2611.8    19.5  -666.5   20.08    -320   16.88   776.8   17.42   993.6   15.57
  1427.4   17.46  4931.3   19.26  4956.7   17.08  5000.6    6.18  5042.4   10.01
  5057.9   15.74  5061.8   19.24  6006.2   20.81  6342.4   18.34  6740.3   22.73
  6827.9   23.63  7506.3   23.01  7582.6   24.09  7739.6   31.58  8234.6   36.44
#Mann= 10 ,-1 , 0
 -7363.2     .07       0 -7255.4     .14       0 -6811.1     .07       0
 -6794.9     .14       0  4931.3     .04       0  5061.8     .14       0
  6740.3     .07       0  6827.9    .035       0  7506.3     .14       0
  7739.6     .07       0
Bank Sta=4931.3,5061.8
XS Rating Curve= 0 ,0
Exp/Cntr=0.3,0.1

Type RM Length L Ch R = 1 ,362319  ,952,2663,1280
BEGIN DESCRIPTION:
Waccamaw River 8.0
END DESCRIPTION:
XS GIS Cut Line= 4
      2117339.16        67357.77      2116736.71        67881.94
       2108090.2        75405.02      2103819.61        80190.76
#Sta/Elev= 30
 -7037.2   32.88 -6257.2   30.91 -5378.5   20.99 -4808.5   18.62 -3274.8   17.16
 -2914.4   19.69  -937.1   20.31    -103   19.64   -49.9   17.67     791   18.67
  1147.6   16.06  4375.5   18.75  4931.3   17.14  4956.7   14.96  5000.6    4.06
  5042.4    7.89  5061.8   17.12  5065.6   19.02  6095.9   17.49  6500.5   19.83
  6808.2   17.83  7663.3      19  7929.9   16.45  9203.7   20.47 10271.4   18.85
 10450.8   23.54 10756.1   24.43 10964.5   27.19 11084.4   29.17 11636.7   36.13
#Mann= 6 ,-1 , 0
 -7037.2     .14       0  4931.3     .04       0  5061.8     .14       0
 10756.1     .07       0 10964.5     .14       0 11084.4     .07       0
#XS Ineff= 2 , 0
       0   -3900   32.76               0
Permanent Ineff=
       F       F
Bank Sta=4931.3,5061.8
XS Rating Curve= 0 ,0
Exp/Cntr=0.3,0.1

Type RM Length L Ch R = 1 ,359656  ,1148,1968,466
BEGIN DESCRIPTION:
Waccamaw River 6.0
END DESCRIPTION:
XS GIS Cut Line= 4
      2117115.64        67033.86      2116522.02        67488.35
      2107361.97        74501.51      2103282.87        79403.59
#Sta/Elev= 30
 -7535.4    33.3 -7344.3   30.51 -6710.3   30.53 -5443.5   19.72 -5365.4   25.04
 -5139.2   28.57 -4999.2    27.1 -4775.3   19.19 -4643.6   19.71 -3926.7    21.7
 -3751.6   19.31 -3164.4    19.3   -3009   19.84     412   20.53  1945.6   16.11
  2948.9   18.93  4931.3   17.19  4956.7   15.01  5000.6    4.11  5042.4    7.94
  5061.8   17.17  7446.9   16.46  8086.9   22.44  8321.3   18.95  8897.2   21.16
  9876.5   19.27 10201.9   21.43 10301.9   27.22 10584.8   32.57   11126   35.16
#Mann= 8 ,-1 , 0
 -7535.4     .14       0 -4643.6    .035       0 -3926.7     .07       0
 -3751.6     .14       0 -3164.4     .07       0   -3009     .14       0
  4931.3     .04       0  5061.8     .14       0
#XS Ineff= 2 , 0
       0   -3300   32.74               0
Permanent Ineff=
       F       F
Bank Sta=4931.3,5061.8
XS Rating Curve= 0 ,0
Exp/Cntr=0.3,0.1

Type RM Length L Ch R = 1 ,357688  ,496,951,564
BEGIN DESCRIPTION:
Waccamaw River 5.0
END DESCRIPTION:
XS GIS Cut Line= 4
      2114981.66        66215.75      2113909.98        67237.88
      2107719.79        73141.81      2103139.76        79224.66
#Sta/Elev= 30
 -4807.8   34.17 -3670.8   28.69 -3590.1   28.04 -3490.4   28.59   -3347   28.57
 -3107.6   27.62   -3010   19.92 -2836.9   14.71 -2732.9   20.03   -2434   19.77
 -2384.2   18.87   -2010   19.34 -1304.1   19.18 -1177.8   18.99  -858.5   18.51
  -184.6   18.13  4608.8   19.64  4931.3   16.58  4956.7    14.4  5000.6     3.5
  5042.4    7.33  5061.8   16.56  9361.8   16.83  9466.2   20.88  9705.5   21.33
 10498.6   18.14 11937.4   19.42 12013.2    21.2 12093.5   27.94 12841.7   35.67
#Mann= 14 ,-1 , 0
 -4807.8     .07       0 -3670.8     .15       0 -3590.1     .07       0
 -3490.4     .15       0   -3347     .07       0   -2434     .14       0
 -2384.2     .07       0   -2010     .14       0 -1304.1     .07       0
 -1177.8     .14       0  -858.5     .07       0  -184.6     .14       0
  4931.3     .04       0  5061.8     .14       0
#XS Ineff= 2 , 0
       0    -800   33.67               0
Permanent Ineff=
       F       F
Bank Sta=4931.3,5061.8
XS Rating Curve= 0 ,0
Exp/Cntr=0.3,0.1

Type RM Length L Ch R = 1 ,356737  ,457,969,506
BEGIN DESCRIPTION:
Waccamaw River 4.0
END DESCRIPTION:
XS GIS Cut Line= 4
      2114516.63        66300.36      2113552.16        67166.31
      2106896.81        73141.81      2102674.99        79325.01
#Sta/Elev= 30
 -5103.2   33.05 -4389.9   30.71 -4256.4   29.38 -4056.9   28.97 -3925.6   28.71
 -3687.6    33.6   -3388   26.31 -3340.5   21.53   -3334   14.84 -3321.3   19.91
   -3219   15.23 -3141.7    4.14 -3023.7     6.4 -3006.8    13.2 -2961.9   18.84
 -2933.8   25.42 -2769.6   19.36 -1938.5   18.31 -1068.7   22.67  -970.2   23.17
  -763.1   23.01  -682.1   17.26  4931.3   16.32  5000.6    3.24  5042.4    7.07
  5061.8    16.3 11259.5   18.71 11809.8   25.12 11978.6   34.82 12624.3   38.85
#Mann= 13 ,-1 , 0
 -5103.2     .07       0 -4389.9     .15       0 -4256.4     .07       0
 -4056.9     .15       0 -3925.6     .07       0   -3219    .035       0
 -2961.9     .07       0 -1938.5     .04       0 -1068.7     .14       0
  -970.2     .07       0  -763.1     .14       0  4931.3     .04       0
  5061.8     .14       0
#XS Ineff= 2 , 0
       0    -800   33.37               0
Permanent Ineff=
       F       F
Bank Sta=4931.3,5061.8
XS Rating Curve= 0 ,0
Exp/Cntr=0.3,0.1

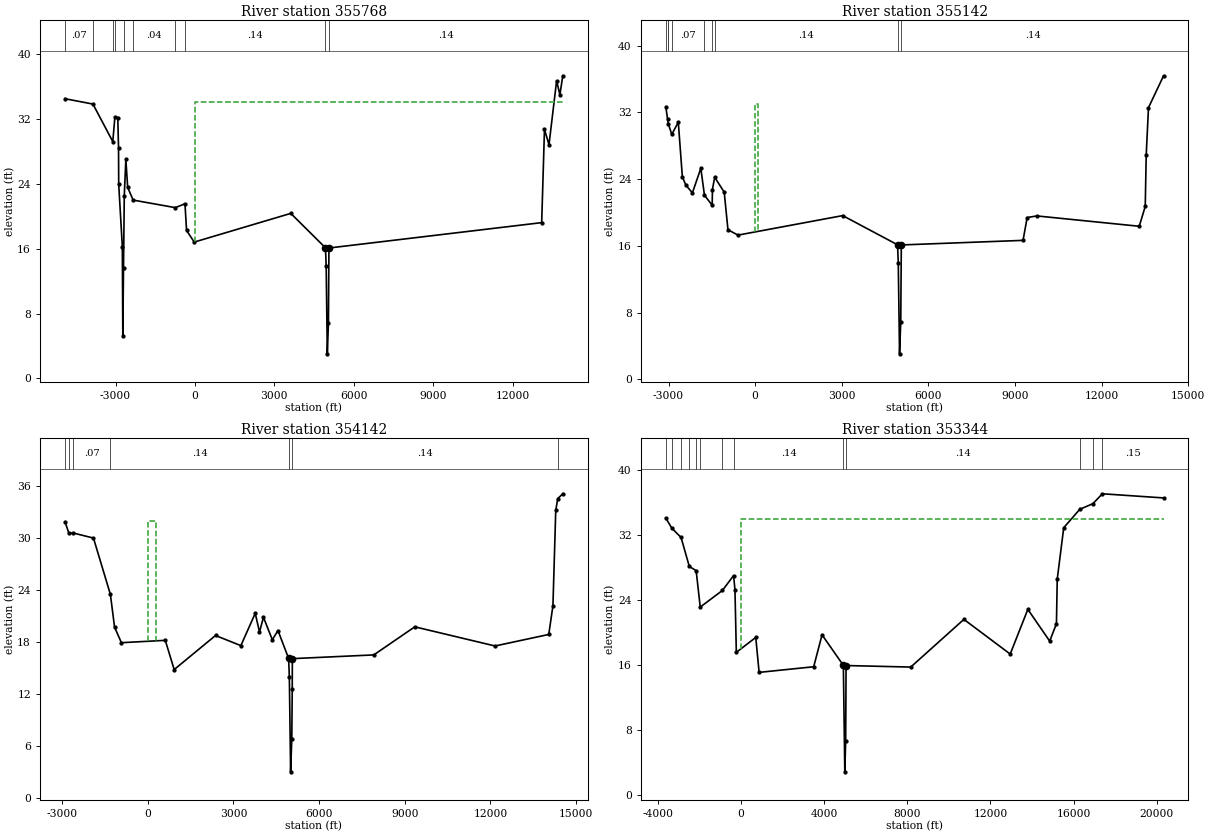
Type RM Length L Ch R = 1 ,355768  ,573,626,541
BEGIN DESCRIPTION:
Waccamaw River 3.0
END DESCRIPTION:
XS GIS Cut Line= 4
      2114582.68         65666.5      2113265.91        66844.28
      2106825.25        72605.09       2101708.5        79260.45
#Sta/Elev= 30
 -4908.2   34.52 -3853.4   33.86 -3102.6   29.23 -3023.9   32.25 -2914.9    32.2
 -2885.7   28.44 -2879.4   23.98 -2742.5   16.28 -2724.1    5.25 -2698.2   13.66
 -2668.6   22.57 -2609.3   27.03 -2540.8   23.58 -2333.3   22.01  -740.5   21.08
  -376.4   21.56  -316.3   18.27   -26.7   16.83  3619.9   20.37  4931.3   16.12
  4956.7   13.94  5000.6    3.04  5042.4    6.87  5061.8    16.1 13097.4   19.23
 13203.1   30.74 13373.6   28.85 13661.3   36.73 13785.1   35.01 13894.5   37.35
#Mann= 10 ,-1 , 0
 -4908.2     .07       0 -3853.4     .15       0 -3102.6     .07       0
 -3023.9    .035       0 -2698.2     .07       0 -2333.3     .04       0
  -740.5     .07       0  -376.4     .14       0  4931.3     .04       0
  5061.8     .14       0
#XS Ineff= 2 , 0
       0    -600   34.15               0
Permanent Ineff=
       F       F
Bank Sta=4931.3,5061.8
XS Rating Curve= 0 ,0
Exp/Cntr=0.3,0.1

Type RM Length L Ch R = 1 ,355142  ,649,1000,761
BEGIN DESCRIPTION:
Waccamaw River 2.0
END DESCRIPTION:
XS GIS Cut Line= 3
      2112836.51        66629.61      2106707.85        71919.68
      2101064.42        79117.35
#Sta/Elev= 30
   -3096   32.68 -3032.9   31.18 -3007.5   30.61 -2888.2   29.37 -2662.8   30.83
 -2522.1   24.28 -2400.3   23.29 -2174.9   22.35 -1882.7    25.3 -1756.8   22.08
 -1488.9   20.87   -1480   22.76 -1403.1   24.23 -1072.3   22.44  -942.7   17.93
    -595   17.29  3031.4   19.63  4931.3   16.13  4956.7   13.95  5000.6    3.05
  5042.4    6.88  5061.8   16.11  9278.3   16.66  9421.2    19.4  9757.6   19.59
 13302.7   18.35 13511.1   20.73 13544.6   26.89 13623.7   32.58 14146.3    36.4
#Mann= 9 ,-1 , 0
   -3096     .15       0 -3032.9     .07       0 -3007.5     .15       0
 -2888.2     .07       0 -1756.8     .04       0   -1480     .07       0
 -1403.1     .14       0  4931.3     .04       0  5061.8     .14       0
#XS Ineff= 2 , 0
       0     100      33               0
Permanent Ineff=
       F       F
Bank Sta=4931.3,5061.8
XS Rating Curve= 0 ,0
Exp/Cntr=0.3,0.1

Type RM Length L Ch R = 1 ,354142  ,656,798,715
BEGIN DESCRIPTION:
Waccamaw River 1.0
END DESCRIPTION:
XS GIS Cut Line= 3
      2112496.61        66532.98      2106250.03        71373.08
      2100216.43        78755.91
#Sta/Elev= 30
 -2902.3    31.9 -2765.8   30.58   -2611    30.6   -1905   30.02   -1312   23.52
 -1166.2   19.75  -927.2   17.95   610.6   18.22   922.6   14.85  2370.3   18.78
    3258   17.61  3761.7   21.34  3910.3   19.18  4049.9   20.88  4359.8   18.29
  4558.6   19.35  4931.3   16.13  4956.7   13.95  5000.6    3.05  5042.4    6.88
  5057.9   12.61  5061.8   16.11  7914.8   16.54  9350.1   19.78   12163   17.57
 14043.7    18.9 14189.8   22.21 14288.2   33.22 14358.6   34.57 14534.7   35.13
#Mann= 7 ,-1 , 0
 -2902.3     .07       0 -2765.8     .15       0   -2611     .07       0
   -1312     .14       0  4931.3     .04       0  5061.8     .14       0
 14358.6     .07       0
#XS Ineff= 2 , 0
       0     300      32               0
Permanent Ineff=
       F       F
Bank Sta=4931.3,5061.8
XS Rating Curve= 0 ,0
Exp/Cntr=0.3,0.1

Type RM Length L Ch R = 1 ,353344  ,0,0,0
BEGIN DESCRIPTION:
Waccamaw River NC/SC tie-in
END DESCRIPTION:
XS GIS Cut Line= 6
      2112057.88        64848.48      2110775.92        66174.68
       2107065.4        69970.18      2104079.39        72947.41
      2098739.33        78271.86      2095250.47         81884.5
#Sta/Elev= 30
 -3605.7   34.08 -3314.8   32.83 -2870.7   31.69 -2474.9   28.13 -2145.9   27.62
 -1949.6   23.14  -885.8   25.18  -345.5   27.01  -279.9   25.25  -214.3   17.58
   719.8   19.41   880.9   15.12  3504.3   15.81  3907.2   19.73  4931.3   15.98
  5000.6     2.9  5042.4    6.73  5061.8   15.96  8170.6   15.77 10725.9   21.63
 12952.5   17.37 13800.5   22.86 14851.1   18.96 15175.9    21.1 15213.7   26.56
   15526   32.89 16296.7   35.15 16926.9   35.84 17384.1   37.06 20326.6   36.55
#Mann= 13 ,-1 , 0
 -3605.7     .07       0 -3314.8     .14       0 -2870.7     .07       0
 -2474.9     .14       0 -2145.9     .07       0 -1949.6     .14       0
  -885.8     .07       0  -345.5     .14       0  4931.3     .04       0
  5061.8     .14       0 16296.7     .07       0 16926.9     .14       0
 17384.1     .15       0
#XS Ineff= 2 , 0
       0    -400      34               0
Permanent Ineff=
       F       F
Bank Sta=4931.3,5061.8
XS Rating Curve= 0 ,0
Exp/Cntr=0.3,0.1

Chan Stop Cuts=-1
Use User Specified Reach Order=0