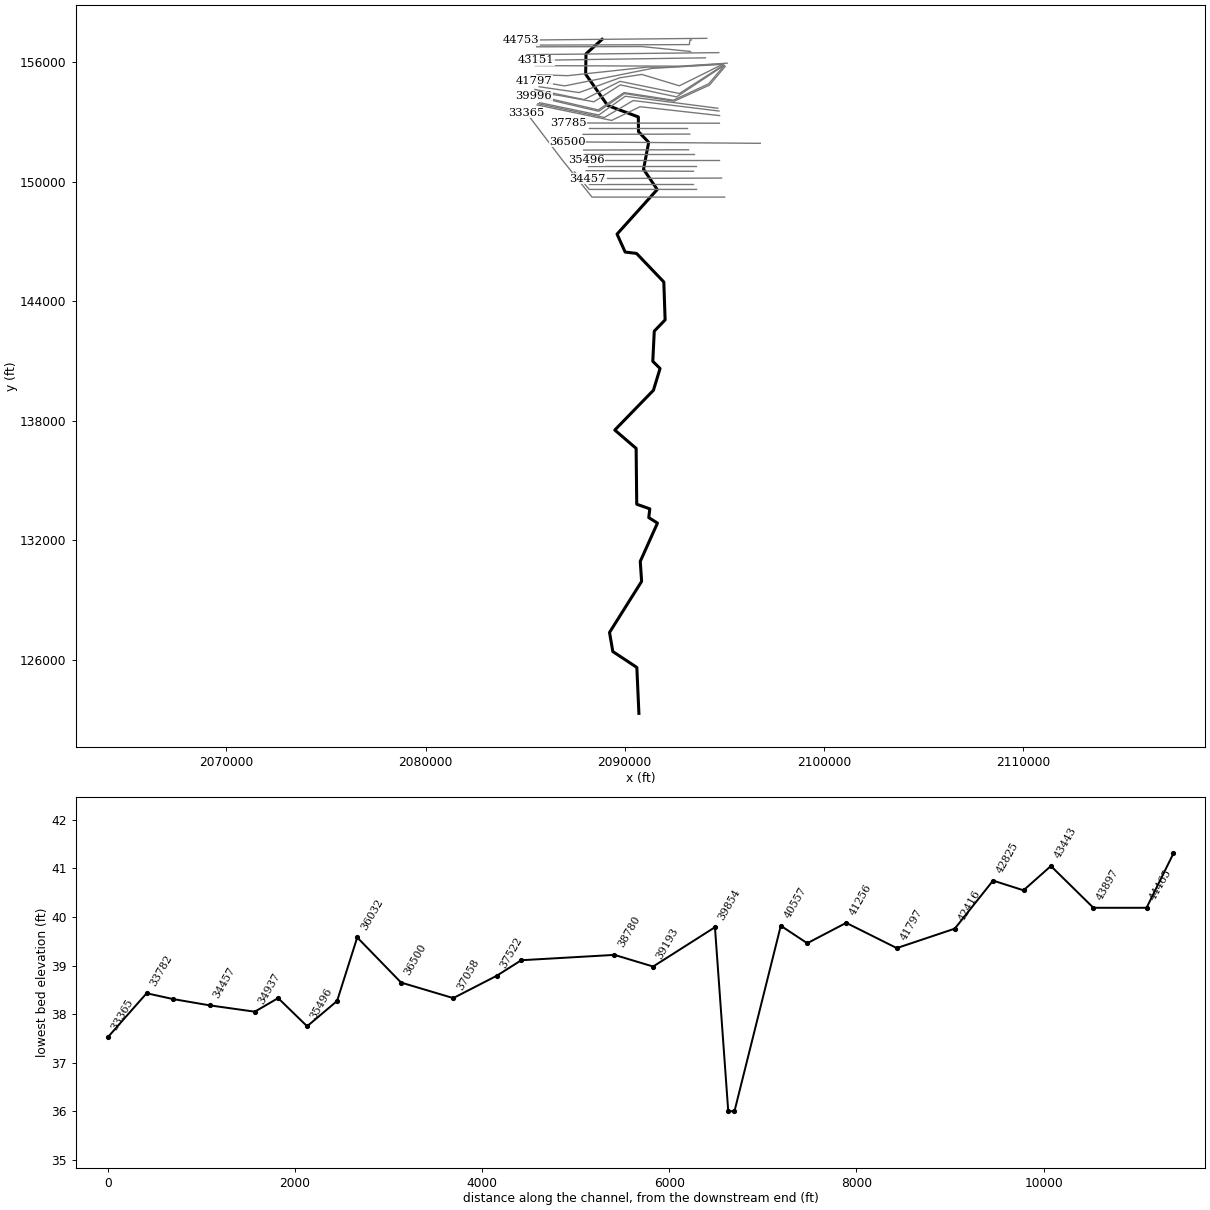
--- monieswamp.prj (project) ---

Proj Title=MonieSwamp
Current Plan=p01
Default Exp/Contr=.3,.1
English Units
Geom File=g01
Flow File=f01
Plan File=p01
Y Axis Title=Elevation
X Axis Title(PF)=Main Channel Distance
X Axis Title(XS)=Station
BEGIN DESCRIPTION:
Monie Swamp - Approximate Study
END DESCRIPTION:
DSS Export Rating Curves= 0
DSS Export Rating Curve Sorted= 0
DSS Export Volume Flow Curves= 0
DXF OffsetX= 0
DXF OffsetY= 0
DXF ScaleX= 1
DXF ScaleY= 10

--- monieswamp.p01 (plan) ---

Plan Title=Monie Swamp
Version=September 1998 Version 2.2
Short Identifier=MonieSwamp
Geom File=g01
Flow File=f01
Interactive Comp Mode
Subcritical Flow
K Sum by GR= 0
Std Step Tol= 0.01
Critical Tol= 0.01
Num of Std Step Trials= 20
Max Error Tol= 0.3
Flow Tol Ratio= 0.001
Log Output Level= 0
Friction Slope Method= 1
Calc Critical at every XS
Parabolic Critical Depth
Global Vel Dist= 0 , 0 , 0
Global Log Level= 0
Encroach Param=-1 ,0,0, 2
Encroach River=Monte Swamp
Encroach Reach=Monte Swamp
Encroach Node=48780.21
       1 5929.97 9483.18
Encroach Node=44266
       1    6140    6270
Encroach Node=44225
       1    6140    6270
Encroach Node=44183
       1    6140    6270
Encroach Node=42153.29
       1    5250    6850
Encroach Node=39719.21
       1    6175    6854
Encroach Node=39684
       1    6175    6854
Encroach Node=39649.03
       1    6175    6854
Encroach Node=36142.23
       1    5300    6800
Encroach Node=35256.86
       1    4100    6700
Encroach Node=29873.28
       1    4600    7000
Encroach Node=27134
       1    4000    5300
Encroach Node=24732.01
       1    3800    6800
Encroach Node=20955.56
       1    4600    6000
Encroach Node=16365.25
       1    5645    7095
Encroach Node=16326
       1    5645    7095
Encroach Node=16287.42
       1    5645    7095
Encroach Node=13420.89
       1    2900    5600
Encroach Node=10617.37
       1    2400    4200
Encroach Node=8494.126
       1    2100    3800
Encroach Node=6399.154
       1 2968.58 4823.09
Encroach Node=4829.35
       1 3065.38  6124.7
Encroach Node=97
       1 1443.57 4167.44

--- monieswamp.f01 (steady flow) ---

Flow Title=Monie Swamp
Version=September 1998 Version 2.2
Number of Profiles= 1
Profile Names=100yr
River Rch & RM=Monie Swamp,Monie Swamp     ,44753
    3270
River Rch & RM=Monie Swamp,Monie Swamp     ,44465
    3690
River Rch & RM=Monie Swamp,Monie Swamp     ,38780
    3730
River Rch & RM=Monie Swamp,Monie Swamp     ,37785
    3840
River Rch & RM=Monie Swamp,Monie Swamp     ,30115
    3910
River Rch & RM=Monie Swamp,Monie Swamp     ,29660
    5200
River Rch & RM=Monie Swamp,Monie Swamp     ,18696
    5280
River Rch & RM=Monie Swamp,Monie Swamp     ,18129
    5410
River Rch & RM=Monie Swamp,Monie Swamp     ,6209
    5510
River Rch & RM=Monie Swamp,Monie Swamp     ,5353
    5670
River Rch & RM=Monie Swamp,Monie Swamp     ,867
    5730
Boundary for River Rch & Prof#=Monie Swamp,Monie Swamp     , 1
Up Type= 0
Dn Type= 3
Dn Slope=.00005
DSS Import GetInterval= 0
DSS Import GetPeak= 0
DSS Import FillOption= 0

--- monieswamp.g01 (geometry) ---

Geom Title=Monie Swamp
Version=September 1998 Version 2.2

River Reach=Monie Swamp     ,Monie Swamp
Reach XY= 30
       2088865.7      157162.032      2088056.75      156433.969
     2088039.625      155411.469     2089140.375      153841.516
     2090685.625      153264.578     2090692.375      152527.484
       2091204.5      151989.281      2090946.75      150636.375
      2091634.25      149619.688        2089616.      147379.906
     2090024.375      146478.703       2090595.5      146409.797
        2091965.      144975.594     2092030.125      143071.359
      2091485.75      142506.844     2091411.375      140991.234
     2091776.375      140630.906     2091444.125      139538.094
      2089502.75      137539.313     2090574.625       136618.25
     2090604.875      133813.156       2091261.5      133582.578
     2091209.125      133141.703     2091645.875      132866.984
     2090782.375      130943.836       2090849.5      129936.391
       2089238.5      127374.734      2089403.75      126414.766
        2090610.      125617.352     2090713.875      123309.289

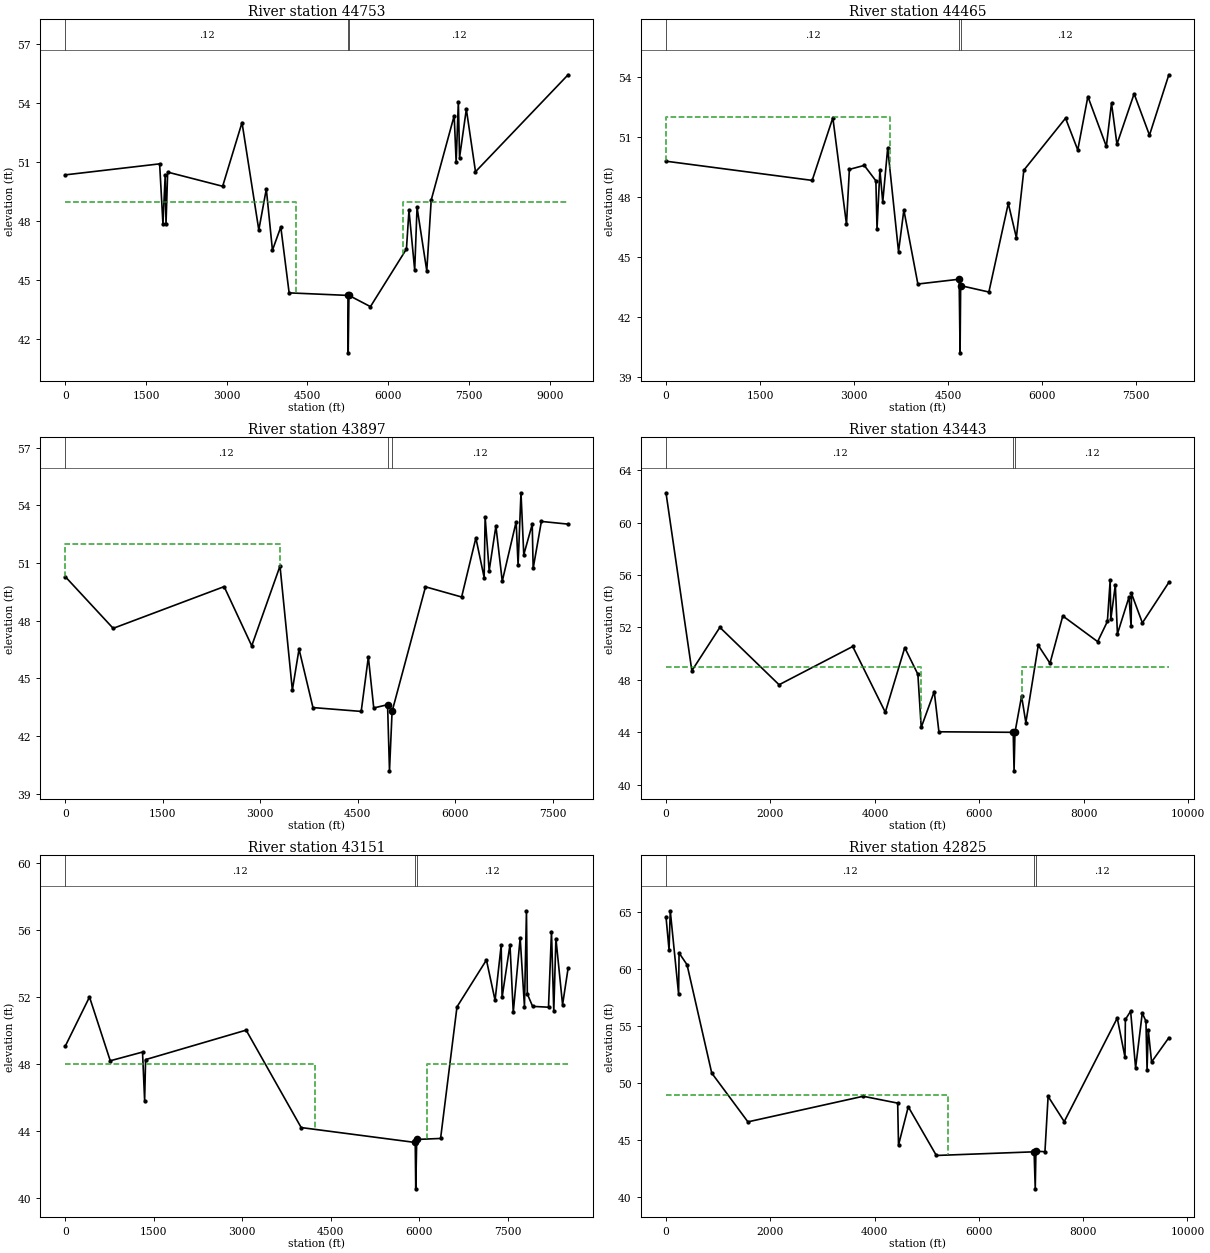
Type RM Length L Ch R = 1 ,44753   ,288.42,287.19,286.59
XS GIS Cut Line= 2
     2094123.498      157212.538 2084782.4628472  157122.7206523
#Sta/Elev= 30
       0   50.36 1753.34   50.92 1815.19   47.87 1857.22   50.35 1871.99   47.86
 1902.51    50.5 2924.16   49.78 3283.81   53.02 3595.85   47.56 3735.38   49.64
 3849.24   46.53 4004.38   47.71 4159.18   44.36 5251.28   44.23 5256.43   41.31
 5270.37   44.23 5669.72   43.66 6338.71   46.59 6385.53   48.56 6491.94   45.52
 6535.61   48.71 6716.31   45.48 6798.79   49.08 7225.71   53.37 7261.97      51
 7303.03   54.08 7325.34   51.24 7451.39    53.7 7621.44   50.52 9341.46   55.45
#Mann= 3 , 0 , 0
       0     .12       0 5251.28     .06       0 5270.37     .12       0
#XS Ineff= 2 , 0
       0    4290      49    6270       0      49
Bank Sta=5251.28,5270.37
Exp/Cntr=.3,.1

Type RM Length L Ch R = 1 ,44465   ,91.44,568.05,92.72
XS GIS Cut Line= 4
        2093350.         157132.     2093280.254        157131.9
     2093243.295      156897.829      2085531.27       156873.19
#Sta/Elev= 30
       0   49.77 2331.27   48.81 2660.96   51.94 2878.58   46.61 2924.28   49.36
 3161.94   49.56  3347.1   48.79 3365.27    46.4 3411.36   49.33 3456.57   47.73
 3535.51   50.43 3708.41   45.25  3793.3   47.33 4016.75   43.63 4674.95   43.87
 4689.96   40.19    4699   43.55 5149.11   43.23 5458.66   47.66 5587.48   45.95
 5706.47   49.32 6371.65   51.92 6566.61   50.33 6727.74      53 7022.18   50.51
 7104.65   52.67 7191.37   50.62 7465.22   53.14 7710.22   51.07 8018.77   54.09
#Mann= 3 , 0 , 0
       0     .12       0 4674.95     .06       0    4699     .12       0
#XS Ineff= 2 , 0
       0    3570      52               0
Bank Sta=4674.95,4699
Exp/Cntr=.3,.1

Type RM Length L Ch R = 1 ,43897   ,361.89,454.05,385.83
XS GIS Cut Line= 3
     2093304.893      156552.883     2090865.626      156799.273
     2085580.548      156786.954
#Sta/Elev= 30
       0   50.29  737.35    47.6  2444.6   49.77 2869.28   46.69  3304.4   50.84
 3494.37   44.39 3597.08   46.52 3811.46   43.48 4553.58   43.28  4663.6   46.11
 4746.64   43.46 4959.27   43.63 4988.91   40.19  5028.9   43.28 5542.87   49.76
 6098.84   49.23 6317.99    52.3 6445.52   50.24 6460.37    53.4 6522.55    50.6
 6626.18   52.92 6723.88   50.05 6937.67   53.14 6967.51    50.9 7012.14   54.65
 7055.02   51.43 7185.12   53.01 7199.44   50.72 7325.87   53.16 7736.77   53.02
#Mann= 3 , 0 , 0
       0     .12       0 4959.27     .06       0  5028.9     .12       0
#XS Ineff= 2 , 0
       0    3300      52               0
Bank Sta=4959.27,5028.9
Exp/Cntr=.3,.1

Type RM Length L Ch R = 1 ,43443   ,276.01,292.75,278.36
XS GIS Cut Line= 2
     2094725.934       156494.49     2085097.843      156392.471
#Sta/Elev= 30
       0   62.27  495.44   48.69 1031.75      52 2165.57   47.62 3575.55   50.54
 4199.73   45.52 4571.93   50.45 4823.15   48.42 4887.26   44.36 5136.76    47.1
 5226.02   44.03 6648.69   43.99 6665.14   41.05 6682.27   43.98 6808.95   46.75
 6890.76   44.73 7128.61   50.63 7353.16   49.26 7598.09   52.87 8265.71   50.91
  8452.1   52.45 8505.41   55.58 8517.43    52.6 8604.15   55.23 8644.45    51.5
 8866.64   54.32 8906.51   52.07  8913.4   54.59 9122.16   52.34 9628.64   55.43
#Mann= 3 , 0 , 0
       0     .12       0 6648.69     .06       0 6682.27     .12       0
#XS Ineff= 2 , 0
       0    4880      49    6820       0      49
Bank Sta=6648.69,6682.27
Exp/Cntr=.3,.1

Type RM Length L Ch R = 1 ,43151   ,337.74,325.13,311.4
XS GIS Cut Line= 2
     2094056.384      156232.575      2085531.27       156109.38
#Sta/Elev= 30
       0   49.07  411.16   52.01  763.33    48.2 1310.35   48.72 1346.02   45.82
  1362.3   48.27 3067.12   50.03  4000.5   44.21  5934.1   43.32 5943.01   40.55
 5959.68    43.5 6364.15   43.56 6642.27   51.42 7141.59   54.22 7288.04   51.81
 7391.77    55.1 7406.89   51.98 7540.86   55.13 7596.38   51.09 7713.58   55.54
 7786.29   51.44 7820.32   57.16 7834.85   52.19 7924.76   51.45 8194.04    51.4
 8244.44   55.92 8283.51   51.17 8319.64    55.5 8432.61   51.55 8526.01   53.72
#Mann= 3 , 0 , 0
       0     .12       0  5934.1     .06       0 5959.68     .12       0
#XS Ineff= 2 , 0
       0    4230      48    6130       0      48
Bank Sta=5934.1,5959.68
Exp/Cntr=.3,.1

Type RM Length L Ch R = 1 ,42825   ,269.57,409.41,407
XS GIS Cut Line= 4
 2095147.7207104  155964.7545558     2092781.928      155813.575
     2085528.955      155842.645 2085508.9551606  155842.7251596
#Sta/Elev= 30
       0   64.56   58.65   61.66      82   65.08     242   57.78  250.85   61.39
  403.63   60.36  877.39   50.88 1571.32   46.61 3781.72   48.85 4443.48   48.25
 4459.36   44.58 4646.53   47.93 5185.17   43.67 7059.93   43.99 7081.76   40.75
 7094.82   44.04  7267.7      44  7328.6   48.84 7637.36   46.63 8654.53   55.69
 8803.12   52.27 8810.23   55.57 8910.98   56.29 9006.39   51.33  9134.1   56.13
 9204.97   55.42 9226.14   51.18  9249.2   54.65 9312.76   51.85 9643.65   53.97
#Mann= 3 , 0 , 0
       0     .12       0 7059.93     .06       0 7094.82     .12       0
#XS Ineff= 2 , 0
       0    5400      49               0
Bank Sta=7059.93,7094.82
Exp/Cntr=.3,.1

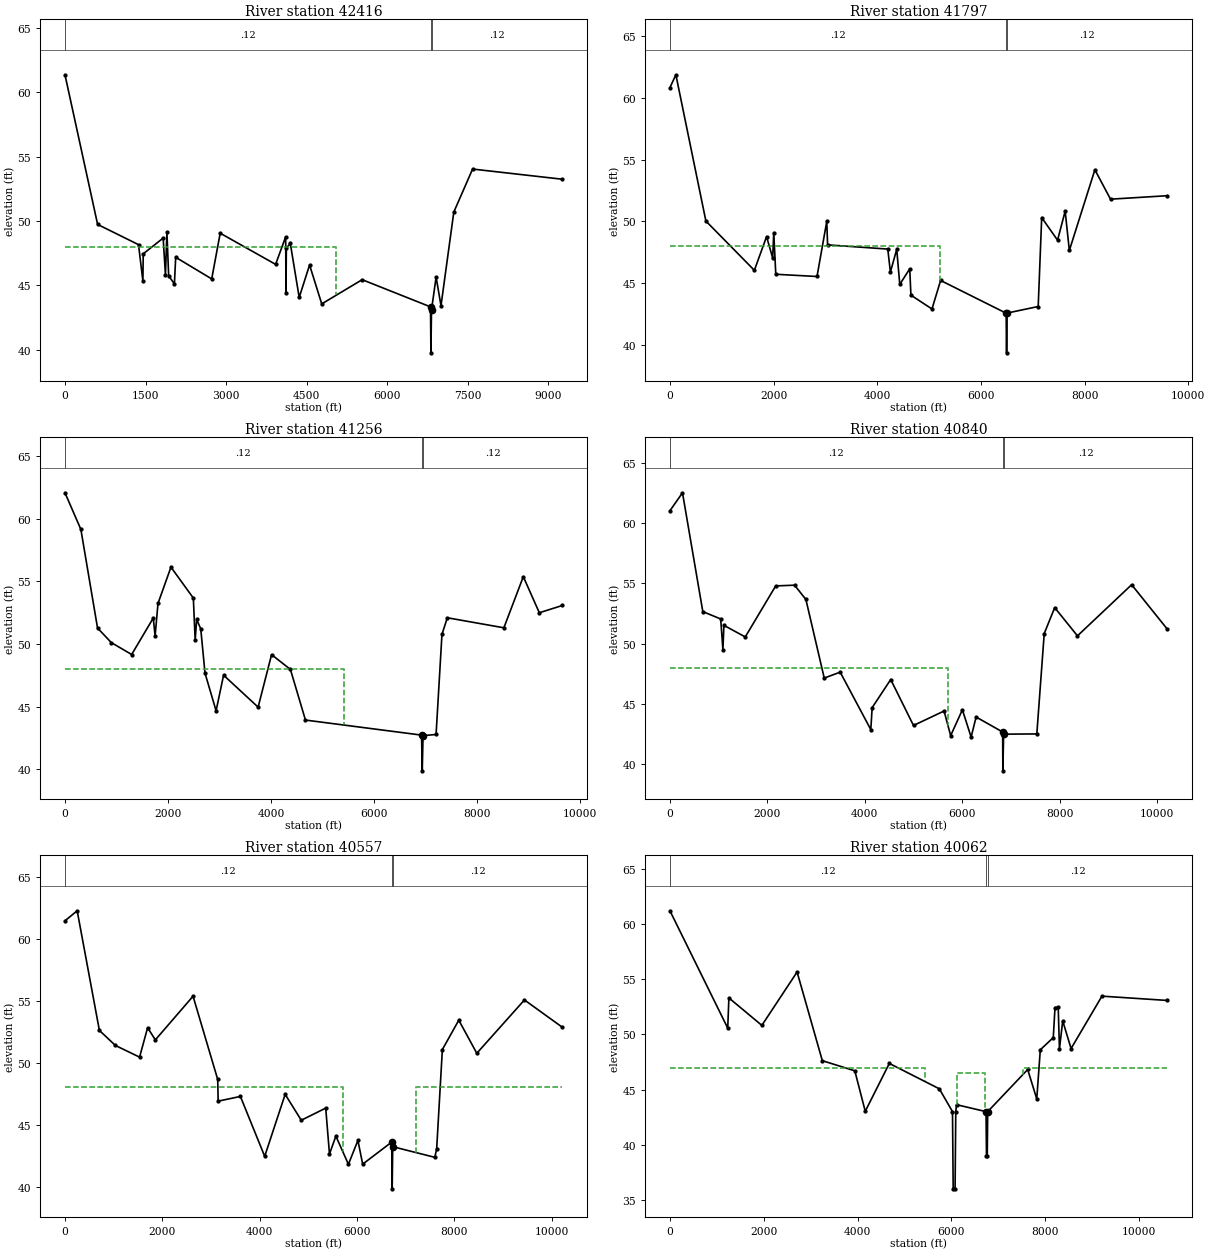
Type RM Length L Ch R = 1 ,42416   ,283.36,619.51,405.15
XS GIS Cut Line= 6
     2094829.123      155924.542        2093030.         155814.
        2091870.         155753.     2091169.774      155770.139
     2087139.858      155337.811     2085595.829      155384.132
#Sta/Elev= 30
       0   61.35  607.98   49.73 1369.77   48.16 1451.49   45.33 1457.54   47.45
  1828.8   48.67 1871.21   45.82 1898.65   49.13 1930.94   45.74 2038.29   45.11
 2062.01   47.18 2732.98    45.5 2890.87   49.05 3922.99   46.63 4110.36   48.77
 4116.01   44.37 4123.04   47.88 4196.25   48.27 4362.32   44.06  4555.6   46.58
 4781.99   43.56 5535.06   45.44 6807.81   43.33 6815.13   39.76 6826.33   43.09
 6912.06   45.64 7003.21   43.42 7241.71   50.69 7591.58   54.03 9262.32   53.24
#Mann= 3 , 0 , 0
       0     .12       0 6807.81     .06       0 6826.33     .12       0
#XS Ineff= 2 , 0
       0    5050      48               0
Bank Sta=6807.81,6826.33
Exp/Cntr=.3,.1

Type RM Length L Ch R = 1 ,41797   ,213.08,540.13,402.63
XS GIS Cut Line= 4
     2094942.726      155907.878     2091384.795      155703.839
     2086985.204      154823.921     2085461.288       155078.97
#Sta/Elev= 30
       0   60.83  114.62   61.87   693.8   50.03 1628.99   46.04 1864.55   48.77
 1982.29   47.04 2003.18   49.09 2042.39   45.72 2837.83   45.54 3026.09      50
 3041.95    48.1 4203.22   47.76 4253.68    45.9 4375.88   47.74 4434.62    44.9
 4626.77   46.16 4649.76   44.03 5055.95   42.91 5222.73   45.22 6486.63   42.57
 6495.42   39.36 6505.82   42.58 7105.46   43.11 7172.92   50.31 7478.97   48.48
 7625.52   50.83 7706.41   47.65  8199.1   54.18 8500.73    51.8 9595.61   52.08
#Mann= 3 , 0 , 0
       0     .12       0 6486.63     .06       0 6505.82     .12       0
#XS Ineff= 2 , 0
       0    5210      48               0
Bank Sta=6486.63,6505.82
Exp/Cntr=.3,.1

Type RM Length L Ch R = 1 ,41256   ,219.97,416.38,370
XS GIS Cut Line= 6
     2094860.004      155878.221     2092744.684      154828.282
     2090860.968      155399.572     2089749.267      155229.729
     2087711.149      154488.595     2085703.911      154781.961
#Sta/Elev= 30
       0   62.06  308.49   59.14   632.1   51.27  899.02   50.11 1294.14   49.16
 1713.65   52.07 1749.31   50.64 1805.17   53.23 2056.81   56.13 2491.36   53.66
 2526.76   50.32 2556.53   51.96 2635.11    51.2 2717.93   47.67 2932.73   44.67
 3078.17   47.51 3748.35   44.96 4009.64   49.15 4375.14   47.97 4667.17   43.93
 6920.38   42.73 6933.82   39.88 6949.34   42.69 7202.22   42.78 7316.37   50.76
 7420.38   52.09 8518.12   51.29 8895.01   55.37 9205.93   52.49 9651.86   53.07
#Mann= 3 , 0 , 0
       0     .12       0 6920.38     .06       0 6949.34     .12       0
#XS Ineff= 2 , 0
       0    5410      48               0
Bank Sta=6920.38,6949.34
Exp/Cntr=.3,.1

Type RM Length L Ch R = 1 ,40840   ,198.43,282.68,311.36
XS GIS Cut Line= 5
     2094942.726      155856.868     2092749.306      154441.348
     2089765.236      155053.465      2087954.39      154135.289
     2085486.793      154645.387
#Sta/Elev= 30
       0   61.02  257.75   62.51  674.88   52.66 1041.65   52.05 1087.58    49.5
  1107.8   51.52 1545.92   50.56  2170.4   54.79 2557.35   54.85 2790.28   53.67
 3166.87   47.15 3494.08   47.64 4122.45   42.88 4150.46    44.7 4530.97   47.03
 4998.88   43.22 5626.48   44.42  5761.3   42.38 6002.25   44.52 6181.19   42.26
  6283.9   43.92 6828.35   42.68 6832.48   39.46 6848.76    42.5 7529.74   42.52
 7681.69   50.84 7896.73   52.99 8363.89   50.65 9475.74   54.89 10206.8   51.21
#Mann= 3 , 0 , 0
       0     .12       0 6828.35     .06       0 6848.76     .12       0
#XS Ineff= 2 , 0
       0    5710      48               0
Bank Sta=6828.35,6848.76
Exp/Cntr=.3,.1

Type RM Length L Ch R = 1 ,40557   ,396.69,494.95,499.92
XS GIS Cut Line= 6
     2094937.205       155816.46     2092605.721      154272.431
     2089780.148      154874.602     2088452.283      154025.386
     2086769.291      154334.192     2085534.068      154504.035
#Sta/Elev= 30
       0   61.43  250.91   62.24  707.41   52.59 1036.33   51.38 1532.96   50.44
 1698.25   52.81 1856.89   51.83 2631.86   55.35 3138.77   48.64 3147.95   46.89
 3605.01   47.27  4104.1   42.44 4524.67   47.44 4855.85   45.35  5358.2   46.33
  5435.3   42.63 5567.17   44.07 5824.44    41.8 6019.58   43.72 6117.76   41.81
 6714.37   43.59 6723.97   39.82 6734.81   43.22 7599.57   42.36 7637.83   43.03
 7755.05   51.05 8092.58   53.42 8462.69   50.75 9441.75   55.0510219.74   52.85
#Mann= 3 , 0 , 0
       0     .12       0 6714.37     .06       0 6734.81     .12       0
#XS Ineff= 2 , 0
       0    5710      48    7210       0      48
Bank Sta=6714.37,6734.81
Exp/Cntr=.5,.3

Type RM Length L Ch R = 1 ,40062   ,84.2,66.53,66
XS GIS Cut Line= 6
 2095009.3615888  155856.2763323     2094220.186      154929.968
     2092444.475      154105.254      2089967.51      154488.334
     2088674.353      153616.352  2085465.976328  154360.0850247
#Sta/Elev= 30
       0   61.21 1232.62   50.57 1257.09   53.31 1959.95   50.82 2711.54   55.66
 3249.16   47.62 3942.23    46.7 4164.61   43.03 4678.24   47.37  5743.9   45.07
    6025      43    6040      36    6080      36    6095      43 6110.98   43.63
    6740      43    6750      39    6766      39    6776      43  7628.4   46.82
 7821.85   44.15 7897.42   48.61 8173.84   49.71 8210.85   52.44 8279.22   52.46
 8305.49   48.69 8375.14   51.23 8553.47   48.72  9211.8   53.4710604.42   53.08
#Mann= 3 , 0 , 0
       0     .12       0    6740     .06       0    6776     .12       0
#XS Ineff= 3 ,-1
       0    5430      47    6115    6720    46.5    7525   11000      47
Bank Sta=6740,6776
Exp/Cntr=.5,.3

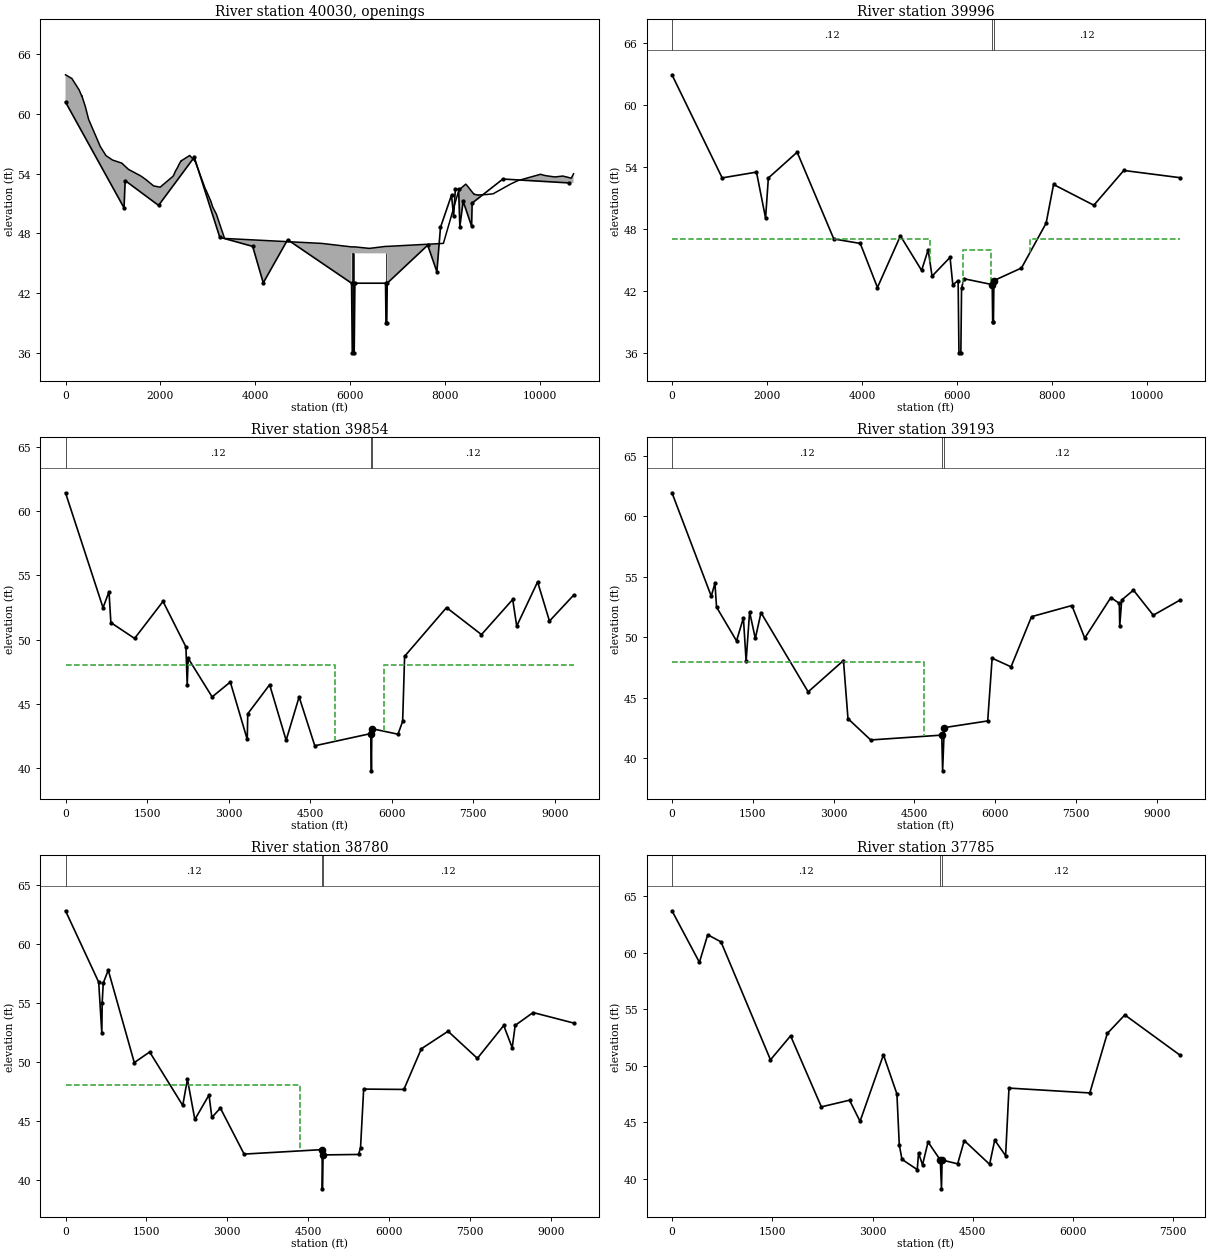
Type RM Length L Ch R = 4 ,40030   ,,,
BEGIN DESCRIPTION:
SR 1158 -- Columbus County Bridges 325, 324 (left to right)
END DESCRIPTION:
Bridge Culvert--1,0,-1,-1, 0
Deck Dist Width WeirC Skew NumUp NumDn MinLoCord MaxHiCord MaxSubmerge Is_Ogee
20,25.3,2.6,0,81,81,,,.95,0,0,0,,
       0   36.46  105.57  132.42   285.6  344.76  345.56  418.54  485.03   485.1
  554.17  727.05  727.37  851.62  989.99 1185.85 1227.77 1326.83 1562.75 1606.73
 1706.42 1706.67 1856.07 1992.93 2269.08 2306.97 2307.67 2372.23 2374.57  2433.2
  2433.3 2615.29  2719.8 2721.07 2811.68 2811.85  2941.1 2941.35 2941.54 2958.21
    2971 3064.51 3098.17 3180.73 3180.98    3350    5400    6025    6025    6095
    6095    6400    6740    6740    6776    6776 7955.75 7957.87 7958.89 8272.16
  8311.6 8429.01 8460.38 8562.23 8606.49 8607.01 8691.18 8693.06 8884.07 9007.56
 9379.41 9551.75 9556.2510005.6810038.1410111.2910113.8610304.0910474.2310652.92
   10700
   63.95   63.85   63.65   63.59   62.44   61.79   61.82   60.74    59.5   59.49
   58.72    56.8   56.78   55.83   55.38   55.07   54.88   54.44   53.84   53.71
   53.37   53.36   52.78   52.65   53.77   54.16    54.2   54.74    54.8    55.3
   55.29   55.84   55.31   55.39   54.22   54.21   52.53    52.5   52.49   52.37
   52.23    51.2   50.68   49.91   49.89    47.5      47   46.65   46.65   46.65
   46.65    46.5    46.7    46.7    46.7    46.7      47      47      47   52.16
   52.47   52.96    52.8   52.18   51.93   51.94   51.85   51.87   51.92   51.99
   52.98   53.36   53.35   53.95    53.9   53.81   53.81   53.68   53.77   53.56
      54
                                                                                
                                                                                
                                                                                
                                                                                
                                                                      46      46
                              46      46
                                                                                
                                                                                
        
       0   36.46  105.57  132.42   285.6  344.76  345.56  418.54  485.03   485.1
  554.17  727.05  727.37  851.62  989.99 1185.85 1227.77 1326.83 1562.75 1606.73
 1706.42 1706.67 1856.07 1992.93 2269.08 2306.97 2307.67 2372.23 2374.57  2433.2
  2433.3 2615.29  2719.8 2721.07 2811.68 2811.85  2941.1 2941.35 2941.54 2958.21
    2971 3064.51 3098.17 3180.73 3180.98    3350    5400    6025    6025    6095
    6095    6400    6740    6740    6776    6776 7955.75 7957.87 7958.89 8272.16
  8311.6 8429.01 8460.38 8562.23 8606.49 8607.01 8691.18 8693.06 8884.07 9007.56
 9379.41 9551.75 9556.2510005.6810038.1410111.2910113.8610304.0910474.2310652.92
   10700
   63.95   63.85   63.65   63.59   62.44   61.79   61.82   60.74    59.5   59.49
   58.72    56.8   56.78   55.83   55.38   55.07   54.88   54.44   53.84   53.71
   53.37   53.36   52.78   52.65   53.77   54.16    54.2   54.74    54.8    55.3
   55.29   55.84   55.31   55.39   54.22   54.21   52.53    52.5   52.49   52.37
   52.23    51.2   50.68   49.91   49.89    47.5      47   46.65   46.65   46.65
   46.65    46.5    46.7    46.7    46.7    46.7      47      47      47   52.16
   52.47   52.96    52.8   52.18   51.93   51.94   51.85   51.87   51.92   51.99
   52.98   53.36   53.35   53.95    53.9   53.81   53.81   53.68   53.77   53.56
      54
                                                                                
                                                                                
                                                                                
                                                                                
                                                                      46      46
                              46      46
                                                                                
                                                                                
        
Pier Skew, UpSta & Num, DnSta & Num=,6044, 2 ,6044, 2 , 0 , 0 , 0 ,,
       2       2
      20      49
       2       2
      20      49
Pier Skew, UpSta & Num, DnSta & Num=,6062, 2 ,6062, 2 , 0 , 0 , 0 ,,
       2       2
      20      49
       2       2
      20      49
Pier Skew, UpSta & Num, DnSta & Num=,6079, 2 ,6079, 2 , 0 , 0 , 0 ,,
       2       2
      20      49
       2       2
      20      49
Pier Skew, UpSta & Num, DnSta & Num=,6759, 2 ,6759, 2 , 0 , 0 , 0 ,,
       2       2
      20      49
       2       2
      20      49
BR Coef=-1 , 1 , 0 ,, 0 ,,,.8,0,1.2,0,
WSPro=,,,, 1 ,,,, 0 ,,,, 0 ,,,,-1 ,-1 ,-1 , 0 , 0 , 0 , 0 , 0
BC Mult= 3 ,0,6600,0,6600
BC Mult= 3 ,6300,10800,6300,10800
BR U #Sta/Elev= 30
       0   61.21 1232.62   50.57 1257.09   53.31 1959.95   50.82 2711.54   55.66
 3249.16   47.62 3942.23    46.7 4164.61   43.03 4678.24   47.37    6025      43
    6040      36    6080      36    6095      43    6740      43    6750      39
    6766      39    6776      43  7628.4   46.82 7821.85   44.15 7897.42   48.61
 8129.86   51.85 8173.84   49.71 8210.85   52.44 8279.22   52.46 8305.49   48.69
 8375.14   51.23 8553.47   48.72 8564.55   51.05  9211.8   53.4710604.42   53.08
BR U #Mann= 5
       0     .12    6025     .05    6095     .12    6740     .05    6776     .12
BR D #Sta/Elev= 30
       0   62.94 1056.57   52.95 1778.57   53.51    1970   49.06 2028.66   52.94
 2634.88   55.44 3406.38   47.03 3962.91    46.6  4324.6   42.33 4808.24   47.33
 5254.01   43.99 5391.94   45.98 5474.01   43.43 5852.64   45.25 5910.76   42.59
    6025    42.8    6040      36    6080      36    6095    42.3    6740   42.61
    6750      39    6766      39    6776      43 7355.98   44.22 7675.31   49.32
 7874.72   48.56 8031.26   52.31 8878.85    50.3 9509.24   53.6710692.74   52.97
BR D #Mann= 5
       0     .12    6025     .05    6095     .12    6740     .05    6776     .12
BC Design=,, 0 ,, 0 ,,,,,,

Type RM Length L Ch R = 1 ,39996   ,156.14,142.1,142
XS GIS Cut Line= 6
     2095046.846      155801.128       2094259.4      154864.357
     2092483.618      154055.426     2089984.847      154437.869
     2088694.101      153549.441     2085426.147       154310.03
#Sta/Elev= 30
       0   62.94 1056.57   52.95 1778.57   53.51    1970   49.06 2028.66   52.94
 2634.88   55.44 3406.38   47.03 3962.91    46.6  4324.6   42.33 4808.24   47.33
 5254.01   43.99 5391.94   45.98 5474.01   43.43 5852.64   45.25 5910.76   42.59
 6022.76      43    6040      36    6080      36    6095    42.3 6145.56   43.18
    6740   42.61    6750      39    6766      39    6776      43 7355.98   44.22
 7874.72   48.56 8031.26   52.31 8878.85    50.3 9509.24   53.6710692.74   52.97
#Mann= 3 , 0 , 0
       0     .12       0    6740     .06       0    6776     .12       0
#XS Ineff= 3 ,-1
       0    5430      47    6115    6720      46    7525   11000      47
Bank Sta=6740,6776
Exp/Cntr=.5,.3

Type RM Length L Ch R = 1 ,39854   ,403.06,660.51,357.18
XS GIS Cut Line= 4
      2094674.72       153701.14     2090027.193      154303.312
     2088699.328      153361.454     2085734.792      153979.066
#Sta/Elev= 30
       0   61.42  690.14   52.48  799.95   53.72   834.2   51.32 1270.48   50.09
 1793.12   52.97 2214.26   49.43 2237.77   46.47 2256.63   48.54 2696.45   45.54
 3030.61    46.7 3342.09   42.23 3351.59   44.23 3753.91   46.49 4057.31   42.17
 4296.03   45.54  4584.3   41.74 5614.87   42.69 5625.58   39.79 5633.55   43.07
 6114.17   42.64 6199.83   43.64    6236    48.7 7006.51   52.49 7648.98   50.39
 8223.59   53.12 8297.53   51.05 8681.62   54.49 8899.68   51.44 9342.54   53.45
#Mann= 3 , 0 , 0
       0     .12       0 5614.87     .06       0 5633.55     .12       0
#XS Ineff= 2 , 0
       0    4950      48    5850       0      48
Bank Sta=5614.87,5633.55
Exp/Cntr=.3,.1

Type RM Length L Ch R = 1 ,39193   ,484.89,413.08,390.42
XS GIS Cut Line= 4
     2094736.481      153562.178      2090428.64      154087.148
     2088977.253      153237.932      2085642.15      153932.745
#Sta/Elev= 30
       0   61.94  729.27    53.4  797.39   54.47  827.03    52.5 1197.94   49.71
 1325.61   51.61 1375.88   48.04 1440.59    52.1  1546.6   49.91 1652.15   52.04
 2527.22    45.5 3182.52   48.09 3266.24   43.29 3687.63   41.53 5006.26   41.93
 5022.41   38.98  5053.4   42.55 5859.03    43.1 5941.54   48.28 6292.56   47.57
 6672.25   51.71 7421.54   52.63  7659.6   49.94  8144.4   53.29 8301.42   52.81
 8309.29   50.94 8346.89   53.09 8563.72    53.9 8932.23   51.83 9427.99   53.08
#Mann= 3 , 0 , 0
       0     .12       0 5006.26     .06       0  5053.4     .12       0
#XS Ineff= 2 , 0
       0    4680      48               0
Bank Sta=5006.26,5053.4
Exp/Cntr=.3,.1

Type RM Length L Ch R = 1 ,38780   ,951.86,995.67,503.23
XS GIS Cut Line= 4
     2094764.192      153331.886     2090772.678      153778.221
     2089344.405      153089.589     2085601.565      153867.488
#Sta/Elev= 30
       0   62.83  615.59   56.77  673.68   52.44  680.52   55.02  700.29   56.69
  792.76   57.79 1276.08   49.94 1561.42   50.84 2175.04    46.3 2261.55   48.53
 2399.45   45.11 2662.31   47.19 2715.18   45.28  2872.5   46.08  3313.3   42.17
 4759.54   42.55 4765.23   39.22 4778.39    42.1 5437.12   42.14 5473.29   42.72
 5531.06   47.69 6277.39   47.66 6600.76   51.11  7096.8    52.6 7640.41    50.3
 8129.64   53.09 8286.73    51.2 8342.25    53.1 8674.44   54.19 9424.83    53.3
#Mann= 3 , 0 , 0
       0     .12       0 4759.54     .06       0 4778.39     .12       0
#XS Ineff= 2 , 0
       0    4350      48               0
Bank Sta=4759.54,4778.39
Exp/Cntr=.3,.1

Type RM Length L Ch R = 1 ,37785   ,258.89,262.27,272.1
XS GIS Cut Line= 3
 2094755.9339578  152949.2626662     2094725.934      152949.313
 2087155.4809578  152962.0146662
#Sta/Elev= 30
       0    63.7  410.66   59.14  534.74   61.58  733.62   60.95 1473.77   50.52
 1774.53   52.64 2234.77   46.36 2655.97   46.95 2813.72   45.08 3163.27   50.96
 3365.14    47.5 3400.47   43.01 3440.73   41.72 3669.44   40.81 3688.69   42.28
 3748.36   41.23 3831.04   43.25 4014.18   41.66 4032.04   39.11 4041.28   41.66
 4274.12   41.32  4372.7   43.38 4751.83   41.28 4828.74   43.42 4991.22   42.04
 5041.87   48.02 6250.88   47.59 6512.49   52.85 6774.66   54.49 7600.47   50.93
#Mann= 3 , 0 , 0
       0     .12       0 4014.18     .06       0 4041.28     .12       0
Bank Sta=4014.18,4041.28
Exp/Cntr=.3,.1

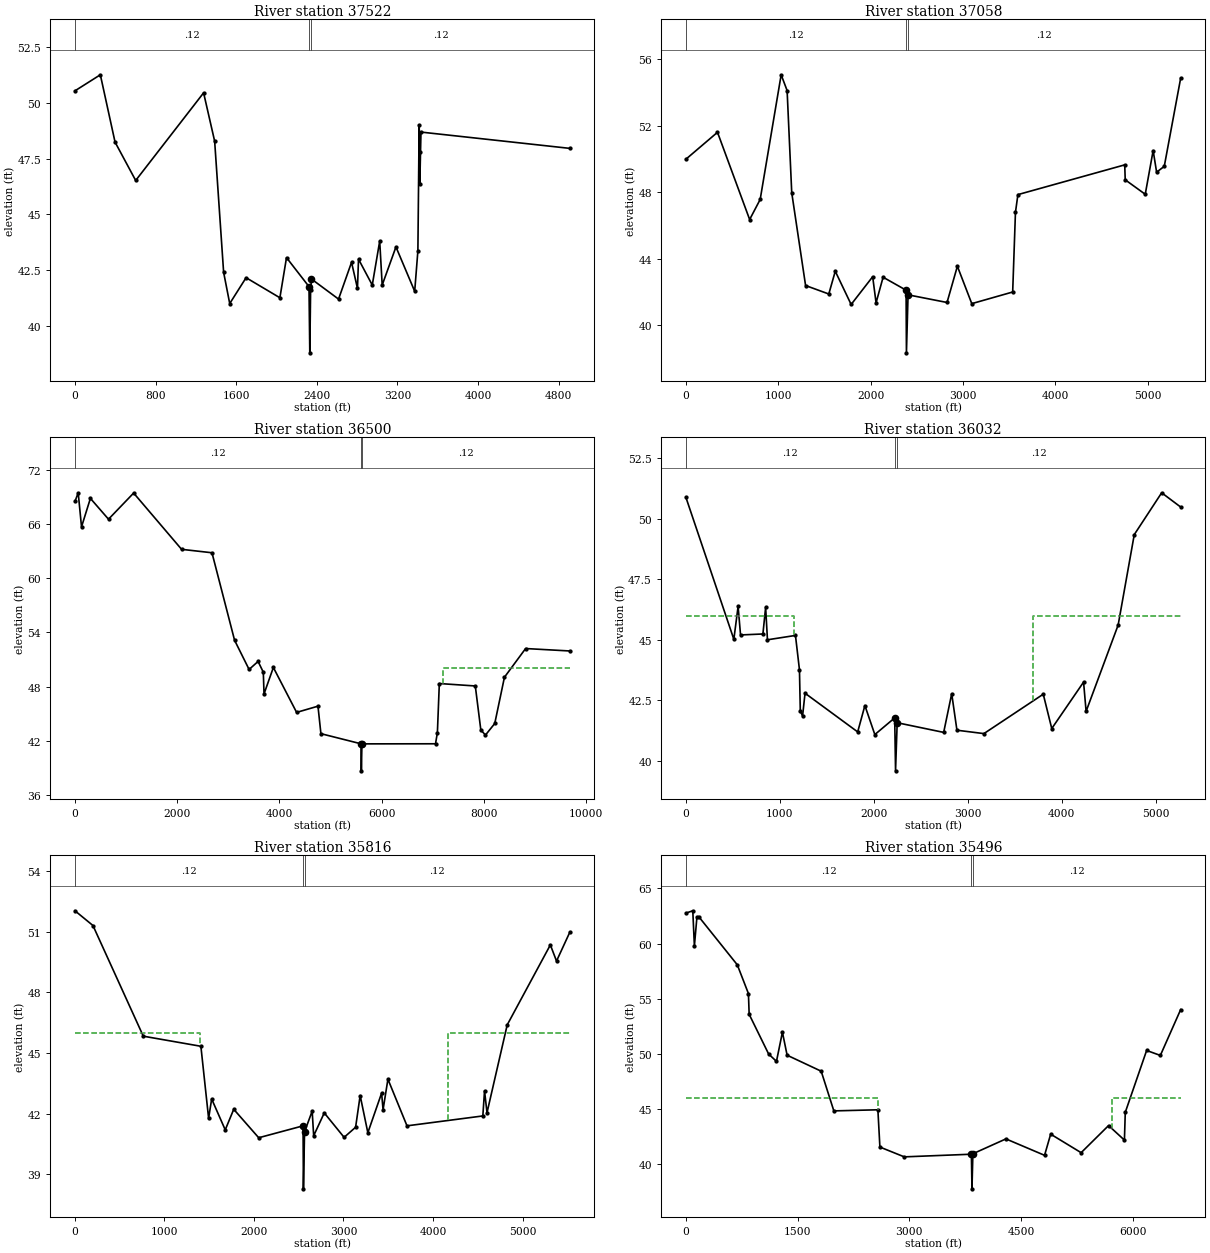
Type RM Length L Ch R = 1 ,37522   ,327.53,464.23,327.73
XS GIS Cut Line= 2
     2093115.251      152712.962     2088205.238      152712.962
#Sta/Elev= 30
       0   50.54  251.81   51.26  397.79   48.24  602.61   46.52 1276.51   50.45
 1386.24   48.28 1475.28    42.4 1535.77      41 1698.16   42.16 2033.63   41.26
 2099.22   43.06 2322.44   41.76 2330.39   38.79 2338.42    41.6 2346.99    42.1
 2615.76    41.2 2744.74   42.85 2803.42   41.68 2813.91   42.99 2950.37   41.83
 3024.11    43.8 3048.87   41.83 3185.39   43.54 3371.42   41.55 3403.16   43.37
 3415.51   48.99  3421.8   47.79 3422.15   46.38 3433.74   48.69 4910.01   47.96
#Mann= 3 , 0 , 0
       0     .12       0 2322.44     .06       0 2346.99     .12       0
Bank Sta=2322.44,2346.99
Exp/Cntr=.3,.1

Type RM Length L Ch R = 1 ,37058   ,435.74,557.71,412.56
XS GIS Cut Line= 2
     2093269.654      152404.156     2087911.873      152388.716
#Sta/Elev= 30
       0   49.98  342.03    51.6  690.24   46.35  804.28   47.56 1031.51   55.06
 1095.93   54.11 1146.06   47.96 1295.95   42.38 1547.32   41.87 1617.42   43.24
 1789.27   41.24 2022.51   42.91 2059.26   41.34  2135.4   42.88 2384.22    42.1
 2388.09   38.33 2405.65   41.82 2827.68   41.36 2939.72   43.54 3095.72   41.29
 3538.58   41.99 3568.59   46.78 3595.18   47.85 4751.95   49.64 4757.24   48.74
 4974.07   47.87 5059.67    50.5 5097.21    49.2 5180.09   49.55  5357.8   54.86
#Mann= 3 , 0 , 0
       0     .12       0 2384.22     .06       0 2405.65     .12       0
Bank Sta=2384.22,2405.65
Exp/Cntr=.3,.1

Type RM Length L Ch R = 1 ,36500   ,383.78,468.58,380.16
XS GIS Cut Line= 2
     2096809.831      151939.616      2087132.56      152012.929
#Sta/Elev= 30
       0   68.52   63.28   69.48  128.16    65.7  301.78   68.86  655.96   66.55
 1147.57   69.45  2085.4   63.21 2679.81   62.83  3121.7   53.13 3405.95   49.89
  3581.6   50.78 3683.83   49.59 3698.06   47.18 3880.53   50.11 4335.41   45.13
 4753.12   45.82 4810.57   42.77 5593.63   41.65 5601.75   38.65 5612.99   41.64
 7052.05   41.65 7088.95   42.88 7126.73   48.33 7830.27   48.06 7938.71   43.17
  8029.7   42.62 8210.93    43.9 8400.47   49.03  8814.4   52.21 9677.56   51.94
#Mann= 3 , 0 , 0
       0     .12       0 5593.63     .06       0 5612.99     .12       0
#XS Ineff= 2 , 0
       0                    7200       0      50
Bank Sta=5593.63,5612.99
Exp/Cntr=.3,.1

Type RM Length L Ch R = 1 ,36032   ,220.13,215.39,208.2
XS GIS Cut Line= 2
     2093207.892      151616.701     2087942.753      151601.261
#Sta/Elev= 30
       0   50.89  510.13   45.02  555.43   46.38  581.45    45.2  819.38   45.24
  848.45   46.34  867.79      45 1165.83   45.18  1208.4   43.76 1217.31   42.05
 1241.56   41.85 1267.69   42.79 1828.03   41.19  1904.6   42.28 2010.45   41.08
  2221.9   41.77 2230.89   39.58 2248.22   41.57 2743.14   41.17 2828.53   42.77
 2884.22   41.26  3171.2   41.12 3802.76   42.75 3893.21   41.33  4231.8   43.25
 4258.74   42.04 4599.79   45.61 4771.24   49.35 5062.93   51.08 5265.16   50.49
#Mann= 3 , 0 , 0
       0     .12       0  2221.9     .06       0 2248.22     .12       0
#XS Ineff= 2 , 0
       0    1155      46    3690       0      46
Bank Sta=2221.9,2248.22
Exp/Cntr=.3,.1

Type RM Length L Ch R = 1 ,35816   ,322.72,320.11,313.57
XS GIS Cut Line= 2
     2093501.258      151400.537     2087973.634      151400.537
#Sta/Elev= 30
       0   52.04  200.83   51.31  763.34   45.83  1406.8   45.33 1493.18   41.76
 1527.23   42.72  1678.9   41.19 1773.73   42.21 2052.83    40.8 2548.24   41.39
 2552.43   38.27 2564.82   41.09 2650.08   42.12 2666.85    40.9 2785.25   42.03
 3006.89   40.82 3135.24   41.32 3186.14   42.89 3272.05   41.05 3425.86   43.01
 3442.13   42.19 3496.37    43.7 3709.42   41.39 4556.75   41.88 4575.78   43.12
 4603.37   42.04 4829.12   46.39 5311.09   50.35 5380.01   49.55 5527.63   50.97
#Mann= 3 , 0 , 0
       0     .12       0 2548.24     .06       0 2564.82     .12       0
#XS Ineff= 2 , 0
       0    1400      46    4170       0      46
Bank Sta=2548.24,2564.82
Exp/Cntr=.3,.1

Type RM Length L Ch R = 1 ,35496   ,310.56,309.74,305.06
XS GIS Cut Line= 3
     2094733.182      151087.457     2094713.182      151087.457
     2088089.161      151087.457
#Sta/Elev= 30
       0   62.76   92.42   62.97  113.96   59.78  148.22   62.42  180.21   62.37
  689.93   58.07   839.6   55.46  849.37   53.58 1110.81   49.98 1216.02   49.31
 1295.97   51.96 1358.98   49.87 1816.65   48.42 1986.57   44.82 2578.02   44.92
 2605.01   41.54 2932.11   40.65  3833.6   40.89  3841.5   37.75 3853.53   40.93
 4297.25   42.28 4816.21   40.79 4898.18   42.71  5307.3   41.03 5675.91   43.49
 5888.61   42.17 5900.06   44.69 6186.78    50.3 6371.06   49.85 6644.03   54.01
#Mann= 3 , 0 , 0
       0     .12       0  3833.6     .06       0 3853.53     .12       0
#XS Ineff= 2 , 0
       0    2578      46    5720       0      46
Bank Sta=3833.6,3853.53
Exp/Cntr=.3,.1

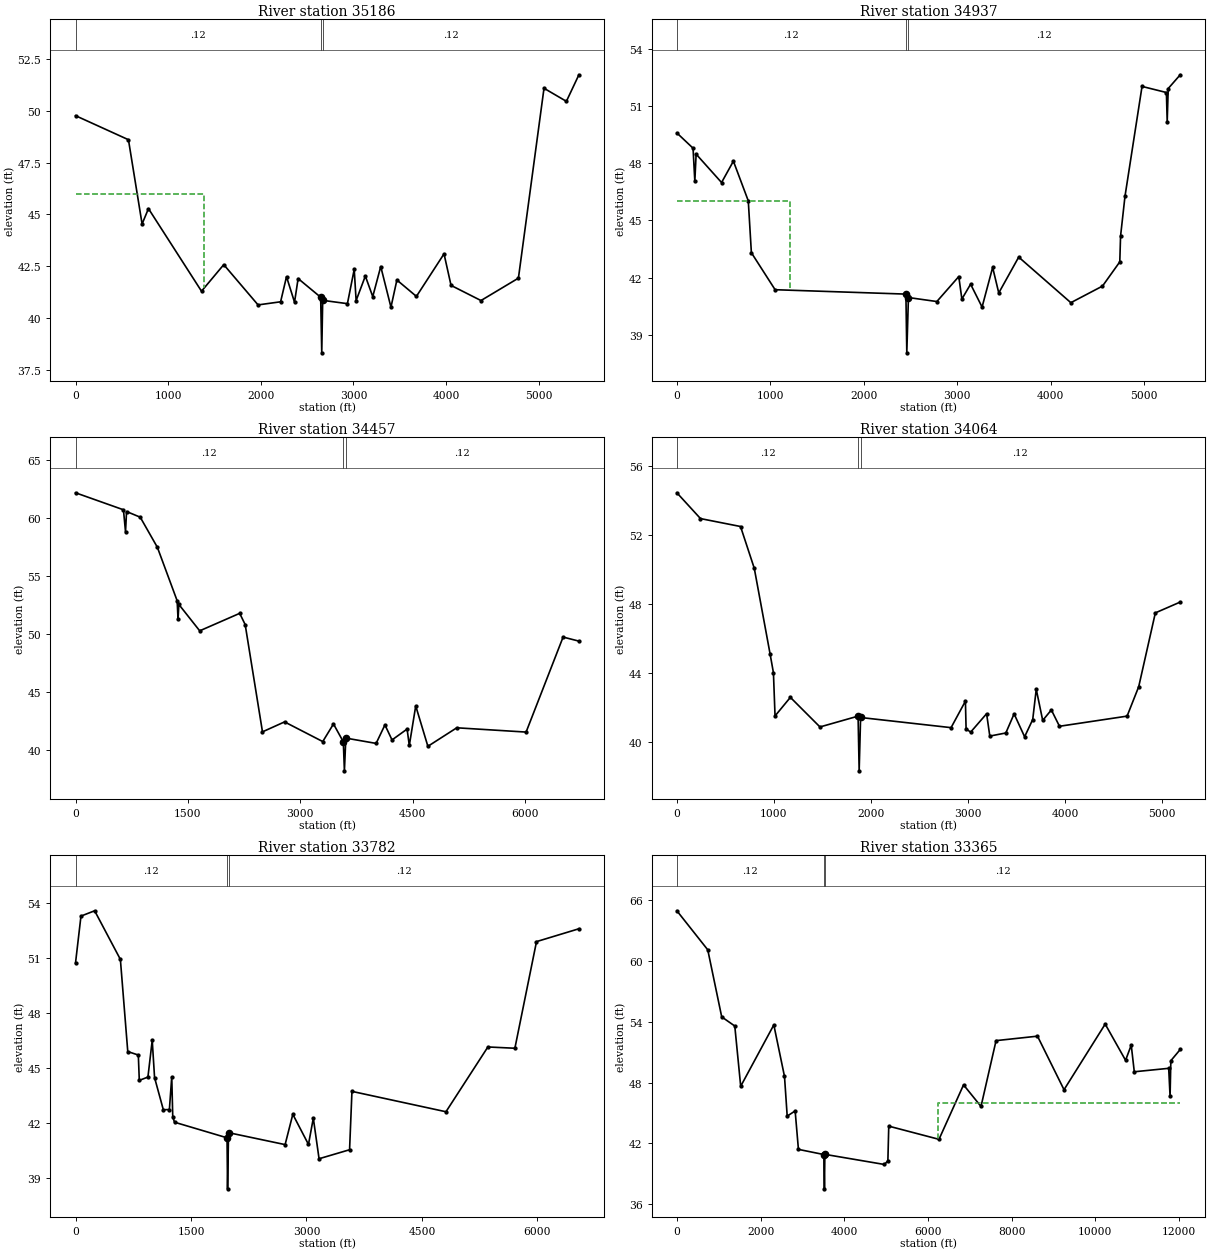
Type RM Length L Ch R = 1 ,35186   ,242.27,249.13,229.82
XS GIS Cut Line= 2
     2093578.459      150782.925     2088143.477      150782.925
#Sta/Elev= 30
       0   49.76  571.46    48.6  718.67   44.54  787.54   45.28 1360.23    41.3
 1600.47   42.58 1970.72   40.64  2214.2   40.79 2278.03      42  2364.6   40.77
 2403.37   41.91 2646.84   41.01 2658.52   38.33 2668.58   40.86 2935.61    40.7
 3009.02   42.35 3029.63   40.85 3129.06   42.03  3209.2   41.04  3295.4   42.49
 3405.67   40.53 3469.79   41.84 3680.56   41.05  3978.7    43.1  4054.5   41.58
 4377.65   40.85  4781.9   41.93 5058.13   51.08 5299.82   50.45 5434.98   51.73
#Mann= 3 , 0 , 0
       0     .12       0 2646.84     .06       0 2668.58     .12       0
#XS Ineff= 2 , 0
       0    1390      46               0
Bank Sta=2646.84,2668.58
Exp/Cntr=.3,.1

Type RM Length L Ch R = 1 ,34937   ,369.11,480,375.78
XS GIS Cut Line= 2
     2093454.937      150535.881     2088066.276      150566.761
#Sta/Elev= 30
       0   49.58  173.33   48.78  192.35   47.04  206.09   48.47  478.52   46.98
  605.16    48.1  764.52   46.02   797.7    43.3 1051.68   41.36 2451.88   41.13
  2461.5   38.05 2478.82   40.95 2783.19   40.74 3017.93   42.05 3051.05   40.87
 3144.45   41.65 3267.33   40.45 3380.54   42.53 3445.94   41.19 3659.44   43.07
  4217.6   40.68 4556.34   41.55 4741.55   42.82 4749.79   44.17 4796.96   46.25
  4979.7   52.02 5240.54    51.7 5249.08   50.18 5260.02   51.91 5388.75   52.63
#Mann= 3 , 0 , 0
       0     .12       0 2451.88     .06       0 2478.82     .12       0
#XS Ineff= 2 , 0
       0    1210      46               0
Bank Sta=2451.88,2478.82
Exp/Cntr=.3,.1

Type RM Length L Ch R = 1 ,34457   ,301.9,393.3,290.46
XS GIS Cut Line= 2
     2094866.211      150194.786     2088145.676      150169.281
#Sta/Elev= 30
       0   62.21  640.01   60.74  667.53   58.83  681.19   60.59  863.74    60.1
 1092.57    57.5 1356.76   52.88 1368.73   51.29 1379.59   52.56 1657.95   50.28
 2191.71   51.79 2264.99   50.82 2496.01   41.55 2790.78   42.41 3300.67   40.71
 3444.03   42.23 3575.35   40.69 3589.81   38.18 3608.95   41.01 4013.15   40.55
  4130.9   42.15 4225.52   40.85 4426.85   41.79  4456.2   40.37    4542   43.79
 4704.31    40.3 5089.83    41.9 6015.61   41.53 6509.44   49.74 6720.58   49.39
#Mann= 3 , 0 , 0
       0     .12       0 3575.35     .06       0 3608.95     .12       0
Bank Sta=3575.35,3608.95
Exp/Cntr=.3,.1

Type RM Length L Ch R = 1 ,34064   ,273.48,282.5,262.54
XS GIS Cut Line= 2
     2093408.616      149887.388     2088220.679      149887.388
#Sta/Elev= 30
       0   54.47  243.52   52.97  656.13   52.51  797.87   50.08  960.22   45.12
  995.26   44.01  1011.8    41.5 1169.89   42.58  1474.9   40.86 1867.66   41.49
 1878.74   38.31  1893.6   41.41    2826   40.82 2973.91   42.36 2980.79   40.75
 3027.78   40.56 3192.24   41.63 3225.19   40.33 3390.23   40.51 3475.66   41.62
 3583.96   40.29 3667.49   41.29 3703.85   43.05  3770.4   41.24 3859.54   41.85
 3943.28    40.9 4640.07   41.49 4759.85    43.2 4931.27   47.49 5187.93   48.12
#Mann= 3 , 0 , 0
       0     .12       0 1867.66     .06       0  1893.6     .12       0
Bank Sta=1867.66,1893.6
Exp/Cntr=.3,.1

Type RM Length L Ch R = 1 ,33782   ,406.25,416.57,393.3
XS GIS Cut Line= 3
      2093609.34      149624.904     2088220.679      149624.904
     2087479.545         150505.
#Sta/Elev= 30
       0   50.74   70.76   53.29  248.32   53.58  582.74   50.93  678.69   45.91
  815.88   45.72  828.41   44.34   940.6   44.52  996.38   46.52 1026.78   44.49
 1140.62   42.74 1219.28   42.75 1250.09   44.53 1263.11   42.35 1286.08   42.06
 1968.31   41.21 1974.86   38.43 1987.93   41.49 2722.66   40.84 2822.64   42.49
 3026.21   40.85 3089.06   42.28 3163.74   40.07 3560.05   40.56    3591   43.74
 4812.32   42.63 5356.81   46.16 5707.55   46.09 5988.34    51.9 6539.25    52.6
#Mann= 3 , 0 , 0
       0     .12       0 1968.31     .06       0 1987.93     .12       0
Bank Sta=1968.31,1987.93
Exp/Cntr=.3,.1

Type RM Length L Ch R = 1 ,33365   ,466.6,517.6,431.51
XS GIS Cut Line= 4
     2095018.421      149239.149     2088359.419      149239.149
     2086864.227      151104.286     2085060.747      153478.097
#Sta/Elev= 30
       0   64.93  738.59   61.08 1071.89   54.47 1384.24   53.57  1525.7   47.63
 2317.23   53.68 2572.44    48.6 2636.88   44.69 2826.83    45.2 2905.32   41.41
 3512.95    40.9 3526.87   37.52 3537.01   40.92 4961.48   39.92 5043.26   40.29
 5064.16    43.7 6264.56    42.4 6851.64   47.77  7268.8   45.64 7628.73   52.13
 8618.96   52.57 9253.02   47.2910236.72   53.7610724.04   50.1910859.29   51.69
10932.24   49.0611754.88    49.411787.54   46.64   11806   50.1512030.66   51.26
#Mann= 3 , 0 , 0
       0     .12       0 3512.95     .06       0 3537.01     .12       0
#XS Ineff= 2 , 0
       0                    6250       0      46
Bank Sta=3512.95,3537.01
Exp/Cntr=.3,.1