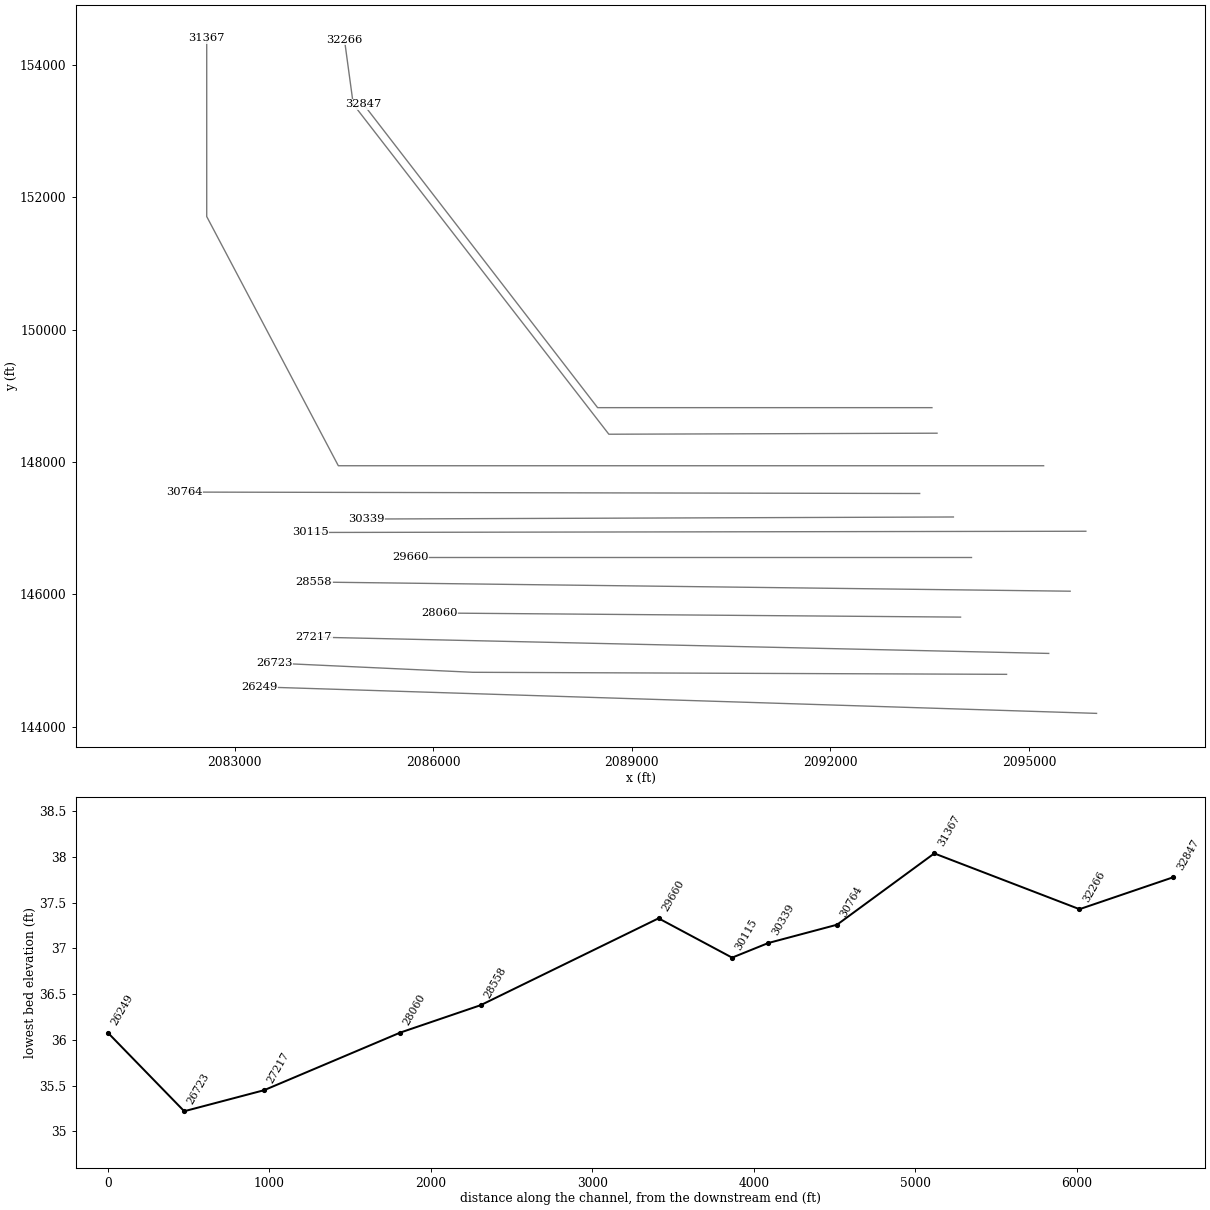
HEC-RAS study monieswamp.prj: MonieSwamp

--- monieswamp.g01 (geometry) --- (continued)

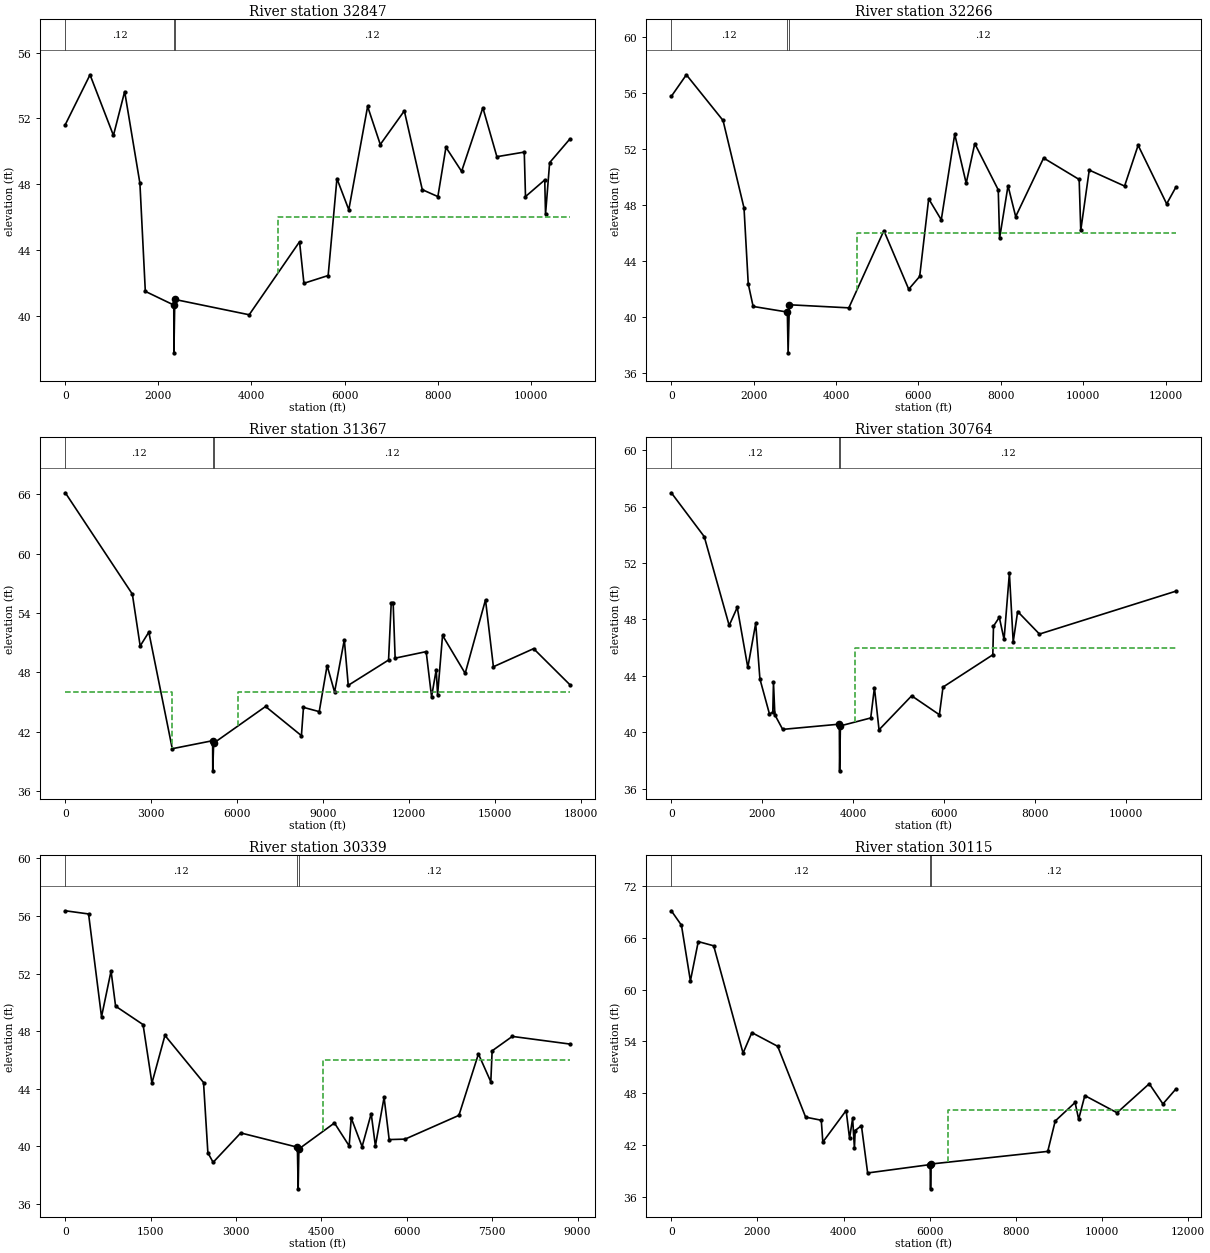
Type RM Length L Ch R = 1 ,32847   ,455.1,581.7,528.03
XS GIS Cut Line= 3
     2093532.139      148822.008     2088483.163      148822.008
     2084947.337      153407.775
#Sta/Elev= 30
       0   51.63   530.8   54.65 1033.69   50.97 1274.96   53.63 1602.46   48.07
 1718.73   41.51 2330.51   40.68 2333.06   37.78 2352.19   41.02 3950.33   40.09
 5032.58   44.52 5126.65      42  5647.2   42.47 5836.01   48.35 6090.69   46.46
 6495.27   52.73  6767.3   50.42 7283.72   52.46 7669.76   47.68 8004.59   47.26
  8178.2   50.25 8514.44   48.79 8971.34   52.65 9272.73   49.68 9860.98   49.96
 9887.41   47.2610301.12   48.2710317.62   46.1810406.35   49.32 10839.6   50.75
#Mann= 3 , 0 , 0
       0     .12       0 2330.51     .06       0 2352.19     .12       0
#XS Ineff= 2 , 0
       0                    4560       0      46
Bank Sta=2330.51,2352.19
Exp/Cntr=.3,.1

Type RM Length L Ch R = 1 ,32266   ,532.14,899.09,678.82
XS GIS Cut Line= 4
      2093609.34      148436.001     2088653.007      148420.561
     2084792.934      153407.775        2084660.         154384.
#Sta/Elev= 30
       0   55.73  365.18   57.27 1255.82   54.01 1764.79   47.77 1867.76   42.35
  1986.3   40.74 2817.07   40.34 2835.22   37.43 2866.06   40.86 4309.78   40.64
 5160.75   46.15  5763.6   41.97 6029.71   42.88 6248.47   48.42 6554.01   46.92
 6880.85   53.03 7159.15   49.53 7367.19   52.36 7937.18   49.06 7970.14   45.61
 8174.78   49.35 8360.59   47.15 9038.79   51.33 9901.92    49.8 9940.38   46.16
10146.73   50.4711004.43   49.3311333.37   52.2412026.22   48.0612248.12   49.24
#Mann= 3 , 0 , 0
       0     .12       0 2817.07     .06       0 2866.06     .12       0
#XS Ineff= 2 , 0
       0                    4500       0      46
Bank Sta=2817.07,2866.06
Exp/Cntr=.3,.1

Type RM Length L Ch R = 1 ,31367   ,418.45,602.26,445.08
XS GIS Cut Line= 4
     2095218.807      147944.344     2084567.488      147944.344
        2082580.         151710.        2082580.         154403.
#Sta/Elev= 30
       0   66.17  2338.4   55.92 2611.26   50.67 2913.46   52.07 3732.07   40.28
 5139.87   41.09 5143.79   38.04 5175.07   40.84 6986.48   44.55 8237.43    41.6
 8309.44   44.46 8859.02   44.03 9133.74   48.69 9394.55   46.01 9734.48    51.3
 9871.65   46.6911278.05   49.2511371.04   55.0411437.79   55.0711507.74   49.44
12590.31    50.1 12778.9   45.53 12941.6   48.2812989.01   45.7313161.66   51.74
13951.44    47.914660.76   55.3414936.21   48.5716338.84    50.417602.28   46.76
#Mann= 3 , 0 , 0
       0     .12       0 5139.87     .06       0 5175.07     .12       0
#XS Ineff= 2 , 0
       0    3730      46    6030       0      46
Bank Sta=5139.87,5175.07
Exp/Cntr=.3,.1

Type RM Length L Ch R = 1 ,30764   ,374.48,425.37,381.22
XS GIS Cut Line= 3
     2093346.855      147525.024     2085240.702      147540.464
 2082246.8773526  147546.1664155
#Sta/Elev= 30
       0   56.98  724.51   53.87  1273.2   47.57 1450.24   48.85 1683.12   44.59
 1856.65   47.72  1949.2   43.78 2157.77   41.31 2232.82    41.4 2247.69   43.55
 2278.44   41.23 2450.06    40.2 3696.41   40.57 3702.74   37.26 3720.73   40.45
 4387.45   41.01  4468.9   43.16 4570.26   40.17 5288.06   42.58 5898.17   41.24
 5978.05    43.2 7073.81   45.49 7088.48   47.52 7216.52   48.15 7321.33   46.58
 7438.58   51.28 7522.29    46.4 7620.14   48.56 8099.96   46.96   11100      50
#Mann= 3 , 0 , 0
       0     .12       0 3696.41     .06       0 3720.73     .12       0
#XS Ineff= 2 , 0
       0                    4050       0      46
Bank Sta=3696.41,3720.73
Exp/Cntr=.3,.1

Type RM Length L Ch R = 1 ,30339   ,218.15,224.15,210.97
XS GIS Cut Line= 2
     2093856.385      147169.897     2084993.658      147139.017
#Sta/Elev= 30
       0   56.36  408.44   56.14  635.75      49  803.44   52.18  882.99   49.74
 1365.65   48.46  1521.6    44.4 1749.88   47.71 2427.82   44.44  2504.4   39.56
 2596.55    38.9 3081.69   40.94 4076.88   39.95 4090.27   37.06 4103.47   39.83
 4728.01   41.63 4986.47   40.04 5023.09   41.97 5213.68   39.99 5373.63   42.28
 5447.26   40.04 5600.02   43.41 5689.35   40.48 5968.67   40.51 6914.57   42.16
 7257.33   46.42 7474.82   44.49 7498.19   46.64 7852.53   47.64 8862.79   47.11
#Mann= 3 , 0 , 0
       0     .12       0 4076.88     .06       0 4103.47     .12       0
#XS Ineff= 2 , 0
       0                    4530       0      46
Bank Sta=4076.88,4103.47
Exp/Cntr=.3,.1

Type RM Length L Ch R = 1 ,30115   ,391.26,455.29,389.51
XS GIS Cut Line= 2
     2095856.766      146954.342     2084145.069      146936.014
#Sta/Elev= 30
       0   69.13  235.39   67.45  443.06      61  625.44   65.56  983.39   65.07
 1665.52   52.63 1869.55   55.01 2469.66   53.42 3117.99   45.21 3481.26   44.85
 3517.37   42.32 4058.54   45.98 4137.79   42.75 4209.36   45.08 4250.87   41.58
 4268.06   43.66 4413.53   44.22 4557.76   38.74 6008.11   39.71  6018.1    36.9
 6031.53   39.78 8738.84   41.24  8912.1   44.76 9373.59   46.91 9456.43   44.97
 9599.58   47.71 10347.8   45.7211095.31   49.0811412.84   46.7411711.71   48.46
#Mann= 3 , 0 , 0
       0     .12       0 6008.11     .06       0 6031.53     .12       0
#XS Ineff= 2 , 0
       0                    6430       0      46
Bank Sta=6008.11,6031.53
Exp/Cntr=.3,.1

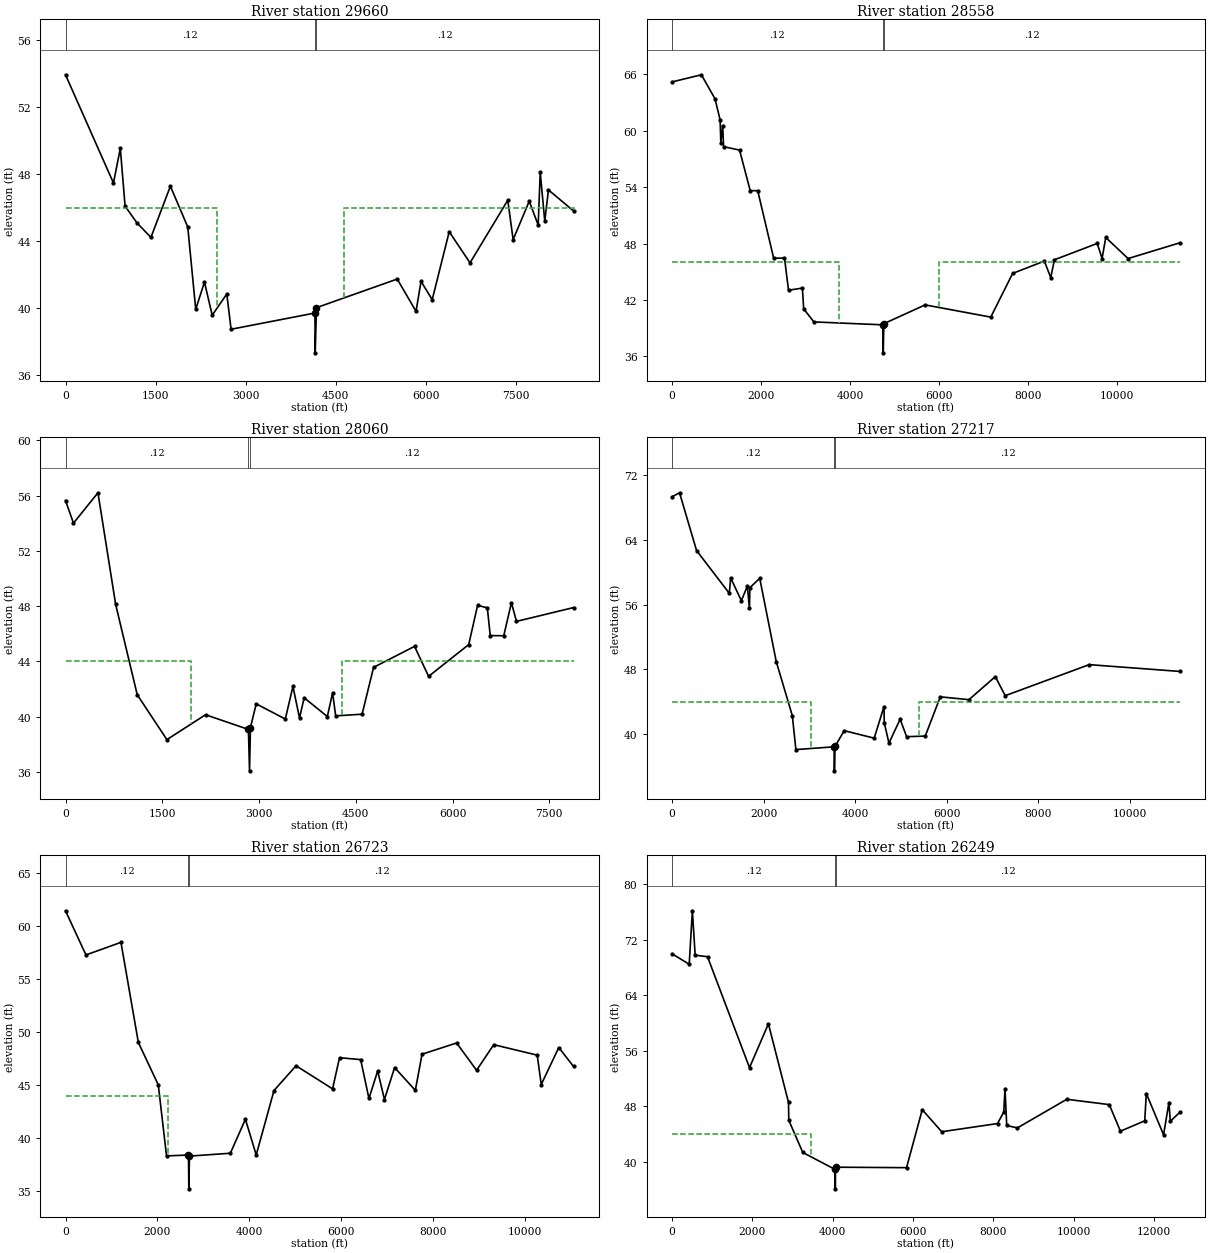
Type RM Length L Ch R = 1 ,29660   ,561.62,1101.53,521.8
XS GIS Cut Line= 2
      2094118.87      146567.726      2085657.59      146567.726
#Sta/Elev= 30
       0   53.95  798.71   47.48  912.89   49.55  992.24    46.1 1189.34    45.1
 1422.68   44.23 1746.71   47.29 2036.21   44.85  2168.7   39.93 2314.18   41.56
 2443.13   39.58  2686.3   40.85 2757.63   38.74 4154.49   39.71 4158.51   37.33
 4179.88   40.03 5524.62   41.74 5837.93   39.81 5920.89    41.6 6107.59   40.51
 6390.46   44.57 6737.36   42.71  7365.9   46.45 7455.08    44.1 7723.15   46.39
  7872.3   44.97 7906.46   48.12 7982.06   45.19  8043.1   47.07 8461.29   45.81
#Mann= 3 , 0 , 0
       0     .12       0 4154.49     .06       0 4179.88     .12       0
#XS Ineff= 2 , 0
       0    2530      46    4630       0      46
Bank Sta=4154.49,4179.88
Exp/Cntr=.3,.1

Type RM Length L Ch R = 1 ,28558   ,498,498.09,563.99
XS GIS Cut Line= 2
     2095619.581      146048.378     2084197.543      146187.107
#Sta/Elev= 30
       0    65.2  661.31   65.96  966.93   63.41 1082.74   61.16 1098.03   58.72
 1140.44   60.54 1160.55   58.31 1519.66   57.95 1759.49   53.63 1927.68   53.63
 2286.31   46.45 2530.05   46.46 2620.45   43.04 2932.51   43.27 2961.25   41.06
 3189.91   39.67  4740.5   39.36 4750.48   36.38 4763.34   39.48 5691.91   41.48
 7167.92   40.18 7659.92   44.83 8372.79   46.14 8515.87   44.39 8600.03   46.28
 9562.47   48.02 9670.13   46.41 9753.35   48.65 10255.7   46.4111422.89   48.09
#Mann= 3 , 0 , 0
       0     .12       0  4740.5     .06       0 4763.34     .12       0
#XS Ineff= 2 , 0
       0    3760      46    6000       0      46
Bank Sta=4740.5,4763.34
Exp/Cntr=.3,.1

Type RM Length L Ch R = 1 ,28060   ,559.08,842.91,1035.56
XS GIS Cut Line= 2
     2093964.467      145656.749     2086089.918       145718.51
#Sta/Elev= 30
       0   55.65  123.33   54.01  502.86   56.21  777.31   48.13 1111.59   41.59
 1571.46   38.34 2170.14   40.14 2834.92   39.08 2852.51   36.08 2866.42   39.21
 2956.03   40.93 3407.05   39.83 3525.27   42.19 3627.19   39.91 3699.41   41.37
 4058.28   40.01 4140.16   41.73  4187.5   40.06 4597.21   40.18  4775.1   43.57
 5409.96   45.09 5628.27   42.92 6249.84   45.22 6387.39   48.06 6538.32   47.88
 6583.72   45.87 6792.74   45.86 6911.86   48.25 6990.45    46.9 7874.79    47.9
#Mann= 3 , 0 , 0
       0     .12       0 2834.92     .06       0 2866.42     .12       0
#XS Ineff= 2 , 0
       0    1950      44    4290       0      44
Bank Sta=2834.92,2866.42
Exp/Cntr=.3,.1

Type RM Length L Ch R = 1 ,27217   ,404.09,494.37,453.11
XS GIS Cut Line= 2
     2095295.879      145108.102     2084197.543      145354.732
#Sta/Elev= 30
       0   69.33  165.42   69.83  536.93   62.69 1252.54    57.4 1282.52    59.3
 1516.19   56.49 1647.72    58.3 1692.33   55.56 1702.72   58.09 1917.23   59.26
  2279.4   48.94 2629.68   42.27 2707.55   38.08 3541.25   38.42 3549.44   35.45
 3563.45   38.47 3762.74   40.42 4418.97   39.49 4633.25    43.4 4638.79   41.41
 4740.71   38.88 4985.88   41.83 5127.52   39.67 5534.32   39.75 5863.34    44.6
 6488.73   44.25 7065.45    47.1  7281.3   44.74 9115.77   48.5811101.09   47.74
#Mann= 3 , 0 , 0
       0     .12       0 3541.25     .06       0 3563.45     .12       0
#XS Ineff= 2 , 0
       0    3030      44    5400       0      44
Bank Sta=3541.25,3563.45
Exp/Cntr=.3,.1

Type RM Length L Ch R = 1 ,26723   ,482.21,473.45,464.47
XS GIS Cut Line= 3
      2094659.28      144792.093     2086599.448      144822.973
     2083604.032      144961.936
#Sta/Elev= 30
       0   61.47  444.93    57.3 1206.86   58.49 1585.72   49.04 2019.74   45.03
 2198.84   38.33 2676.17   38.41 2684.75   35.22 2698.28   38.31  3588.2   38.58
 3916.02   41.79 4151.15   38.42 4538.02    44.5 5017.86   46.84 5813.08   44.66
  5964.6    47.6 6424.38   47.42  6604.8   43.75 6795.21   46.35  6942.5   43.65
 7163.02   46.67 7614.79   44.52 7760.85   47.93 8513.46   48.99 8948.07   46.41
  9320.6   48.8310267.77   47.8410355.53   45.0710737.24   48.5611058.54   46.77
#Mann= 3 , 0 , 0
       0     .12       0 2676.17     .06       0 2698.28     .12       0
#XS Ineff= 2 , 0
       0    2230      44               0
Bank Sta=2676.17,2698.28
Exp/Cntr=.3,.1

Type RM Length L Ch R = 1 ,26249   ,246.75,297.89,257.28
XS GIS Cut Line= 2
     2096018.174      144202.162     2083373.232      144602.681
#Sta/Elev= 30
       0   69.97  428.87   68.45  508.08   76.16  577.51   69.76  884.72   69.54
  1930.7   53.55 2401.51   59.86 2902.06   48.54 2909.36   45.96 3257.39   41.32
 4061.06   38.88 4067.03   36.08 4073.71    39.2 5840.85   39.13 6232.58   47.49
 6717.25   44.31 8106.69   45.49 8262.33   47.15 8293.05   50.53 8335.83   45.21
 8600.85   44.86 9831.97   48.9910889.89   48.2211167.51   44.3911772.87   45.88
11811.97   49.82 12241.6   43.8712375.35   48.5112409.86   45.8212651.28   47.14
#Mann= 3 , 0 , 0
       0     .12       0 4061.06     .06       0 4073.71     .12       0
#XS Ineff= 2 , 0
       0    3460      44               0
Bank Sta=4061.06,4073.71
Exp/Cntr=.3,.1