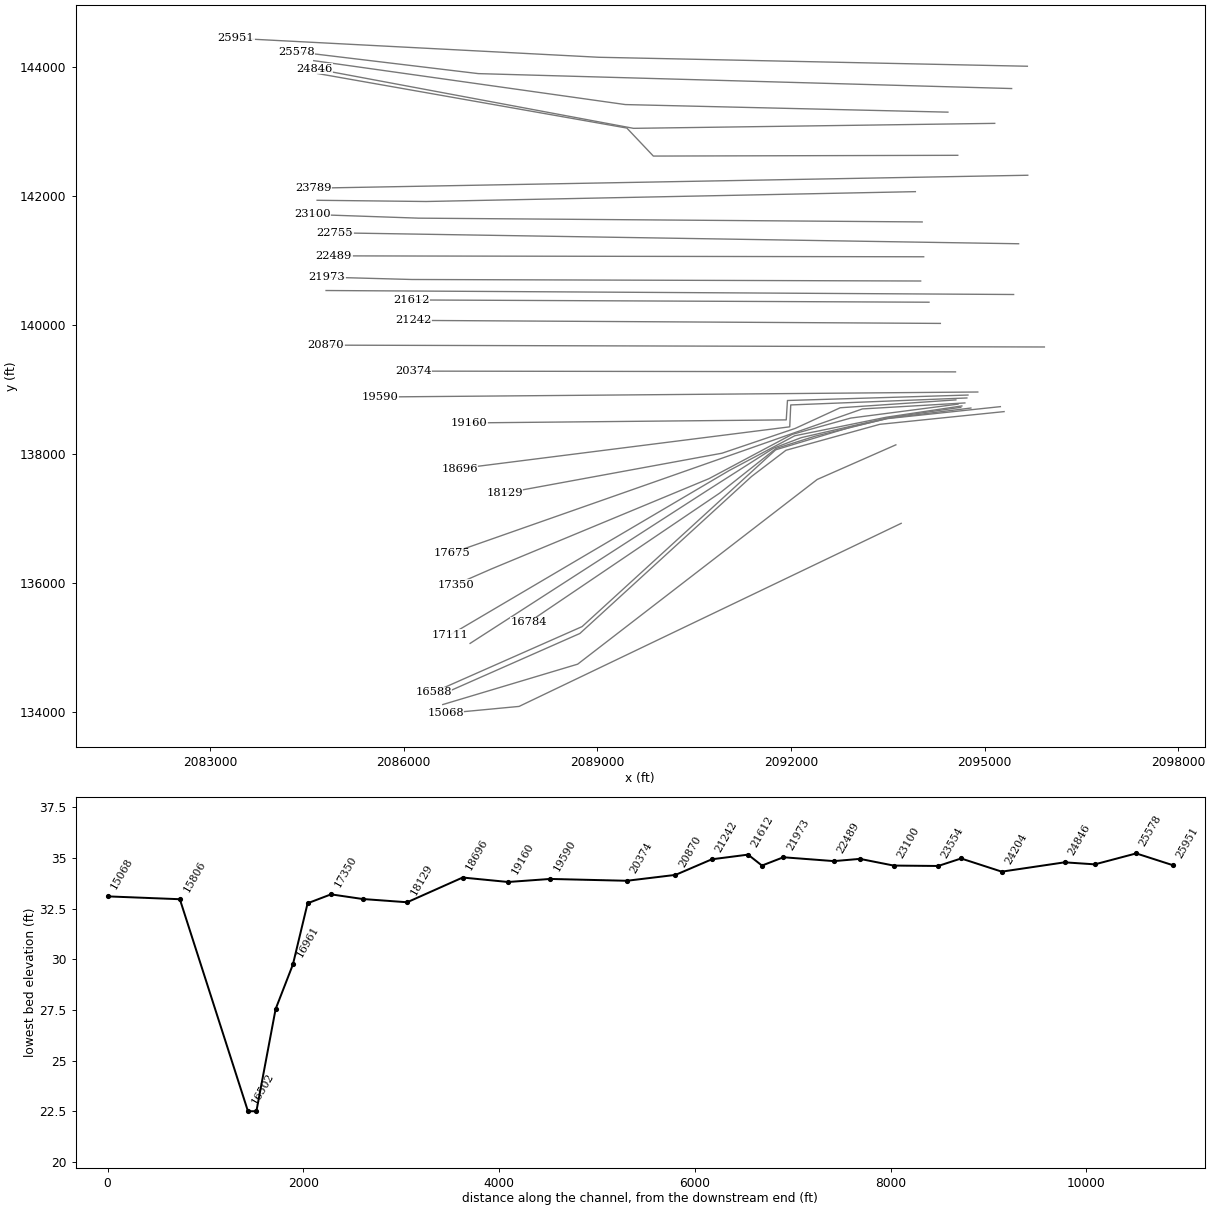
HEC-RAS study monieswamp.prj: MonieSwamp

--- monieswamp.g01 (geometry) --- (continued)

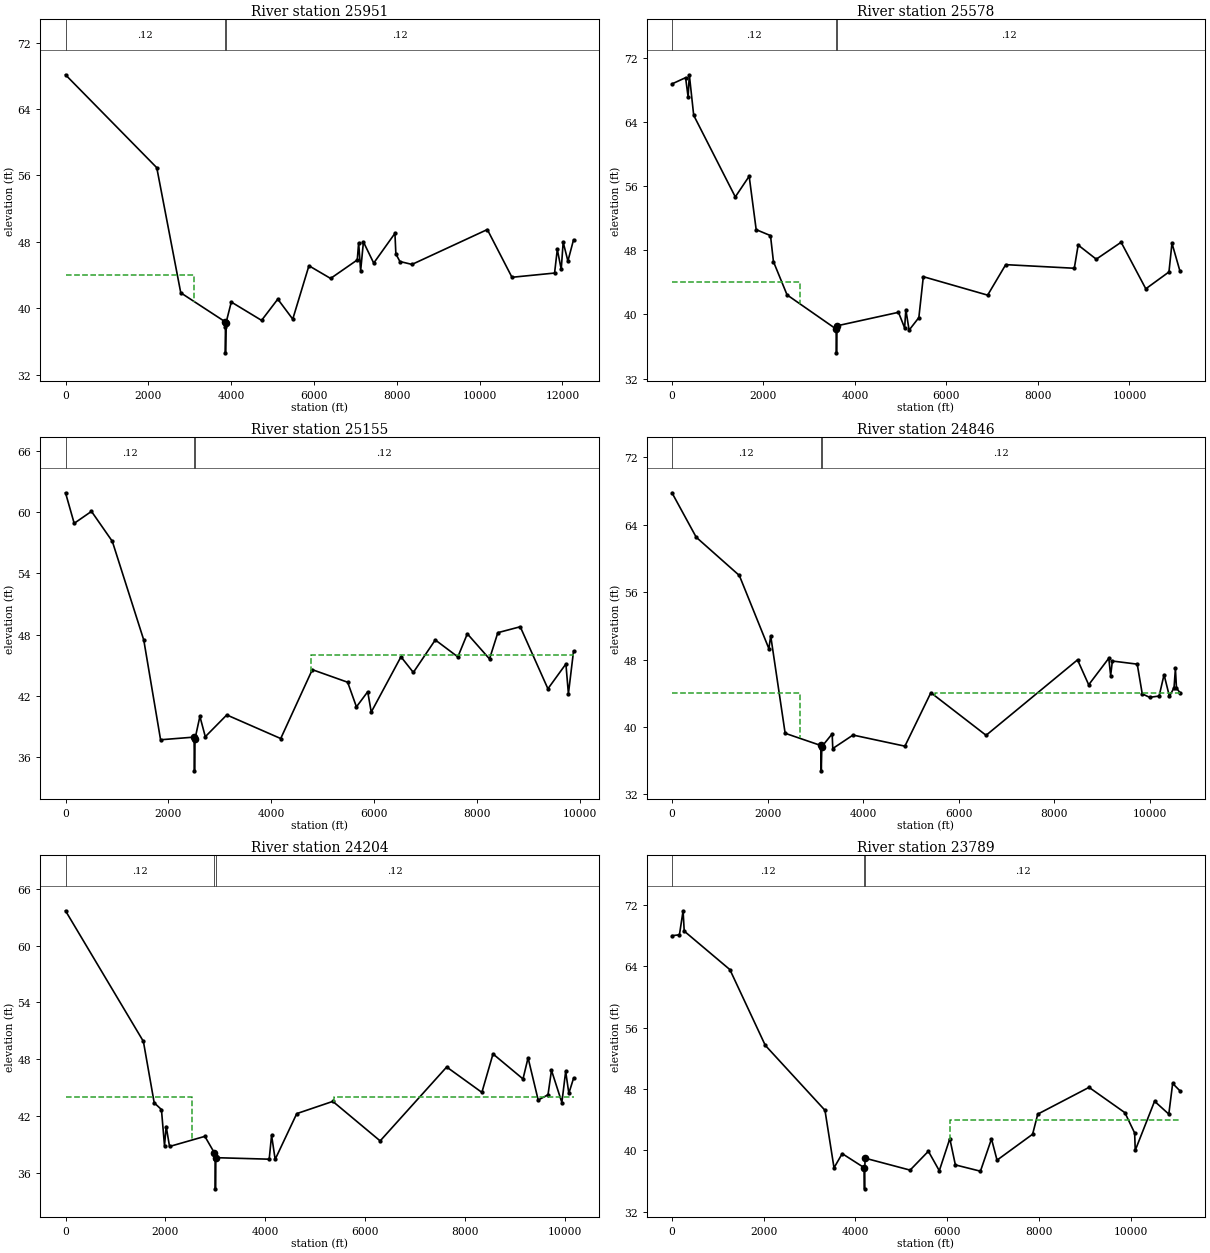
Type RM Length L Ch R = 1 ,25951   ,330.37,373.29,320.87
XS GIS Cut Line= 3
     2095662.899      144004.638     2089023.574        144143.6
     2083403.308      144436.966
#Sta/Elev= 30
       0   68.13  2203.8   56.94 2783.35   41.87 3852.38   38.39 3860.58   37.78
 3863.01   34.64 3876.91   38.26 4003.54   40.76 4735.15   38.55 5126.68   41.11
 5487.69    38.7 5878.56   45.13 6401.87    43.6 7046.26   45.83  7078.9    47.9
 7127.28   44.53 7194.37      48  7442.9   45.45 7955.35   49.03 7977.89   46.55
 8075.67   45.64 8367.17   45.2910186.62   49.4910781.83   43.7411810.52   44.25
11876.57    47.111971.11   44.6912018.27   47.9712132.54   45.6912268.71   48.26
#Mann= 3 , 0 , 0
       0     .12       0 3852.38     .06       0 3876.91     .12       0
#XS Ineff= 2 , 0
       0    3110      44               0
Bank Sta=3852.38,3876.91
Exp/Cntr=.3,.1

Type RM Length L Ch R = 1 ,25578   ,416.09,422.67,408.4
XS GIS Cut Line= 3
     2095419.194      143659.153       2087157.1      143890.368
     2084336.273      144229.484
#Sta/Elev= 30
       0   68.73   297.6   69.51  353.22   67.09  379.29   69.87  474.94   64.82
 1384.46   54.65 1687.61   57.23 1840.94   50.57 2153.79   49.83 2218.09   46.59
 2516.21   42.44 3587.39   38.19 3596.56   35.22  3609.6   38.59 4951.54   40.27
 5086.15   38.33 5112.58    40.6    5184   38.05 5397.02   39.61 5494.98   44.71
 6900.98   42.41 7296.15   46.21 8795.23   45.76 8879.93   48.65 9275.54   46.89
 9819.11      4910358.49    43.210865.05    45.310930.66   48.8811106.48   45.38
#Mann= 3 , 0 , 0
       0     .12       0 3587.39     .06       0  3609.6     .12       0
#XS Ineff= 2 , 0
       0    2790      44    5500       0      44
Bank Sta=3587.39,3609.6
Exp/Cntr=.3,.1

Type RM Length L Ch R = 1 ,25155   ,284.15,309.08,306.66
XS GIS Cut Line= 3
     2094432.256      143293.448     2089434.745      143410.761
     2084607.337      144091.173
#Sta/Elev= 30
       0   61.89  168.83    58.9  504.76   60.07  909.66   57.14 1521.51   47.47
 1847.81   37.72 2498.12   37.98 2506.98   34.68 2517.87   37.83 2611.93   40.01
 2717.06   38.02  3134.4   40.15 4182.69   37.84 4796.68   44.58 5483.77   43.35
  5654.5   40.94 5873.56   42.42  5942.4   40.43 6519.83   45.84 6760.37   44.31
 7186.71   47.49 7625.53   45.83 7809.55   48.09 8240.65   45.63 8402.46    48.2
 8837.86   48.78 9375.89   42.71 9725.51   45.14 9774.15   42.22    9874    46.4
#Mann= 3 , 0 , 0
       0     .12       0 2498.12     .06       0 2517.87     .12       0
#XS Ineff= 2 , 0
       0                    4780       0      46
Bank Sta=2498.12,2517.87
Exp/Cntr=.3,.1

Type RM Length L Ch R = 1 ,24846   ,489.67,642.39,450.17
XS GIS Cut Line= 3
      2095157.15       143119.65     2089561.739      143042.579
     2084613.731       143967.44
#Sta/Elev= 30
       0    67.8  507.52   62.52 1409.26   57.98 2027.87   49.29 2065.81   50.81
 2367.96   39.24 3114.49   37.79 3123.81   34.78 3135.75   37.66 3351.63   39.17
 3364.43   37.43 3787.82   39.03 4873.56   37.71 5417.06   44.06 6572.16      39
 8485.48   47.96  8719.1      45 9139.44   48.15 9178.56    46.1 9214.07   47.82
 9734.46   47.45 9839.53   43.92 9993.55   43.5110192.59   43.66 10295.7    46.2
10408.12   43.6310504.91   44.6510533.25   46.94 10555.6    44.610629.66   44.06
#Mann= 3 , 0 , 0
       0     .12       0 3114.49     .06       0 3135.75     .12       0
#XS Ineff= 2 , 0
       0    2670      44    5500       0      44
Bank Sta=3114.49,3135.75
Exp/Cntr=.3,.1

Type RM Length L Ch R = 1 ,24204   ,378.17,415.27,384.98
XS GIS Cut Line= 4
     2094584.762      142624.767     2089868.801      142613.036
     2089458.207      143047.092     2084665.993      143891.742
#Sta/Elev= 30
       0   63.67 1560.59   49.88  1777.2    43.4 1922.27   42.69 1983.64   38.87
 2017.54    40.9 2084.41   38.79 2792.27   39.86 2982.61   38.12 2997.35   37.52
 3003.74   34.32 3013.14   37.61 4081.37   37.45 4128.96   39.97 4200.78   37.43
 4633.68   42.26 5355.94   43.55 6304.64   39.38  7637.6   47.18 8342.81    44.5
 8565.61   48.56 9166.77   45.92 9268.31   48.15 9471.16   43.69 9667.81   44.25
 9737.47   46.83  9945.5   43.4310021.71   46.7210085.27    44.410179.54   45.99
#Mann= 3 , 0 , 0
       0     .12       0 2982.61     .06       0 3013.14     .12       0
#XS Ineff= 2 , 0
       0    2530      44    5380       0      44
Bank Sta=2982.61,3013.14
Exp/Cntr=.3,.1

Type RM Length L Ch R = 1 ,23789   ,230.07,234.18,229.83
XS GIS Cut Line= 2
     2095669.057      142315.823      2084597.58      142115.563
#Sta/Elev= 30
       0   67.97  162.74   68.09   242.3   71.22  266.85   68.57 1262.25   63.55
 2033.46   53.68  3334.7   45.21    3532   37.71 3710.43   39.56  4185.7   37.74
 4196.58   34.97 4207.85   38.97 5190.33   37.41 5588.52   39.87 5826.74   37.33
 6056.07   41.51 6176.98   38.09  6723.3   37.27  6964.4   41.48 7085.01   38.71
 7860.29   42.09 7972.64   44.71 9090.56    48.2 9871.88    44.910084.37   42.25
10097.53   39.9910518.71   46.3910829.03   44.71 10912.9   48.7111073.29   47.74
#Mann= 3 , 0 , 0
       0     .12       0  4185.7     .06       0 4207.85     .12       0
#XS Ineff= 2 , 0
       0                    6060       0      44
Bank Sta=4185.7,4207.85
Exp/Cntr=.3,.1

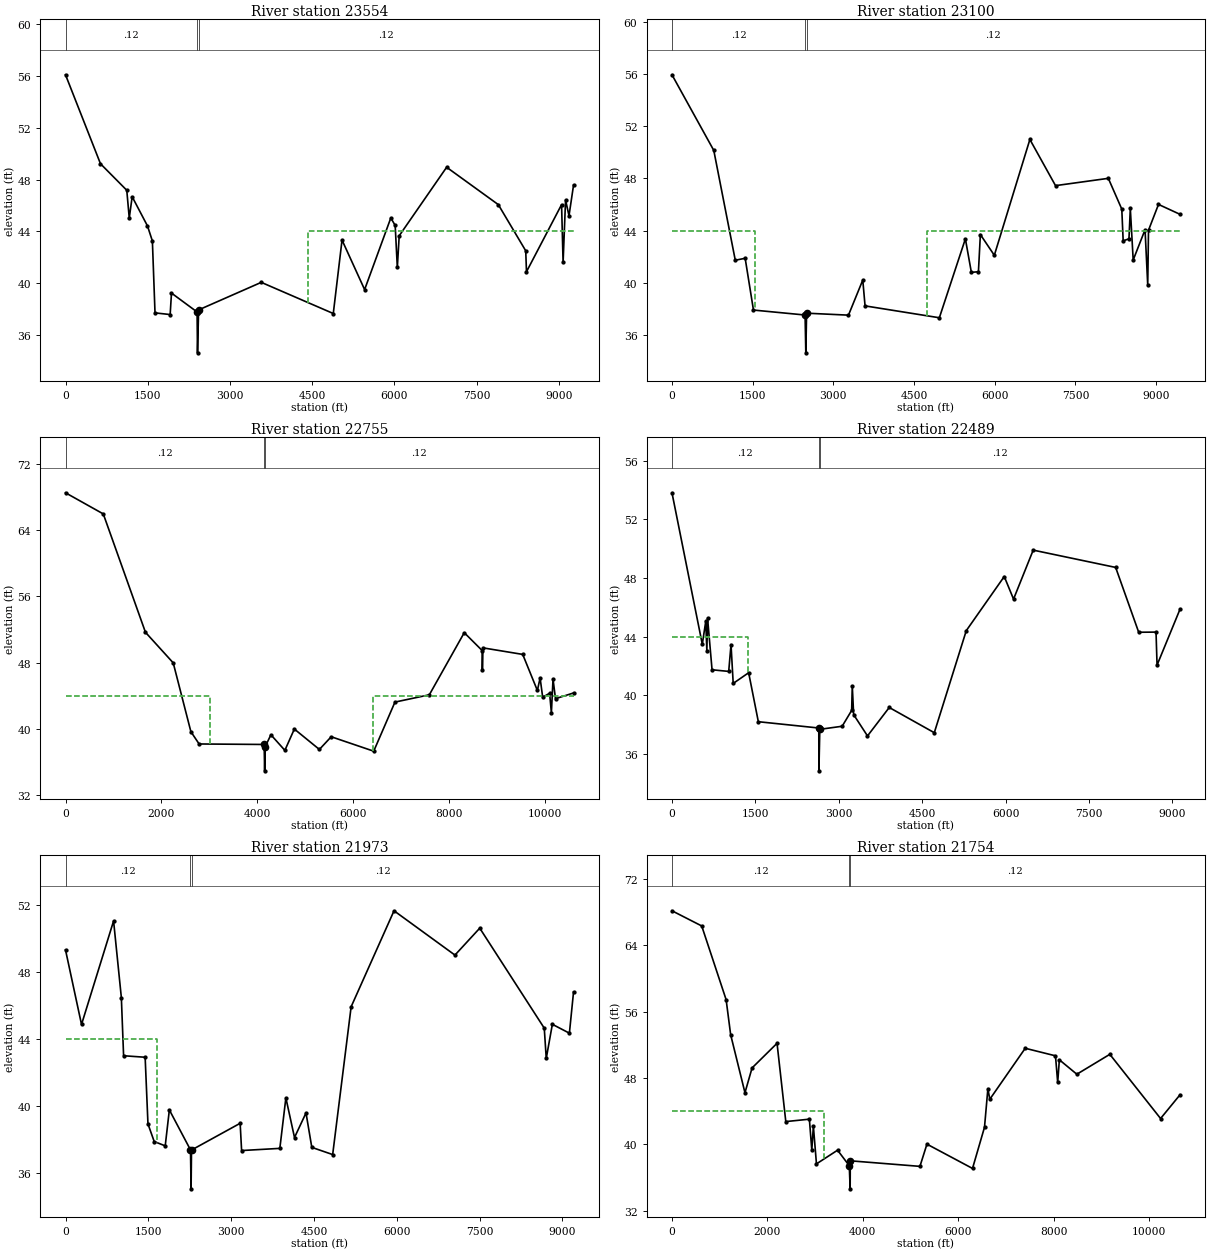
Type RM Length L Ch R = 1 ,23554   ,416.13,454.49,390.33
XS GIS Cut Line= 3
     2093927.812      142061.667     2086349.427      141909.161
        2084660.         141928.
#Sta/Elev= 30
       0    56.1  638.17   49.22 1117.94   47.17 1163.12   45.02 1216.38   46.67
 1495.82   44.41 1585.12   43.25 1633.05   37.69 1909.57   37.56 1933.45   39.22
 2400.79   37.76 2408.32    34.6  2428.6   37.92 3571.78   40.05 4885.68   37.64
 5045.42   43.32  5457.4   39.49 5935.27   45.03 6015.09   44.45 6054.29    41.2
 6088.39   43.65 6953.88   48.95 7896.78   46.06 8397.03   42.49 8410.72   40.87
 9051.03   46.06 9078.75   41.59 9123.81   46.42 9186.43    45.2 9269.46   47.57
#Mann= 3 , 0 , 0
       0     .12       0 2400.79     .06       0  2428.6     .12       0
#XS Ineff= 2 , 0
       0                    4430       0      44
Bank Sta=2400.79,2428.6
Exp/Cntr=.3,.1

Type RM Length L Ch R = 1 ,23100   ,300.16,345.22,289.14
XS GIS Cut Line= 3
     2094033.393      141592.418     2086232.115      141651.074
        2084590.         141708.
#Sta/Elev= 30
       0   55.94  777.33   50.14 1176.94   41.72  1360.6   41.87 1514.95    37.9
 2474.48   37.52 2488.02   34.62 2502.82   37.66 3281.16   37.51 3547.04    40.2
 3589.61   38.22 4970.61   37.31 5454.49   43.36 5565.81   40.79 5696.99   40.84
 5733.29   43.69 5992.61    42.1  6653.6   50.98 7130.32   47.44 8111.77      48
 8362.21   45.64 8387.87   43.21  8495.6   43.36 8520.68   45.69 8574.12   41.74
 8794.71   44.06 8844.44   39.82 8858.87   44.02 9044.62      46  9444.6   45.24
#Mann= 3 , 0 , 0
       0     .12       0 2474.48     .06       0 2502.82     .12       0
#XS Ineff= 2 , 0
       0    1550      44    4740       0      44
Bank Sta=2474.48,2502.82
Exp/Cntr=.3,.1

Type RM Length L Ch R = 1 ,22755   ,260.47,265.4,272.13
XS GIS Cut Line= 2
     2095527.095      141254.513     2084937.433      141424.071
#Sta/Elev= 30
       0   68.48  787.56   65.93 1666.35   51.66 2245.41   47.97 2613.95   39.67
 2785.24   38.19 4141.09   38.13 4151.49   34.95 4162.27   37.85  4281.7    39.3
 4573.03   37.42  4770.4   39.99  5292.5   37.53 5539.22   39.06 6425.01   37.32
 6868.01   43.24 7584.62   44.12  8312.5   51.61 8685.46   49.46 8690.25   47.07
 8702.37   49.78 9531.24   48.99 9836.99   44.64 9893.77   46.15 9947.69   43.82
10091.86   44.3110129.06   41.9410163.11   46.0110214.86   43.6510591.02   44.34
#Mann= 3 , 0 , 0
       0     .12       0 4141.09     .06       0 4162.27     .12       0
#XS Ineff= 2 , 0
       0    3010      44    6415       0      44
Bank Sta=4141.09,4162.27
Exp/Cntr=.3,.1

Type RM Length L Ch R = 1 ,22489   ,378.52,516.71,375.11
XS GIS Cut Line= 3
     2094056.856       141052.78     2086208.652      141064.511
        2084920.         141067.
#Sta/Elev= 30
       0    53.8  545.47   43.47  607.26   45.03   627.4   43.03  639.94   45.26
   720.8   41.73 1020.47   41.62 1061.93   43.45 1101.17    40.8 1379.07   41.53
 1553.21   38.19 2640.56   37.76 2642.53   34.84 2658.83   37.67 3060.74   37.88
 3231.62   38.96  3242.7   40.64 3267.51   38.67 3516.41   37.22 3907.68   39.16
 4717.72   37.44 5293.09    44.4 5975.78   48.09 6142.91   46.55 6496.51   49.89
 7979.28   48.71 8393.77   44.29 8705.54    44.3 8723.95   42.05 9136.87   45.86
#Mann= 3 , 0 , 0
       0     .12       0 2640.56     .06       0 2658.83     .12       0
#XS Ineff= 2 , 0
       0    1370      44               0
Bank Sta=2640.56,2658.83
Exp/Cntr=.3,.1

Type RM Length L Ch R = 1 ,21973   ,200.23,218.76,193.98
XS GIS Cut Line= 3
     2094009.931       140677.38     2086126.533      140700.843
        2084810.         140737.
#Sta/Elev= 30
       0   49.32  290.03   44.86  870.63   51.05 1011.31   46.47 1051.92   42.99
 1442.21    42.9 1493.36   38.91  1606.1   37.86  1805.8    37.6 1880.69   39.75
 2263.31   37.36 2274.31   35.03 2281.72   37.35 3162.72   38.95 3189.16   37.32
 3881.48   37.45 3990.81   40.47 4147.09    38.1 4355.49   39.57 4460.41   37.51
 4838.28   37.08 5172.69   45.92 5949.36   51.66 7052.68   49.01 7501.83   50.62
 8670.19   44.64 8706.12   42.83 8816.63   44.87 9125.28   44.34 9200.47   46.81
#Mann= 3 , 0 , 0
       0     .12       0 2263.31     .06       0 2281.72     .12       0
#XS Ineff= 2 , 0
       0    1660      44               0
Bank Sta=2263.31,2281.72
Exp/Cntr=.3,.1

Type RM Length L Ch R = 1 ,21754   ,133.79,142,133.1
XS GIS Cut Line= 2
     2095450.023      140468.381     2084798.703      140530.039
#Sta/Elev= 30
       0   68.15   623.6   66.32 1135.45   57.43 1230.52    53.2  1530.3   46.21
  1679.3    49.2 2202.94   52.17 2386.57   42.73 2880.71   43.02 2931.67    39.3
 2964.61   42.17 3029.28   37.63 3471.79   39.28 3717.38   37.41 3735.77   34.62
 3738.68      38 5198.64   37.33 5345.51   40.01 6301.16   37.08 6552.56   42.05
 6623.29    46.7 6663.18   45.42 7406.43   51.57 8040.56   50.66 8086.93   47.45
 8121.81   50.18 8488.58   48.44 9179.96   50.8410243.99    43.110651.51   45.96
#Mann= 3 , 0 , 0
       0     .12       0 3717.38     .06       0 3738.68     .12       0
#XS Ineff= 2 , 0
       0    3180      44               0
Bank Sta=3717.38,3738.68
Exp/Cntr=.3,.1

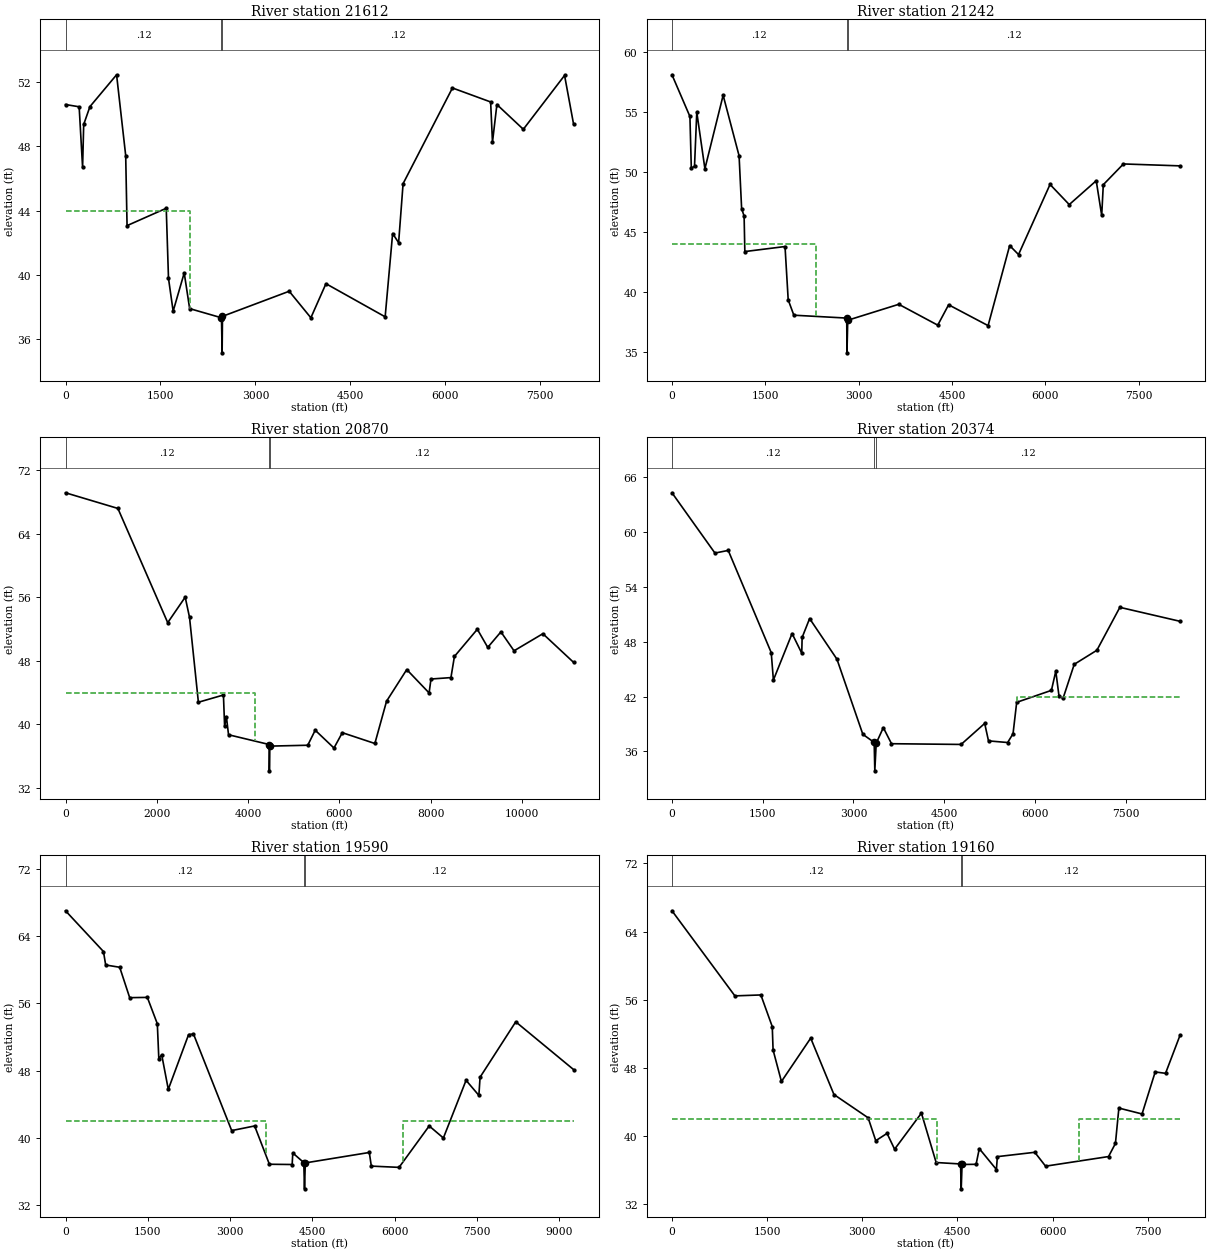
Type RM Length L Ch R = 1 ,21612   ,333.26,369.68,326.47
XS GIS Cut Line= 2
     2094138.974      140348.905     2086114.802      140384.099
#Sta/Elev= 30
       0    50.6  215.53   50.46  269.83   46.69  287.25   49.36  385.83   50.47
  806.73   52.45   950.6   47.43  972.17   43.07 1590.97   44.15 1626.66   39.79
 1700.14   37.75 1875.05   40.13 1960.72   37.91 2463.44   37.34 2473.78   35.16
 2479.49   37.43 3533.13   38.99 3875.33   37.34 4113.67   39.46 5048.68    37.4
 5166.68   42.58 5261.32   42.01 5331.91   45.68  6111.4   51.63 6714.68   50.76
 6743.77   48.26 6813.53    50.6 7231.01   49.06 7882.33   52.41 8024.25   49.39
#Mann= 3 , 0 , 0
       0     .12       0 2463.44     .06       0 2479.49     .12       0
#XS Ineff= 2 , 0
       0    1970      44               0
Bank Sta=2463.44,2479.49
Exp/Cntr=.3,.1

Type RM Length L Ch R = 1 ,21242   ,370,371.8,409.17
XS GIS Cut Line= 2
     2094314.943      140020.431     2086149.996      140067.356
#Sta/Elev= 30
       0   58.13   288.5   54.65  310.63   50.35  362.28   50.49  398.69   55.01
  529.29   50.29  822.31   56.42 1078.59   51.37 1119.39   46.97 1159.39   46.34
 1171.11   43.38 1816.95    43.8 1867.95   39.35 1958.89   38.07 2808.79   37.83
 2812.36   34.93 2825.12   37.65  3645.4   38.98 4271.33   37.24 4446.15   38.94
  5080.6    37.2 5427.33   43.88  5569.7   43.13 6076.12   48.98 6384.93    47.3
 6818.49   49.29 6906.52   46.39 6932.04   48.96 7255.73   50.69 8165.08   50.53
#Mann= 3 , 0 , 0
       0     .12       0 2808.79     .06       0 2825.12     .12       0
#XS Ineff= 2 , 0
       0    2320      44               0
Bank Sta=2808.79,2825.12
Exp/Cntr=.3,.1

Type RM Length L Ch R = 1 ,20870   ,494.81,496.72,520.35
XS GIS Cut Line= 2
     2095926.533      139655.235     2084797.839      139683.844
#Sta/Elev= 30
       0   69.14 1147.47   67.17 2238.94    52.8 2621.97   56.01 2716.61   53.47
  2910.8   42.79 3459.55    43.7  3485.3   39.75 3524.08   40.98 3571.19    38.7
 4462.62   37.47 4465.65   34.16 4473.75   37.27 5306.47   37.38 5469.83   39.27
 5880.62   37.03 6063.54   38.96 6776.53    37.6 7032.61   42.92 7475.02    46.9
 7964.67   43.96 8005.65   45.71 8442.82   45.89 8519.21   48.55 9021.02   51.97
 9249.21   49.69 9537.63   51.64 9825.02   49.2610456.39   51.4111128.73   47.81
#Mann= 3 , 0 , 0
       0     .12       0 4462.62     .06       0 4473.75     .12       0
#XS Ineff= 2 , 0
       0    4150      44               0
Bank Sta=4462.62,4473.75
Exp/Cntr=.3,.1

Type RM Length L Ch R = 1 ,20374   ,458.56,783.75,474.18
XS GIS Cut Line= 2
     2094549.568      139269.631     2086149.996      139281.362
#Sta/Elev= 30
       0   64.31  710.35   57.71  930.07      58 1641.14   46.81 1676.81   43.81
  1985.8    48.9 2145.57   46.75 2152.03   48.47 2275.59   50.54 2727.71   46.09
 3155.59   37.87 3343.03   36.98 3353.55   33.87 3376.63   36.89 3494.29    38.6
 3629.46   36.84 4780.16   36.76 5170.21   39.06 5233.26   37.15 5549.42   36.97
 5638.97   37.93 5699.19   41.37 6273.64   42.68 6345.69   44.78 6398.78   42.06
 6466.03   41.81 6650.73   45.53 7025.08   47.07 7405.06   51.77 8399.58   50.24
#Mann= 3 , 0 , 0
       0     .12       0 3343.03     .06       0 3376.63     .12       0
#XS Ineff= 2 , 0
       0                    5700       0      42
Bank Sta=3343.03,3376.63
Exp/Cntr=.3,.1

Type RM Length L Ch R = 1 ,19590   ,547.3,429.64,429
XS GIS Cut Line= 2
     2094895.106      138957.774     2085631.079      138880.703
#Sta/Elev= 30
       0   66.99  691.97   62.15  732.62   60.55  988.23   60.28  1170.3   56.67
 1492.25    56.7 1674.21   53.57 1701.84    49.4 1754.07   49.89 1874.31   45.78
 2244.48   52.28 2333.86   52.35 3030.28   40.88 3448.86   41.43 3717.92   36.88
 4133.06   36.85 4144.59   38.22 4344.98   37.08 4358.21   33.96 4372.77   37.04
 5539.79   38.28 5576.69   36.66 6082.36   36.51 6631.98   41.43 6890.67      40
 7304.29   46.85 7537.98   45.06 7559.74   47.22 8210.32    53.8 9264.35   48.13
#Mann= 3 , 0 , 0
       0     .12       0 4344.98     .06       0 4372.77     .12       0
#XS Ineff= 2 , 0
       0    3660      42    6150       0      42
Bank Sta=4344.98,4372.77
Exp/Cntr=.3,.1

Type RM Length L Ch R = 1 ,19160   ,386.96,464.67,504.79
XS GIS Cut Line= 4
     2094743.134      138910.655     2091946.405       138826.19
     2091927.635       138525.87     2087019.281      138478.945
#Sta/Elev= 30
       0   66.45  991.63   56.46 1401.03   56.57 1580.76   52.85 1593.62   50.11
 1725.28   46.41 2186.57    51.5 2553.12   44.88 3091.64   42.15 3211.99   39.46
  3389.9   40.32 3508.86   38.46 3931.92    42.7 4163.83    36.9 4548.25   36.73
 4558.96   33.81 4572.27   36.67 4793.29   36.69 4843.88   38.53 5113.72   36.08
 5128.58   37.59 5718.46    38.1 5888.39   36.47  6881.1    37.6 6989.56   39.14
 7043.86   43.29 7409.13    42.6 7616.33   47.53 7779.42   47.37 8007.48   51.83
#Mann= 3 , 0 , 0
       0     .12       0 4548.25     .06       0 4572.27     .12       0
#XS Ineff= 2 , 0
       0    4170      42    6420       0      42
Bank Sta=4548.25,4572.27
Exp/Cntr=.3,.1

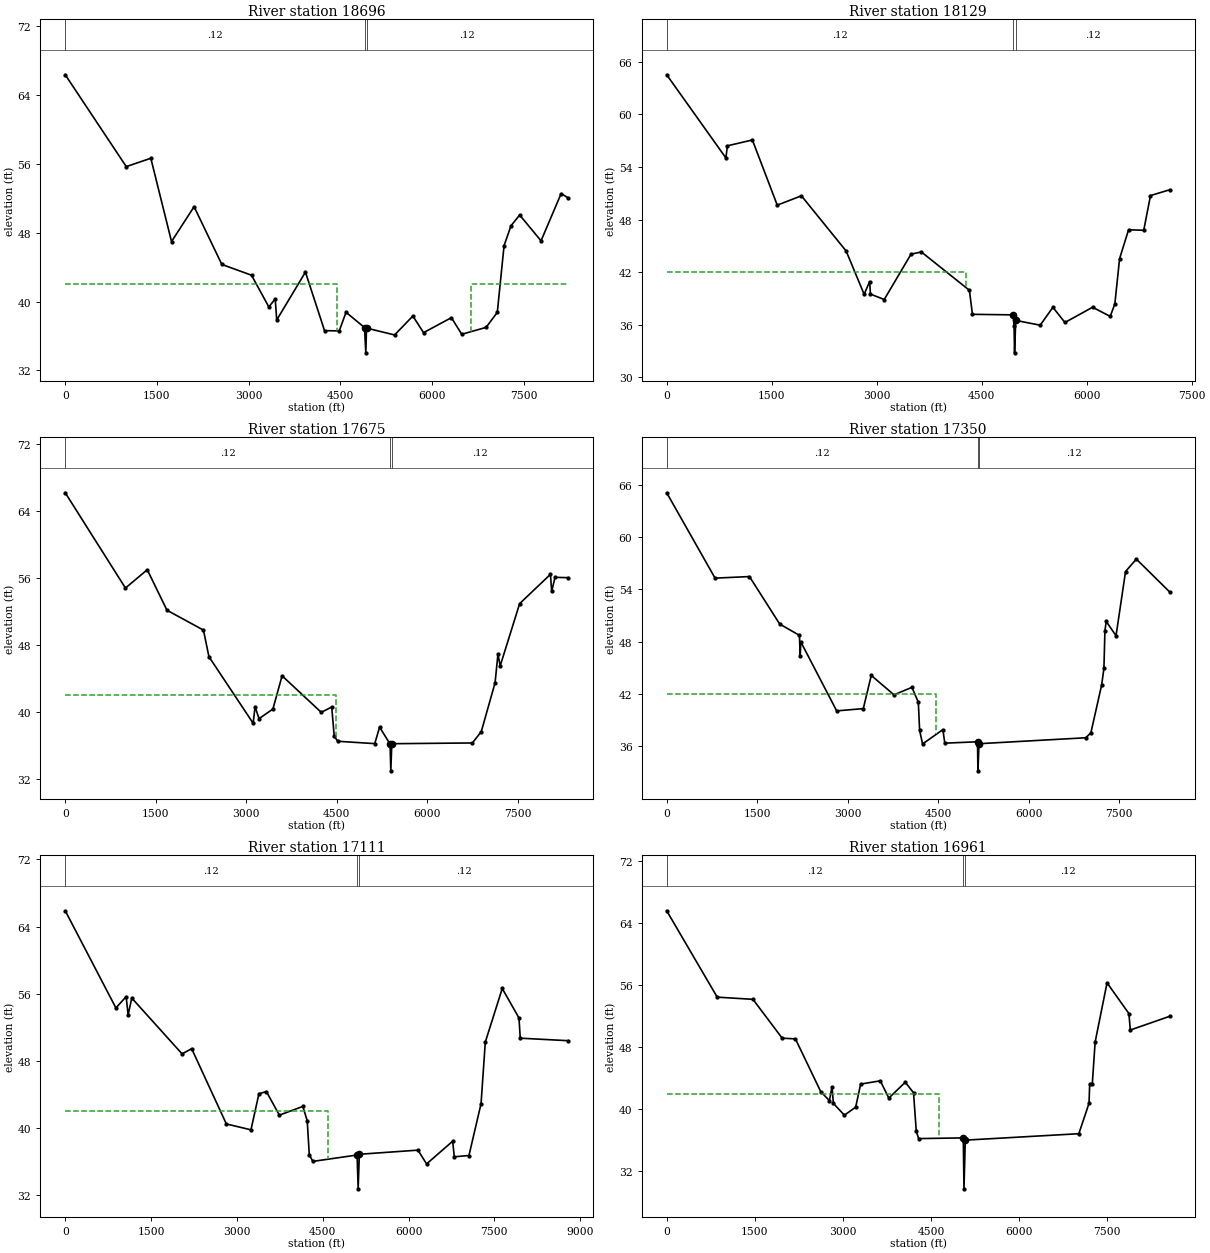
Type RM Length L Ch R = 1 ,18696   ,414.93,566.84,430.18
XS GIS Cut Line= 4
     2094725.548      138865.288     2091997.207      138757.388
     2091981.793      138418.272     2086864.227      137770.869
#Sta/Elev= 30
       0   66.37  998.05   55.69 1399.84   56.66 1738.63   46.97 2107.83   51.03
 2561.61   44.31 3047.08   43.06 3331.34   39.36 3434.78   40.32 3459.48   37.85
 3929.46   43.42 4241.83   36.61 4482.35   36.58 4593.49   38.75 4895.84   36.97
 4916.95   34.03 4928.75   36.91 5387.96   36.11  5686.9   38.31 5861.77   36.38
 6317.38   38.12 6486.45   36.19 6884.89   36.99 7068.27   38.74 7178.97    46.5
 7292.54   48.81 7434.35   50.06 7783.62   47.06 8112.38   52.55  8228.3   52.05
#Mann= 3 , 0 , 0
       0     .12       0 4895.84     .06       0 4928.75     .12       0
#XS Ineff= 2 , 0
       0    4450      42    6630       0      42
Bank Sta=4895.84,4928.75
Exp/Cntr=.3,.1

Type RM Length L Ch R = 1 ,18129   ,229.9,454.15,374.39
XS GIS Cut Line= 5
     2094555.434      138835.575     2092762.899       138713.57
      2092068.41       138394.48     2090932.825      138009.695
     2087563.611      137390.285
#Sta/Elev= 30
       0   64.51   845.7   55.03  867.67   56.41 1224.05   57.08 1579.59   49.65
 1924.69   50.71 2563.87   44.42 2820.89   39.48 2899.52   40.94 2910.64   39.51
 3107.87   38.89 3490.79   44.06 3638.68   44.31 4324.75   39.94 4368.17    37.2
 4950.91   37.14  4962.9   35.86 4969.81   32.81 4986.84   36.51 5335.94   35.96
 5517.59      38 5689.49   36.27 6084.92   38.01 6336.47   36.96 6402.43   38.38
 6470.31   43.55  6598.8   46.84 6815.47   46.78 6911.94   50.74 7185.65    51.4
#Mann= 3 , 0 , 0
       0     .12       0 4950.91     .06       0 4986.84     .12       0
#XS Ineff= 2 , 0
       0    4270      42               0
Bank Sta=4950.91,4986.84
Exp/Cntr=.3,.1

Type RM Length L Ch R = 1 ,17675   ,273.99,324.24,324.17
XS GIS Cut Line= 3
     2094694.719      138788.217     2093107.041       138695.73
     2086740.912      136460.649
#Sta/Elev= 30
       0   66.18  997.94    54.8 1359.38   56.99 1686.33   52.15 2290.64   49.78
 2382.03    46.6 3114.98   38.65 3146.39   40.63 3212.06    39.2 3442.04   40.35
 3594.46   44.32 4243.33   39.96 4417.18   40.59  4458.8   37.09 4518.07    36.5
 5130.57   36.22 5210.88   38.19 5384.16   36.17 5396.69   32.97 5413.13   36.21
 6749.08    36.3 6896.08   37.65 7125.07   43.49 7172.98   46.93 7209.39   45.49
 7532.14   52.94 8043.14   56.44 8063.04    54.4 8119.34   56.08 8337.46   56.04
#Mann= 3 , 0 , 0
       0     .12       0 5384.16     .06       0 5413.13     .12       0
#XS Ineff= 2 , 0
       0    4480      42               0
Bank Sta=5384.16,5413.13
Exp/Cntr=.3,.1

Type RM Length L Ch R = 1 ,17350   ,131.87,239.09,277.34
XS GIS Cut Line= 6
     2094588.281       138769.88     2092927.137      138554.025
     2092016.792       138300.63     2090731.047      137615.525
     2087361.834      136217.161     2086803.426      135973.151
#Sta/Elev= 30
       0   65.06  801.76   55.28 1371.45   55.46 1872.59   50.02 2200.15   48.72
 2211.76   46.38 2222.74   47.97 2816.83   40.07 3257.89   40.33 3389.73   44.13
 3766.84   41.91 4063.87   42.77 4169.56   41.06 4191.22   37.83    4240   36.28
 4576.18   37.92 4608.53   36.37 5150.55   36.53 5157.23    33.2 5175.56   36.31
 6945.62   36.99 7029.38   37.57 7208.31   43.07 7244.94   44.94 7261.68   49.24
 7283.02   50.32 7445.67   48.68 7603.44   56.04 7782.43   57.46 8334.23    53.7
#Mann= 3 , 0 , 0
       0     .12       0 5150.55     .06       0 5175.56     .12       0
#XS Ineff= 2 , 0
       0    4470      42               0
Bank Sta=5150.55,5175.56
Exp/Cntr=.3,.1

Type RM Length L Ch R = 1 ,17111   ,113.97,150.13,154
XS GIS Cut Line= 5
      2094648.47      138741.974      2093480.24      138567.601
      2092058.86      138279.543      2091041.51       137740.04
      2086725.49      135196.672
#Sta/Elev= 30
       0   65.89  885.59   54.31 1064.11   55.66 1099.48   53.49 1163.09   55.49
 2042.17   48.84 2209.62   49.46 2816.41   40.49 3246.45   39.79 3385.28   44.09
 3515.68   44.35 3743.23   41.54 4152.16   42.58 4229.67   40.88 4265.71   36.83
 4327.79   36.03 5101.53   36.79 5119.83   32.76 5140.79   36.88 6165.54   37.37
 6315.81   35.73 6771.48   38.43 6800.54   36.58 7056.83   36.73 7268.18   42.91
 7342.32   50.24 7638.67   56.63  7931.1   53.12 7953.46   50.71 8791.78   50.41
#Mann= 3 , 0 , 0
       0     .12       0 5101.53     .06       0 5140.79     .12       0
#XS Ineff= 2 , 0
       0    4600      42               0
Bank Sta=5101.53,5140.79
Exp/Cntr=.3,.1

Type RM Length L Ch R = 1 ,16961   ,154.59,176.76,174.94
XS GIS Cut Line= 6
     2094631.681       138720.59        2093510.         138560.
     2092161.424       138251.13        2091730.         138087.
     2090708.331      137435.162        2087030.         135063.
#Sta/Elev= 30
       0    65.6  860.73   54.46 1469.24   54.18 1966.85   49.17 2192.75   49.08
    2625   42.26 2771.44   41.12 2816.49   42.89 2839.08   40.76 3026.42   39.24
 3218.83   40.27 3303.73   43.25 3638.56   43.67 3783.52   41.44 4064.01   43.49
 4204.44   42.13 4251.21   37.15  4292.2   36.22 5052.07   36.31 5063.64   29.74
 5086.18   36.02 7020.13   36.85 7193.62   40.77 7205.04   43.25 7249.44   43.28
 7297.83   48.67 7500.43   56.31 7873.16   52.34 7896.75   50.22 8567.01   51.99
#Mann= 3 , 0 , 0
       0     .12       0 5052.07     .06       0 5086.18     .12       0
#XS Ineff= 2 , 0
       0    4640      42               0
Bank Sta=5052.07,5086.18
Exp/Cntr=.3,.1

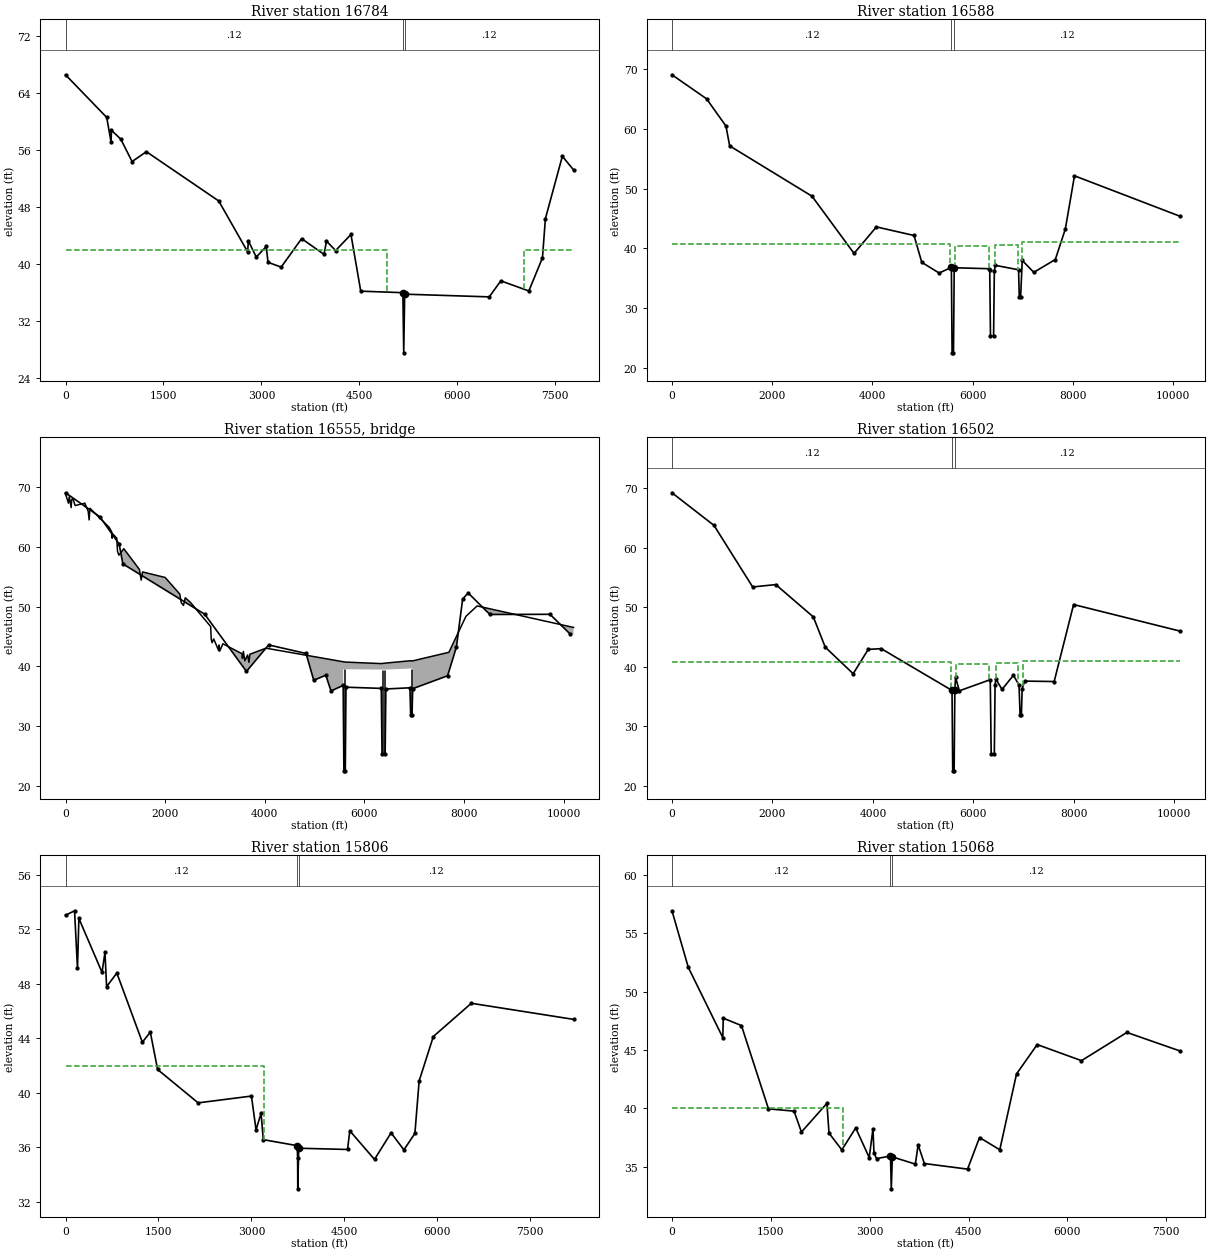
Type RM Length L Ch R = 1 ,16784   ,165.76,196.4,340.81
XS GIS Cut Line= 6
     2094788.168      138709.413        2093510.         138552.
     2092373.799         138273.        2091770.         138083.
        2090900.         137394.     2087936.277      135389.655
#Sta/Elev= 30
       0   66.59   630.8    60.6   696.8   57.19  703.65   58.78   846.9   57.55
 1019.22    54.4 1238.04   55.79 2346.02   48.87  2789.2   41.72 2799.27   43.28
 2921.07   40.99 3073.46   42.48 3100.82   40.25 3302.27   39.58 3614.98   43.58
 3958.05   41.37 3995.74   43.22 4135.97   41.91 4370.78   44.16 4520.51    36.2
 5165.64   35.99 5178.67   27.54 5192.92   35.78 6487.86    35.4 6665.17   37.65
 7094.04   36.23 7302.65   40.88 7347.53   46.38 7607.29   55.15  7778.7   53.23
#Mann= 3 , 0 , 0
       0     .12       0 5165.64     .06       0 5192.92     .12       0
#XS Ineff= 2 , 0
       0    4930      42    7025       0      42
Bank Sta=5165.64,5192.92
Exp/Cntr=.5,.3

Type RM Length L Ch R = 1 ,16588   ,87.06,86.08,76.17
XS GIS Cut Line= 6
     2095244.615      138730.922     2093487.973      138544.913
     2092953.979      138421.603     2091763.726      138062.123
     2088765.209      135323.392     2086465.377      134306.818
#Sta/Elev= 30
       0   69.04  689.64   65.02 1077.08   60.46 1151.26   57.14 2794.89   48.71
 3632.72   39.14 4078.82   43.58 4829.67   42.14 4983.87   37.65 5330.32   35.86
    5575    36.8    5589    22.5    5617    22.5    5631    36.5 5636.34   36.74
 6329.11   36.58    6340    36.3    6355    25.3    6417    25.3    6432    36.2
 6450.64   37.15    6915    36.4    6930    31.8    6956    31.8 6988.61   37.97
 7219.21   35.97 7648.59   38.12 7848.45   43.22  8031.1   52.1310136.62   45.36
#Mann= 3 , 0 , 0
       0     .12       0    5575     .06       0 5636.34     .12       0
#XS Ineff= 4 ,-1
       0    5555    40.8    5651    6320   40.45    6452    6895    40.6
    6991   11000      41
Bank Sta=5575,5636.34
Exp/Cntr=.5,.3

Type RM Length L Ch R = 3 ,16555   ,,,
BEGIN DESCRIPTION:
SR 1004 -- Columbus County Bridges 43, 41, 39 (left to right)
END DESCRIPTION:
Bridge Culvert--1,0,-1,-1, 0
Deck Dist Width WeirC Skew NumUp NumDn MinLoCord MaxHiCord MaxSubmerge Is_Ogee
20,25.3,2.6,0, 60, 60,,,.95,0,0,0,,
       0   58.94   76.31  113.67  124.73   149.6  193.47  387.98  455.11  474.72
  490.55  877.08  930.62  935.98  943.32 1028.39 1044.02 1071.57 1170.37 1483.58
  1519.7 1546.58 1999.99 2294.11 2324.11 2369.08 2404.56 2511.12 2914.21 2926.03
 2943.04 2975.75 3076.51    3083 3096.99 3159.57 3544.84 3551.09 3570.86 3599.75
 3655.84 3682.97 3702.22 4023.99    5575    5575    5631    5631    6340    6340
    6432    6432    6915    6915    6971    6971 7697.52 8039.64  8264.2   10200
   68.85    67.3    68.4   66.56   67.92   68.05    66.9    67.3   65.95    64.5
   66.45   63.25   62.44   61.44    62.2   61.44   59.26    58.6   59.68   56.21
   54.42   55.79   54.87   52.09   50.64   50.19   51.47   50.67   46.65   44.51
   43.94   44.58   42.59   43.57   42.55   43.77   42.09   41.32   42.48   40.92
   41.89   40.66   42.02   43.03   40.76   40.76    40.7    40.7   40.45   40.45
   40.54   40.54   40.92   40.92   40.91   40.91   42.34   48.36    50.1    46.5
                                                                                
                                                                                
                                                                                
                                                                                
                                            39.5    39.5                   39.45
   39.45                   39.62   39.62
       0   58.94   76.31  113.67  124.73   149.6  193.47  387.98  455.11  474.72
  490.55  877.08  930.62  935.98  943.32 1028.39 1044.02 1071.57 1170.37 1483.58
  1519.7 1546.58 1999.99 2294.11 2324.11 2369.08 2404.56 2511.12 2914.21 2926.03
 2943.04 2975.75 3076.51    3083 3096.99 3159.57 3544.84 3551.09 3570.86 3599.75
 3655.84 3682.97 3702.22 4023.99    5575    5575    5631    5631    6340    6340
    6432    6432    6915    6915    6971    6971 7697.52 8039.64  8264.2   10200
   68.85    67.3    68.4   66.56   67.92   68.05    66.9    67.3   65.95    64.5
   66.45   63.25   62.44   61.44    62.2   61.44   59.26    58.6   59.68   56.21
   54.42   55.79   54.87   52.09   50.64   50.19   51.47   50.67   46.65   44.51
   43.94   44.58   42.59   43.57   42.55   43.77   42.09   41.32   42.48   40.92
   41.89   40.66   42.02   43.03   40.76   40.76    40.7    40.7   40.45   40.45
   40.54   40.54   40.92   40.92   40.91   40.91   42.34   48.36    50.1    46.5
                                                                                
                                                                                
                                                                                
                                                                                
                                            39.5    39.5                   39.45
   39.45                   39.62   39.62
Pier Skew, UpSta & Num, DnSta & Num=,5594, 2 ,5594, 2 , 0 , 0 , 0 ,,
       2       2
      20   40.76
       2       2
      20   40.76
Pier Skew, UpSta & Num, DnSta & Num=,5612, 2 ,5612, 2 , 0 , 0 , 0 ,,
       2       2
      20   40.76
       2       2
      20   40.76
Pier Skew, UpSta & Num, DnSta & Num=,6359, 2 ,6359, 2 , 0 , 0 , 0 ,,
       2       2
      20   40.76
       2       2
      20   40.76
Pier Skew, UpSta & Num, DnSta & Num=,6377, 2 ,6377, 2 , 0 , 0 , 0 ,,
       2       2
      20   40.76
       2       2
      20   40.76
Pier Skew, UpSta & Num, DnSta & Num=,6395, 2 ,6395, 2 , 0 , 0 , 0 ,,
       2       2
      20   40.76
       2       2
      20   40.76
Pier Skew, UpSta & Num, DnSta & Num=,6413, 2 ,6413, 2 , 0 , 0 , 0 ,,
       2       2
      20   40.76
       2       2
      20   40.76
Pier Skew, UpSta & Num, DnSta & Num=,6933, 2 ,6933, 2 , 0 , 0 , 0 ,,
       2       2
      20   40.76
       2       2
      20   40.76
Pier Skew, UpSta & Num, DnSta & Num=,6951, 2 ,6951, 2 , 0 , 0 , 0 ,,
       2       2
      20   40.76
       2       2
      20   40.76
BR Coef=-1 , 1 , 0 ,, 0 ,,,.8,0,1.2,0,
WSPro=,,,, 1 ,,,, 0 ,,,, 0 ,,,,-1 ,-1 ,-1 , 0 , 0 , 0 , 0 , 0
BC Mult= 3 ,0,6100,0,6100
BC Mult= 3 ,5900,6750,5900,6750
BC Mult= 3 ,6550,11000,6550,11000
BR U #Sta/Elev= 30
       0   69.04  689.64   65.02 1077.08   60.46 1151.26   57.14 2794.89   48.71
 3632.72   39.14 4078.82   43.58 4829.67   42.14 4983.87   37.65 5226.06   38.51
 5330.32   35.86    5575    36.8    5589    22.5    5617    22.5    5631    36.5
    6340    36.3    6355    25.3    6417    25.3    6432    36.2    6915    36.4
    6930    31.8    6956    31.8    6971   36.25 7671.24   38.41 7848.45   43.22
 7973.27   51.25 8082.81   52.28 8520.76   48.67 9726.68    48.710136.62   45.36
BR U #Mann= 7
       0     .12    5575     .05    5631     .12    6340     .05    6432     .12
    6915     .05    6971     .12
BR D #Sta/Elev= 30
       0    69.2  836.93   63.72 1606.49   53.38 2066.43   53.78 2814.01   48.35
 3051.22   43.27 3607.13   38.81 3906.99    42.9 4165.16   43.02    5575      36
    5589    22.5    5617    22.5    5631      36    5645   38.23    5720   35.94
 6043.14   38.49 6069.16   36.69    6340      37    6355    25.3    6417    25.3
    6432      37 6784.82   38.58    6915    36.4    6930    31.8    6956    31.8
    6971    36.3 7581.57   37.03 7724.25   39.85 7995.02   50.4310113.66   45.97
BR D #Mann= 7
       0     .12    5575     .05    5631     .12    6340     .05    6432     .12
    6915     .05    6971     .12
BC Design=,, 0 ,, 0 ,,,,,,

Type RM Length L Ch R = 1 ,16502   ,552.11,696.03,476.79
XS GIS Cut Line= 6
 2095302.4586548  138654.0295341     2093376.458      138457.117
     2091923.475      138055.215     2091390.736      137649.557
     2088730.795       135216.86 2086544.2637459  134251.4766208
#Sta/Elev= 30
       0    69.2  836.93   63.72 1606.49   53.38 2066.43   53.78 2814.01   48.35
 3051.22   43.27 3607.13   38.81 3906.99    42.9 4165.16   43.02    5575      36
    5589    22.5    5617    22.5    5631      36    5645   38.23    5720   35.94
 6336.08   37.81    6355    25.3    6417    25.3    6432      37 6449.27    37.9
 6570.34   36.17 6797.31   38.55 6909.16    36.9    6930    31.8    6956    31.8
    6971    36.3 7021.69   37.57 7608.45    37.5 7995.02   50.4310113.66   45.97
#Mann= 3 , 0 , 0
       0     .12       0    5575     .06       0    5631     .12       0
#XS Ineff= 4 ,-1
       0    5555    40.8    5651    6320   40.45    6452    6895    40.6
    6991   11000      41
Bank Sta=5575,5631
Exp/Cntr=.5,.3

Type RM Length L Ch R = 1 ,15806   ,760.26,738,515.72
XS GIS Cut Line= 4
     2093625.694      138139.353     2092407.332      137602.827
     2088696.357      134741.352     2086606.139      134115.404
#Sta/Elev= 30
       0   53.04  145.68   53.37  193.38   49.15   215.7   52.81   589.5   48.85
  637.07   50.32  663.15    47.8  828.48    48.8 1240.23   43.72 1368.88   44.46
 1486.29   41.72 2140.86   39.27  3000.8   39.77 3075.07   37.29 3156.07   38.51
 3192.06   36.57 3738.87   36.13 3746.09   35.26 3748.56   32.96 3763.47   35.94
  4551.7   35.85 4588.17   37.22  4986.9   35.12 5254.36   37.07  5461.5   35.82
 5638.88   37.03 5707.49   40.88 5936.07   44.14 6549.68   46.58 8199.28    45.4
#Mann= 3 , 0 , 0
       0     .12       0 3738.87     .06       0 3763.47     .12       0
#XS Ineff= 2 , 0
       0    3210      42               0
Bank Sta=3738.87,3763.47
Exp/Cntr=.3,.1

Type RM Length L Ch R = 1 ,15068   ,175.76,252.42,181.98
XS GIS Cut Line= 3
     2093708.201       136923.08     2087789.088      134086.838
     2086648.426      133978.938
#Sta/Elev= 30
       0   56.94  247.54   52.09  771.14   46.07  778.51   47.73 1053.99    47.1
 1464.22   39.96 1852.69   39.76 1964.55   37.97 2351.29   40.43 2382.94   37.88
 2577.29   36.44 2787.97   38.32 2993.23   35.78 3050.15   38.26 3065.04   36.18
 3104.72   35.69 3315.86   35.92 3328.11    33.1 3344.03   35.84 3692.92   35.22
 3735.55   36.87 3829.85   35.27 4485.45   34.79 4666.94    37.5  4974.4   36.45
 5228.31   42.95  5541.9   45.47 6214.05   44.09 6903.01   46.51  7709.3   44.92
#Mann= 3 , 0 , 0
       0     .12       0 3315.86     .06       0 3344.03     .12       0
#XS Ineff= 2 , 0
       0    2600      40               0
Bank Sta=3315.86,3344.03
Exp/Cntr=.3,.1