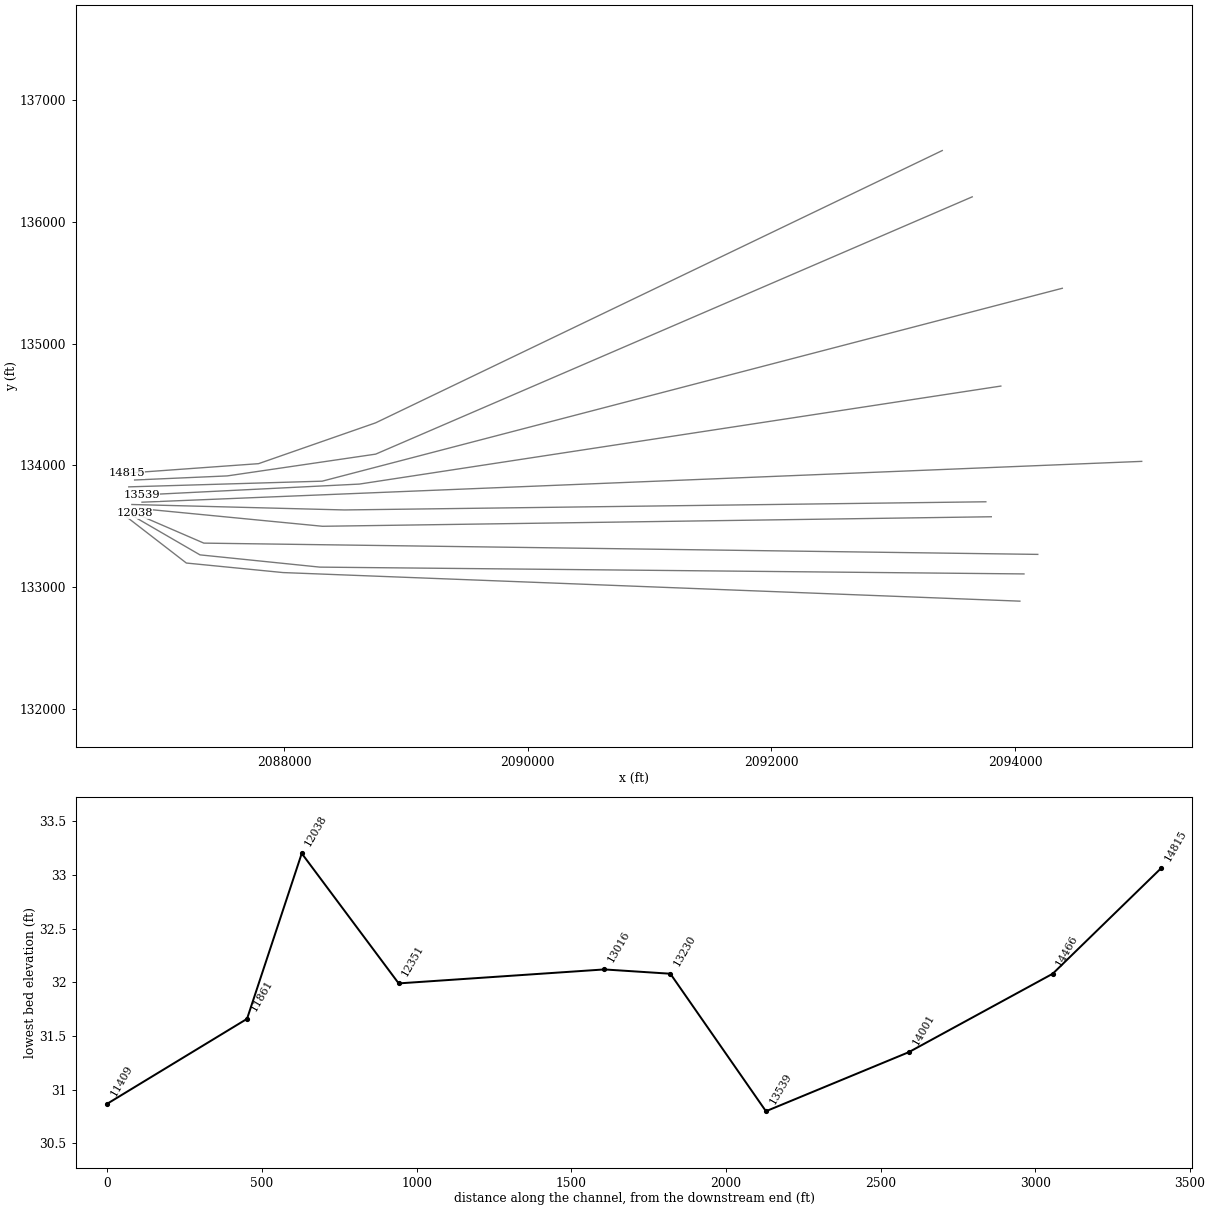
HEC-RAS study monieswamp.prj: MonieSwamp

--- monieswamp.g01 (geometry) --- (continued)

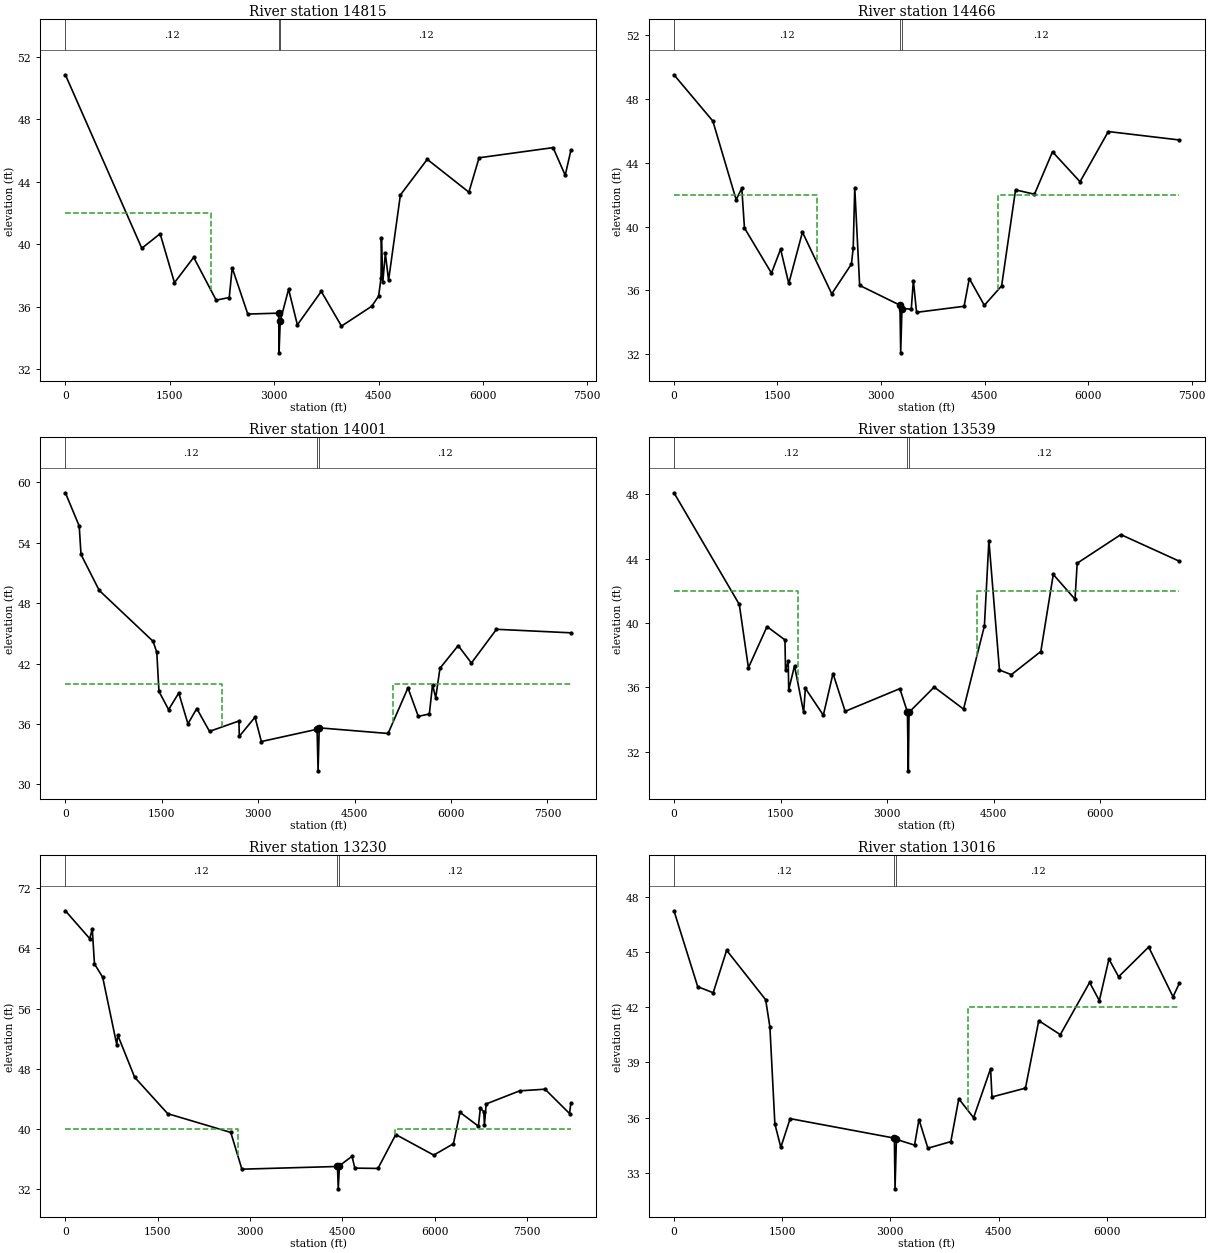
Type RM Length L Ch R = 1 ,14815   ,347.08,349.63,301.52
XS GIS Cut Line= 4
     2093402.141      136585.662     2088752.245      134350.135
     2087790.968      134014.806     2086706.737      133936.562
#Sta/Elev= 30
       0   50.85 1098.28   39.75 1361.48   40.68 1567.54   37.55 1843.75   39.17
 2167.11   36.43 2354.76    36.6 2397.26    38.5 2621.41   35.54 3065.63    35.6
 3070.48   33.06 3087.42   35.09 3207.81   37.13  3333.7   34.85 3677.26   36.99
 3967.75   34.77 4402.23   36.04 4501.44   36.69 4536.13   37.84 4541.35   40.39
  4561.4    37.6 4598.08   39.42 4644.55    37.7 4814.16   43.16  5200.2   45.44
 5798.43   43.34 5945.38   45.54 7008.64   46.19 7182.82   44.42 7264.51   46.02
#Mann= 3 , 0 , 0
       0     .12       0 3065.63     .06       0 3087.42     .12       0
#XS Ineff= 2 , 0
       0    2090      42               0
Bank Sta=3065.63,3087.42
Exp/Cntr=.3,.1

Type RM Length L Ch R = 1 ,14466   ,526.42,465.15,329.31
XS GIS Cut Line= 4
     2093648.049      136205.622     2088752.245      134093.049
     2087533.882      133914.207     2086773.803      133880.674
#Sta/Elev= 30
       0   49.52  562.98   46.62  901.17   41.68   982.5   42.41 1021.43   39.91
  1412.7   37.08 1544.88   38.58 1663.33   36.43  1861.5   39.65 2286.12   35.78
 2571.42   37.65 2597.09   38.66 2619.29   42.44 2690.24   36.31    3274   35.07
 3284.98   32.08  3303.3   34.86 3438.06   34.82  3468.7   36.61 3514.71   34.62
  4203.4      35 4278.64   36.74 4497.01   35.06 4747.38   36.28 4949.07    42.3
 5223.55   42.03 5484.73   44.69 5883.36   42.81 6292.85   45.96 7324.38   45.43
#Mann= 3 , 0 , 0
       0     .12       0    3274     .06       0  3303.3     .12       0
#XS Ineff= 2 , 0
       0    2070      42    4700       0      42
Bank Sta=3274,3303.3
Exp/Cntr=.3,.1

Type RM Length L Ch R = 1 ,14001   ,410.22,461.97,268.76
XS GIS Cut Line= 4
 2094387.3323509  135454.9311669     2088313.176      133871.037
     2086740.912      133824.794 2086725.9184837  133824.3530148
#Sta/Elev= 30
       0   58.97  215.16   55.67  243.24   52.84  526.89   49.27 1365.46   44.21
 1422.21   43.11 1455.95   39.24 1605.77   37.43 1764.02   39.08 1907.09   36.02
 2044.19   37.54 2242.49   35.27 2700.39    36.3 2705.97   34.78 2950.56   36.68
 3049.13   34.26  3916.1   35.48 3931.49   31.35  3949.9   35.62 5020.92   35.06
 5330.16   39.59 5490.81   36.76 5662.92      37 5712.28   39.88 5762.48   38.62
 5828.01   41.54 6111.48   43.79 6317.56   42.06 6707.22   45.41  7865.2   45.06
#Mann= 3 , 0 , 0
       0     .12       0  3916.1     .06       0  3949.9     .12       0
#XS Ineff= 2 , 0
       0    2440      40    5090       0      40
Bank Sta=3916.1,3949.9
Exp/Cntr=.3,.1

Type RM Length L Ch R = 1 ,13539   ,419.01,309.02,258.87
XS GIS Cut Line= 3
      2093882.78      134651.931     2088618.113      133847.141
     2086829.691       133757.72
#Sta/Elev= 30
       0   48.09  919.59   41.15 1047.87   37.21 1309.78   39.77 1562.54   38.94
 1570.14   37.08 1608.22    37.6 1615.38   35.84 1696.97   37.33 1825.35   34.44
 1849.89   35.93 2102.67   34.26 2238.79   36.85 2409.98    34.5 3179.54   35.91
 3286.35   34.46 3298.95    30.8 3309.16   34.44 3663.31   36.01 4076.37   34.64
  4370.2   39.81 4433.53   45.12 4582.23   37.07 4749.38   36.78  5164.4   38.22
 5339.79   43.01 5645.93   41.47 5676.33   43.71  6290.7   45.49 7116.48   43.83
#Mann= 3 , 0 , 0
       0     .12       0 3286.35     .06       0 3309.16     .12       0
#XS Ineff= 2 , 0
       0    1740      42    4260       0      42
Bank Sta=3286.35,3309.16
Exp/Cntr=.3,.1

Type RM Length L Ch R = 1 ,13230   ,226.19,213.66,183.01
XS GIS Cut Line= 2
     2095039.012      134033.611     2086834.564      133698.439
#Sta/Elev= 30
       0      69  396.18    65.3  436.61   66.61  472.32   61.95  605.83   60.18
  834.22   51.24  851.69   52.47  1124.8    46.9 1662.06   42.06 2686.43   39.57
 2867.38   34.69 4419.59   35.05  4432.4   32.08 4452.19   35.15 4655.73    36.4
 4701.76   34.83 5077.65   34.79  5366.6   39.29 5983.26   36.56 6303.49   38.07
 6409.81   42.24 6708.53    40.4 6740.78   42.76 6795.92   42.34 6806.93   40.55
 6834.78   43.35 7378.79   45.09 7791.53   45.31 8188.86   42.08  8211.3   43.47
#Mann= 3 , 0 , 0
       0     .12       0 4419.59     .06       0 4452.19     .12       0
#XS Ineff= 2 , 0
       0    2810      40    5360       0      40
Bank Sta=4419.59,4452.19
Exp/Cntr=.3,.1

Type RM Length L Ch R = 1 ,13016   ,129.29,664.62,129.8
XS GIS Cut Line= 3
     2093759.826      133701.832     2088495.159      133634.766
     2086751.448      133679.477
#Sta/Elev= 30
       0   47.25   329.3   43.12  543.76   42.79  730.31    45.1 1271.42   42.41
 1330.27   40.92  1399.1   35.65 1481.69   34.38 1610.75   35.94 3056.09   34.88
 3065.23   32.12 3084.13   34.81 3335.79    34.5 3397.23   35.89 3520.88   34.33
 3838.81   34.69 3949.51   37.02 4154.39   35.99 4390.15   38.66 4409.55   37.12
 4873.66    37.6 5058.24   41.27 5356.85   40.51 5763.47   43.35  5897.9   42.36
 6031.28   44.62  6165.3   43.66 6582.39   45.28 6919.62   42.57 7009.38   43.32
#Mann= 3 , 0 , 0
       0     .12       0 3056.09     .06       0 3084.13     .12       0
#XS Ineff= 2 , 0
       0                    4080       0      42
Bank Sta=3056.09,3084.13
Exp/Cntr=.3,.1

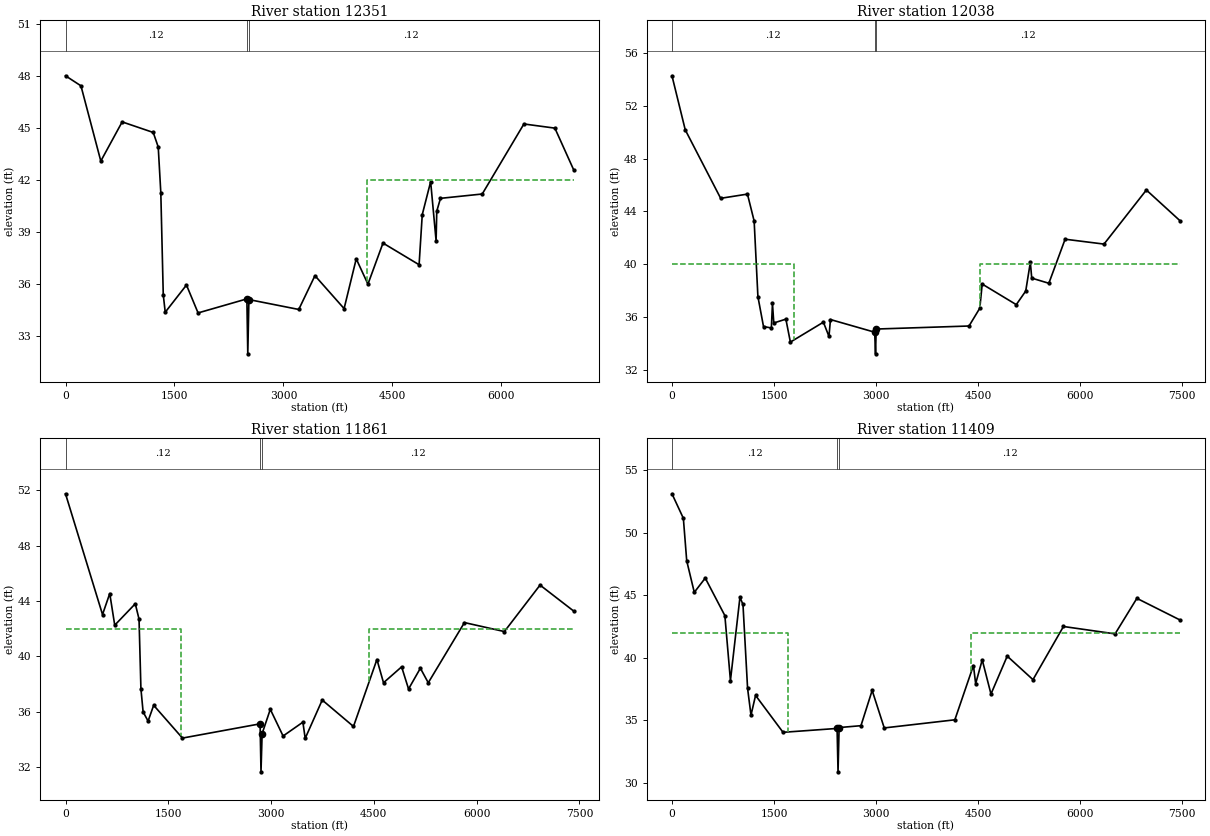
Type RM Length L Ch R = 1 ,12351   ,254.12,313.38,209.42
XS GIS Cut Line= 3
     2093804.536      133578.878     2088316.317      133500.634
     2086818.514      133645.944
#Sta/Elev= 30
       0   48.03   212.6   47.45  485.94   43.11  779.97   45.37 1207.76   44.76
 1276.41   43.92 1311.99   41.28 1345.64    35.4 1372.71   34.39 1665.21   35.96
 1824.93   34.35 2496.72   35.16 2509.19   31.99 2524.69   35.12 3210.82   34.55
  3433.8    36.5 3835.07    34.6 4002.14   37.47 4163.23   36.01 4370.47   38.38
 4867.45   37.13 4910.96   40.02 5026.43   41.92 5101.49   38.51  5110.7   40.22
 5162.04   40.96 5736.67   41.21 6310.29   45.25 6736.56   45.01 6993.61   42.62
#Mann= 3 , 0 , 0
       0     .12       0 2496.72     .06       0 2524.69     .12       0
#XS Ineff= 2 , 0
       0                    4150       0      42
Bank Sta=2496.72,2524.69
Exp/Cntr=.3,.1

Type RM Length L Ch R = 1 ,12038   ,175.1,176.88,178.5
XS GIS Cut Line= 3
     2094186.046      133269.877     2087342.072      133362.364
     2086771.741      133608.993
#Sta/Elev= 30
       0   54.28  195.12   50.18  715.53   44.99 1109.12   45.31  1207.6   43.27
 1262.86   37.54 1345.09   35.27  1460.8   35.16 1476.68   37.02 1496.35   35.54
 1673.99   35.83    1740   34.09 2225.16    35.6  2307.1   34.52  2329.1    35.8
 2978.92   34.84  2991.3    33.2 3001.32   35.08 4365.35   35.31 4523.76   36.66
 4558.92   38.49 5059.73   36.93 5198.69   37.96 5266.45   40.14 5286.95   38.94
 5538.48   38.55 5777.38   41.89 6348.94   41.52 6971.51   45.62 7465.98   43.29
#Mann= 3 , 0 , 0
       0     .12       0 2978.92     .06       0 3001.32     .12       0
#XS Ineff= 2 , 0
       0    1790      40    4525       0      40
Bank Sta=2978.92,3001.32
Exp/Cntr=.3,.1

Type RM Length L Ch R = 1 ,11861   ,161.24,451.8,119.21
XS GIS Cut Line= 4
     2094072.799      133109.417     2088293.962      133165.305
      2087310.33      133265.904     2086751.448      133590.055
#Sta/Elev= 30
       0   51.76  540.13   43.03  645.67   44.55   718.4   42.26 1018.25   43.81
 1073.04    42.7 1100.62   37.66 1132.51   35.99 1205.06   35.33 1286.65   36.47
 1706.61    34.1 2839.54   35.13 2852.88   31.66  2869.2   34.42 2988.65   36.18
 3175.12   34.25 3464.21   35.25 3497.76   34.08 3746.37   36.85 4202.52   34.94
 4544.63   39.78 4640.74    38.1 4904.94   39.25 5006.15   37.65 5178.64   39.15
 5293.77    38.1 5821.69   42.45 6404.71    41.8 6925.07   45.16 7413.95   43.29
#Mann= 3 , 0 , 0
       0     .12       0 2839.54     .06       0  2869.2     .12       0
#XS Ineff= 2 , 0
       0    1680      42    4430       0      42
Bank Sta=2839.54,2869.2
Exp/Cntr=.3,.1

Type RM Length L Ch R = 1 ,11409   ,337.95,342.33,246.3
XS GIS Cut Line= 4
     2094039.267      132885.864     2087992.165      133120.595
     2087198.553      133198.838     2086706.737      133578.878
#Sta/Elev= 30
       0    53.1  167.45   51.14  216.85   47.74   328.1   45.22  489.53   46.36
  777.74   43.36  859.79   38.17  999.55   44.83 1044.11   44.25 1111.86   37.54
 1161.92    35.4 1229.26   36.98 1633.15   34.03 2427.96   34.34 2441.92   30.87
 2457.85   34.41    2779   34.56 2943.75   37.38 3121.31   34.38 4159.69   35.03
 4432.87   39.37 4465.58   37.92  4562.3   39.82 4690.88   37.09 4929.91   40.12
 5308.49   38.24 5756.61   42.49 6515.75    41.9 6836.37   44.74 7470.66   43.01
#Mann= 3 , 0 , 0
       0     .12       0 2427.96     .06       0 2457.85     .12       0
#XS Ineff= 2 , 0
       0    1700      42    4400       0      42
Bank Sta=2427.96,2457.85
Exp/Cntr=.3,.1