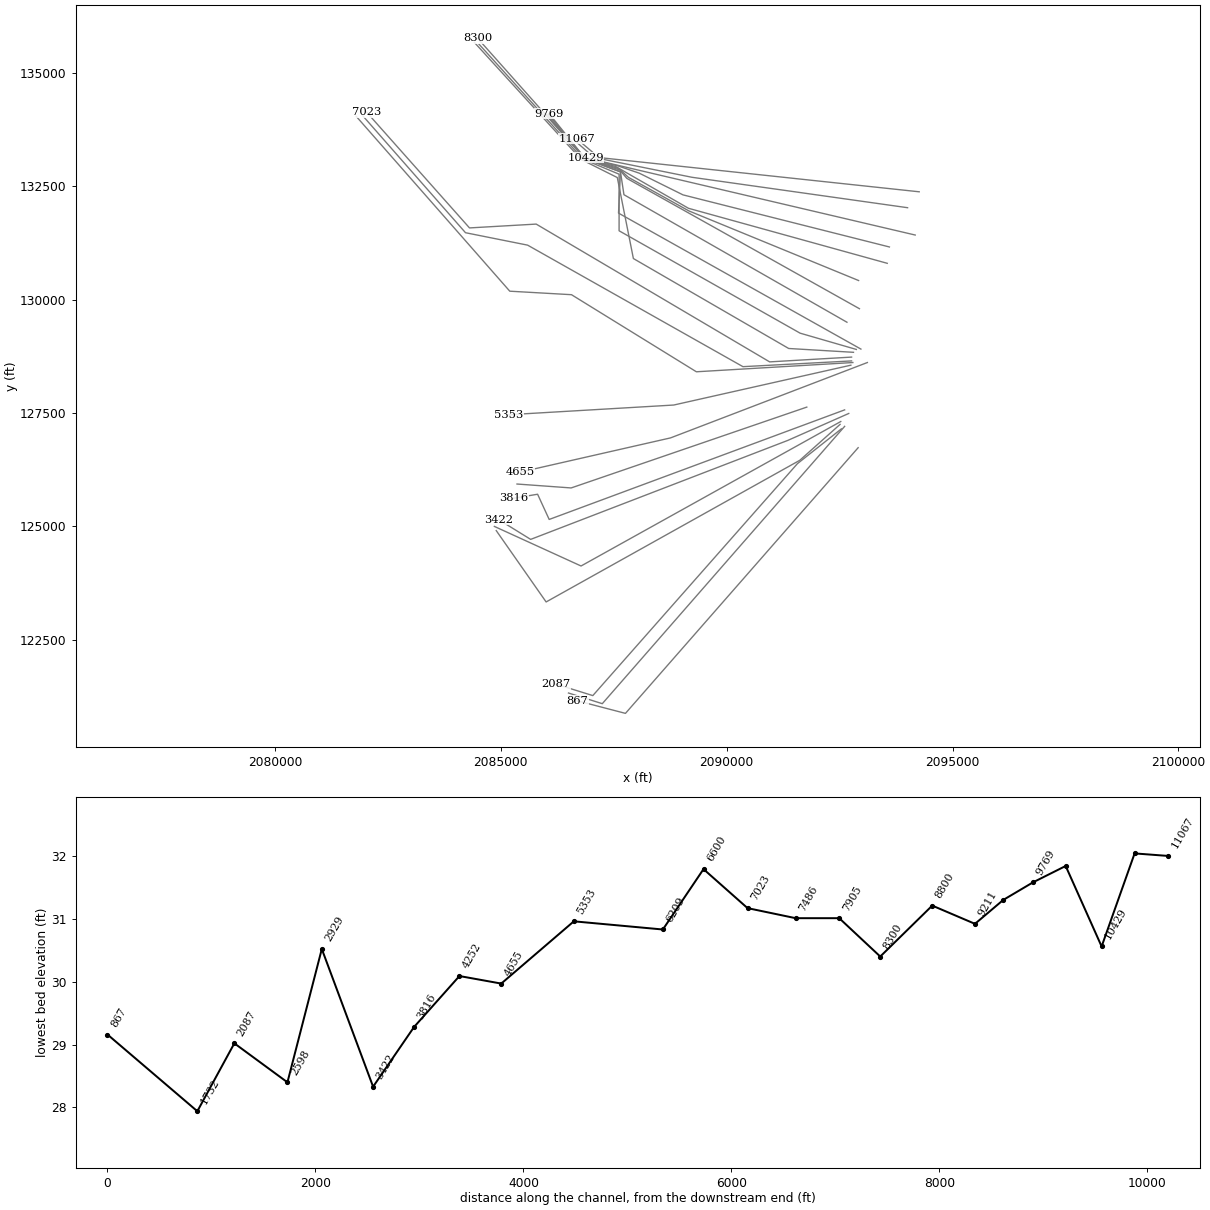
HEC-RAS study monieswamp.prj: MonieSwamp

--- monieswamp.g01 (geometry) --- (continued)

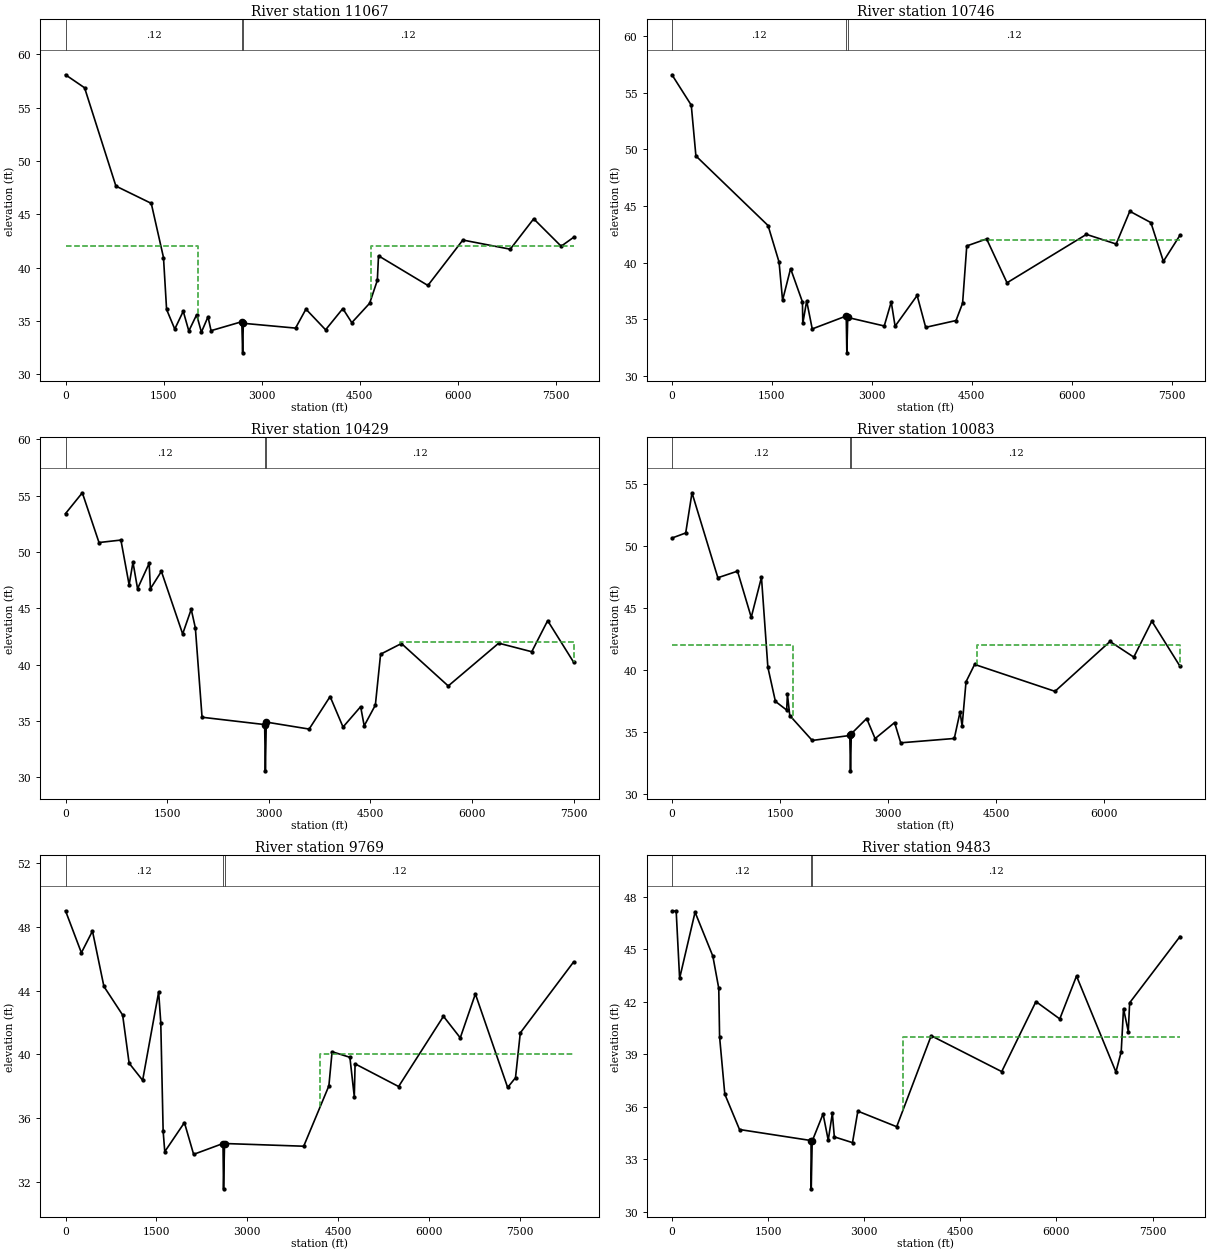
Type RM Length L Ch R = 1 ,11067   ,304.2,320.99,265.49
XS GIS Cut Line= 3
     2094263.117      132375.845     2087172.514      133131.148
     2086679.255      133547.336
#Sta/Elev= 30
       0   58.08  292.02   56.86  771.45   47.64 1312.58   46.02 1499.75   40.94
 1547.15   36.07 1672.26   34.23 1802.03    35.9 1887.53   34.05 2006.86   35.57
 2080.22   33.94 2181.02   35.38 2227.83   34.08  2698.3   34.92 2711.24      32
 2721.63   34.77 3521.01   34.32 3680.04    36.1 3980.88   34.16  4244.6   36.15
 4382.07   34.83 4655.25   36.65 4772.75    38.8 4791.03    41.1 5546.54   38.32
 6081.46   42.58 6807.35   41.72 7165.95   44.57  7586.4      42 7776.09   42.83
#Mann= 3 , 0 , 0
       0     .12       0  2698.3     .06       0 2721.63     .12       0
#XS Ineff= 2 , 0
       0    2030      42    4680       0      42
Bank Sta=2698.3,2721.63
Exp/Cntr=.3,.1

Type RM Length L Ch R = 1 ,10746   ,353.39,317.29,246.09
XS GIS Cut Line= 4
     2094005.734      132025.186     2089232.883      132695.845
     2087064.422      133131.772     2086617.316       133522.99
#Sta/Elev= 30
       0   56.57  289.53   53.89  359.27   49.41 1442.22   43.27 1607.26   40.05
 1660.09   36.68 1780.38   39.47 1958.44   36.53 1963.62   34.63 2021.76   36.62
 2105.44   34.15 2615.61   35.29 2624.66   32.04 2638.49   35.16  3186.1   34.41
 3291.19   36.53 3349.17   34.39 3680.04    37.1 3808.06   34.29 4263.52   34.89
  4362.3   36.42 4424.72   41.47 4722.87   42.09    5029   38.22 6220.83   42.49
 6667.09   41.64 6872.06   44.53 7188.54   43.53 7375.96   40.11 7625.68   42.42
#Mann= 3 , 0 , 0
       0     .12       0 2615.61     .06       0 2638.49     .12       0
#XS Ineff= 2 , 0
       0                    4640       0      42
Bank Sta=2615.61,2638.49
Exp/Cntr=.3,.1

Type RM Length L Ch R = 1 ,10429   ,353.38,345.79,345.55
XS GIS Cut Line= 3
 2094174.3859817  131422.8178602     2094164.648      131425.092
 2086873.4469817  133127.8278602
#Sta/Elev= 30
       0   53.41  248.05   55.26  494.29   50.84  817.61   51.06  938.91   47.08
  995.61   49.09 1063.27   46.74 1234.15   48.99 1253.56   46.74 1414.97   48.28
 1728.82   42.72 1855.19   44.91 1916.41   43.25 2015.13   35.32 2938.84   34.67
 2949.59   30.56 2962.83   34.89 3595.28   34.27 3904.85   37.16 4095.61   34.45
 4355.62   36.26  4407.8   34.56 4572.71    36.4 4649.74   40.92 4957.25   41.87
 5648.22    38.1 6393.01    41.9 6880.39   41.14 7115.36    43.9 7497.38   40.22
#Mann= 3 , 0 , 0
       0     .12       0 2938.84     .06       0 2962.83     .12       0
#XS Ineff= 2 , 0
       0                    4940       0      42
Bank Sta=2938.84,2962.83
Exp/Cntr=.3,.1

Type RM Length L Ch R = 1 ,10083   ,313.62,313.97,288.9
XS GIS Cut Line= 6
     2093603.464      131159.784     2089035.019      132307.875
     2088066.318      132786.246     2087611.865      132941.716
        2086860.         133127.        2086860.         133135.
#Sta/Elev= 30
       0   50.61  190.69   51.02  277.98   54.26  637.12   47.41  909.69   47.94
 1100.44   44.22 1242.51   47.44 1331.47   40.19 1436.02   37.44 1592.35   36.74
 1602.85   38.02 1635.48    36.3 1947.27   34.29 2468.75   34.69 2478.58   31.84
 2489.91   34.83 2703.25   36.06 2820.29   34.44 3090.91   35.73 3175.84    34.1
 3919.65   34.45 3999.91   36.59 4028.14   35.45 4082.55   39.02  4201.9   40.42
 5317.89   38.25 6081.53   42.27  6411.8   41.01 6662.54   43.91 7053.56   40.27
#Mann= 3 , 0 , 0
       0     .12       0 2468.75     .06       0 2489.91     .12       0
#XS Ineff= 2 , 0
       0    1680      42    4230       0      42
Bank Sta=2468.75,2489.91
Exp/Cntr=.3,.1

Type RM Length L Ch R = 1 ,9769    ,338.16,286.38,216.14
XS GIS Cut Line= 5
     2093555.818      130799.525     2089155.741      132012.423
     2087544.445      132933.164      2086863.48      133120.286
      2086069.32      134099.388
#Sta/Elev= 30
       0      49  262.15   46.37  445.12   47.73  634.05   44.26  943.05   42.47
 1050.37   39.45  1273.3   38.38 1537.62   43.91 1572.61      42 1611.77    35.2
 1638.72   33.91 1963.12   35.73 2115.05   33.74 2599.94   34.42  2608.8   31.58
 2625.62   34.42 3932.26   34.25  4347.8   38.03 4400.71   40.17  4694.7   39.82
 4767.51   37.35 4780.59   39.41 5498.85   37.99 6239.44   42.39 6516.78   41.04
 6766.21   43.79 7298.96   37.93  7428.7   38.54 7507.81   41.35 8386.89   45.79
#Mann= 3 , 0 , 0
       0     .12       0 2599.94     .06       0 2625.62     .12       0
#XS Ineff= 2 , 0
       0                    4200       0      40
Bank Sta=2599.94,2625.62
Exp/Cntr=.3,.1

Type RM Length L Ch R = 1 ,9483    ,344.03,271.96,220.35
XS GIS Cut Line= 6
     2092921.239      130420.086     2089165.654      131954.058
     2087825.633      132694.595     2087614.051      132888.546
        2086860.         133115.     2086049.224      134087.512
#Sta/Elev= 30
       0   47.16   65.38   47.19  119.37   43.33  360.29   47.11  637.71    44.6
  730.17   42.76  742.98   39.99  824.47   36.71 1053.97   34.69 2169.95   34.06
 2172.94    31.3 2188.21   34.03 2358.09   35.58 2438.54   34.08 2502.79   35.62
 2533.58   34.27 2817.35   33.94 2900.62   35.74 3506.82   34.85 4045.25   40.05
  5145.7      38 5679.99      42 6051.88   41.01 6313.06   43.46 6928.03   37.98
 7010.58   39.13 7046.54    41.6    7121   40.29 7142.21   41.93 7928.31   45.72
#Mann= 3 , 0 , 0
       0     .12       0 2169.95     .06       0 2188.21     .12       0
#XS Ineff= 2 , 0
       0                    3600       0      40
Bank Sta=2169.95,2188.21
Exp/Cntr=.3,.1

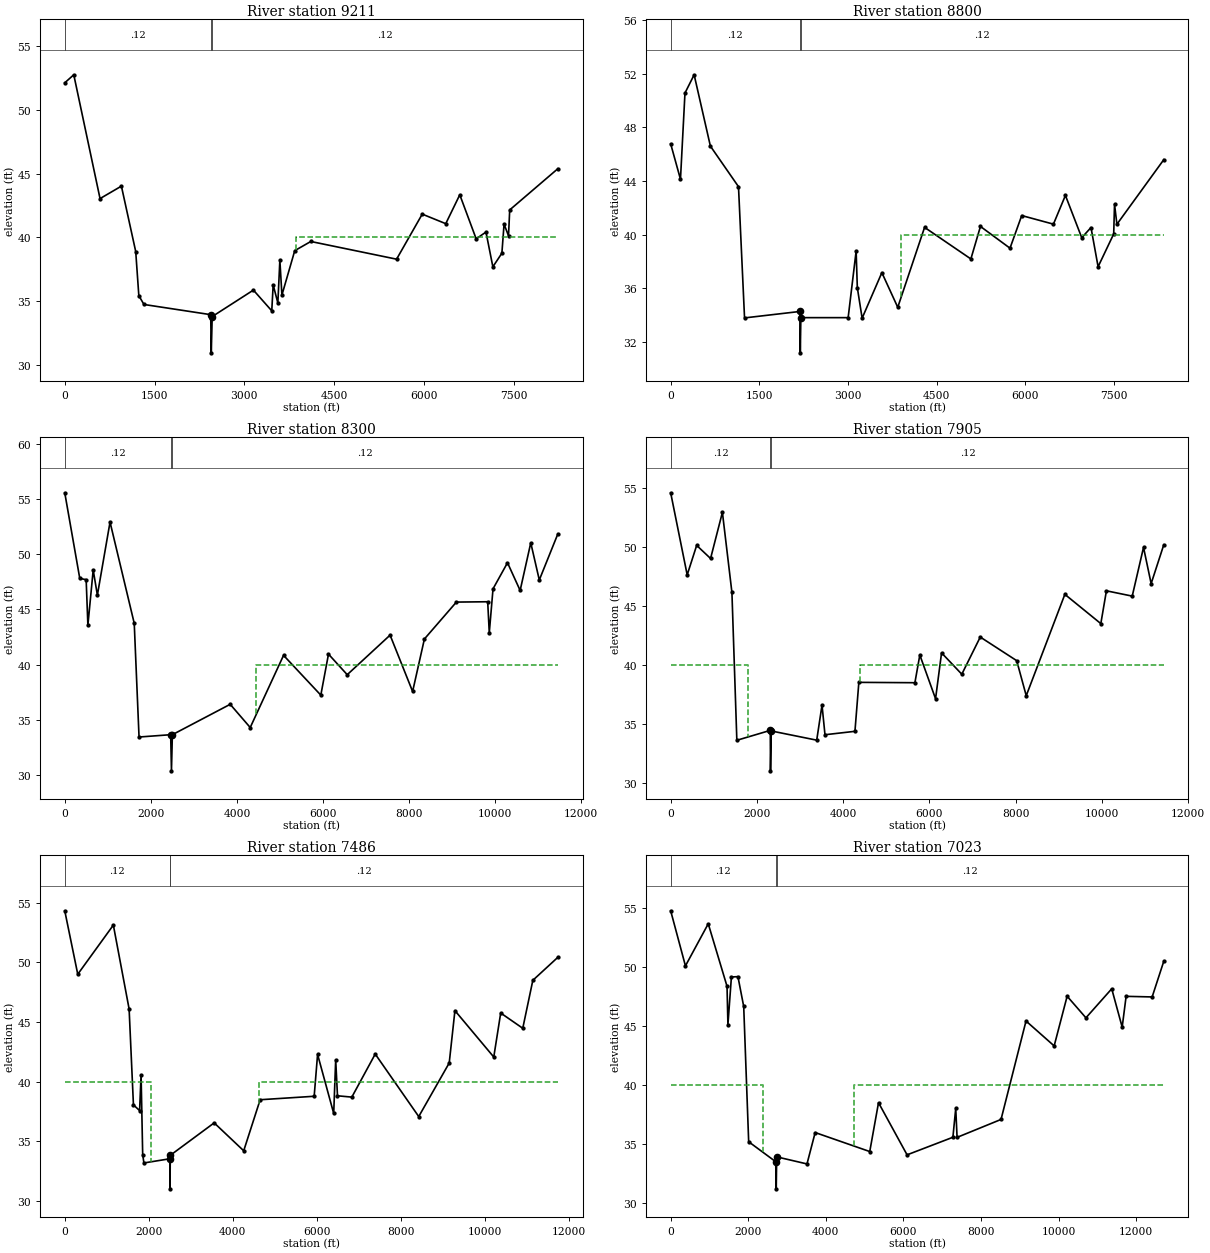
Type RM Length L Ch R = 1 ,9211    ,393.75,410.98,374.84
XS GIS Cut Line= 5
     2092939.931      129798.885     2087790.449      132672.354
     2087633.973       132857.28     2086860.344      133111.833
     2086018.393      134080.465
#Sta/Elev= 30
       0   52.14  150.62   52.77  589.33   43.04  946.17   44.02 1185.37   38.88
 1237.36   35.41 1323.42   34.72 2438.16   33.92 2447.27   30.92 2462.87   33.77
 3151.19   35.85 3457.99   34.22 3481.51   36.26 3559.72   34.84 3593.28    38.2
 3627.51   35.46 3841.94   38.95  4110.1   39.67    5543   38.28 5971.68   41.82
 6364.35   41.07 6598.75   43.34 6872.17   39.88  7036.3   40.41 7151.22   37.68
 7302.04   38.75 7338.29   41.03  7412.7   40.12 7432.66   42.15 8237.04   45.39
#Mann= 3 , 0 , 0
       0     .12       0 2438.16     .06       0 2462.87     .12       0
#XS Ineff= 2 , 0
       0                    3860       0      40
Bank Sta=2438.16,2462.87
Exp/Cntr=.3,.1

Type RM Length L Ch R = 1 ,8800    ,393.27,500.06,390
XS GIS Cut Line= 5
      2092663.51       129500.72     2087727.323      132311.739
        2087650.         132817.        2086860.         133108.
        2085990.         134088.
#Sta/Elev= 30
       0   46.77  165.82   44.13  241.97   50.55  397.09   51.91  671.96    46.6
 1147.65   43.58 1249.96   33.81 2186.12   34.29 2193.25   31.21  2202.8   33.83
 3003.14   33.83 3138.14   38.78 3158.46   36.06 3239.69   33.79 3573.66   37.18
 3842.54    34.6 4296.38   40.55 5079.72    38.2 5241.81   40.62 5741.84      39
 5940.19   41.43 6476.79   40.79 6679.63   42.93 6955.93   39.78 7112.34   40.54
 7232.63   37.62 7496.68   40.06 7510.67   42.28 7550.78   40.78 8343.95   45.59
#Mann= 3 , 0 , 0
       0     .12       0 2186.12     .06       0  2202.8     .12       0
#XS Ineff= 2 , 0
       0                    3900       0      40
Bank Sta=2186.12,2202.8
Exp/Cntr=.3,.1

Type RM Length L Ch R = 1 ,8300    ,359.14,394.38,343.8
XS GIS Cut Line= 6
 2092972.5706558  128908.8297698      2092955.11      128918.583
     2087606.919      131905.993        2087650.         132816.
        2086860.         133106. 2084489.3306839  135758.5108291
#Sta/Elev= 30
       0   55.56  348.86   47.81  497.19    47.7  537.33   43.58  660.68   48.57
  757.91    46.3 1051.89   52.91 1614.11   43.75 1725.79   33.46 2460.72   33.67
  2479.1    30.4 2499.81   33.67 3843.47   36.42 4308.71   34.32 5083.17   40.85
 5948.85   37.25 6127.07   40.96 6562.45    39.1 7558.21   42.68 8081.72   37.58
 8355.56   42.33 9098.47   45.67 9826.02    45.7 9862.72   42.89 9949.89   46.87
10286.02   49.2310579.66   46.7210826.67   51.0311024.95   47.6711456.09   51.84
#Mann= 3 , 0 , 0
       0     .12       0 2460.72     .06       0 2499.81     .12       0
#XS Ineff= 2 , 0
       0                    4450       0      40
Bank Sta=2460.72,2499.81
Exp/Cntr=.3,.1

Type RM Length L Ch R = 1 ,7905    ,421.51,419.09,399.16
XS GIS Cut Line= 6
     2092871.464      128901.117     2091627.065      129259.673
     2087619.681      131516.463        2087620.         132764.
        2086820.         133096.      2084519.23      135629.305
#Sta/Elev= 30
       0   54.58  383.04   47.62  602.69   50.12  924.89   49.01 1199.24   52.92
 1419.98   46.13 1534.08    33.6 2309.19   34.44 2314.21   31.01 2332.05   34.39
 3385.82   33.61 3508.55   36.58 3577.43   34.07 4271.92   34.36 4362.42   38.51
 5661.88   38.48 5776.05   40.83 6140.78   37.12 6279.98   41.01  6749.3    39.2
 7177.19   42.35 8021.66   40.35 8243.06   37.38 9138.47   45.97 9972.15   43.49
10101.91   46.2710700.31   45.8210962.11   49.95 11138.9   46.8811431.63   50.17
#Mann= 3 , 0 , 0
       0     .12       0 2309.19     .06       0 2332.05     .12       0
#XS Ineff= 2 , 0
       0    1790      40    4400       0      40
Bank Sta=2309.19,2332.05
Exp/Cntr=.3,.1

Type RM Length L Ch R = 1 ,7486    ,472.51,462.92,452.69
XS GIS Cut Line= 6
     2092808.189      128837.843     2091373.967      128922.209
     2087936.053       130904.81        2087580.         132690.
        2086780.         133089.     2084413.773      135671.488
#Sta/Elev= 30
       0   54.32  309.34      49 1156.29   53.12  1531.6   46.09 1634.44   38.05
 1781.11   37.57 1816.25   40.57 1854.57   33.87 1884.22   33.18 2499.59   33.53
 2505.04   31.01 2511.33   33.82 3556.07   36.54 4258.66    34.2 4650.18   38.48
 5935.75   38.77 6016.85   42.28 6400.61   37.33 6447.83   41.83 6490.42   38.81
 6831.93    38.7 7388.77   42.31 8424.15   37.07 9149.65   41.56 9285.36   45.95
10209.85   42.0610374.85   45.7510899.83   44.4711139.59   48.4911735.17   50.42
#Mann= 3 , 0 , 0
       0     .12       0 2499.59     .06       0 2511.33     .12       0
#XS Ineff= 2 , 0
       0    2050      40    4620       0      40
Bank Sta=2499.59,2511.33
Exp/Cntr=.3,.1

Type RM Length L Ch R = 1 ,7023    ,404.18,423.45,416.4
XS GIS Cut Line= 5
     2092766.006      128732.385     2090952.137      128626.928
      2085784.72      131664.104     2084308.315      131579.738
     2082030.434      134131.809
#Sta/Elev= 30
       0   54.73  380.64   50.06   968.5   53.63 1452.74   48.33 1475.59   45.08
 1565.46   49.12 1734.02   49.15 1882.61   46.62 2010.63   35.16 2707.32   33.47
 2720.93   31.17 2732.74   33.88 3513.71   33.28 3724.54   35.94 5131.56   34.33
 5357.48   38.47 6093.54   34.05 7274.83   35.54 7348.03   37.99  7382.5   35.53
 8515.54   37.05 9159.54   45.39 9884.97   43.2810219.37   47.4910703.88   45.66
 11368.8   48.1211638.31   44.8711739.59   47.4812410.83   47.4312710.42   50.45
#Mann= 3 , 0 , 0
       0     .12       0 2707.32     .06       0 2732.74     .12       0
#XS Ineff= 2 , 0
       0    2380      40    4720       0      40
Bank Sta=2707.32,2732.74
Exp/Cntr=.3,.1

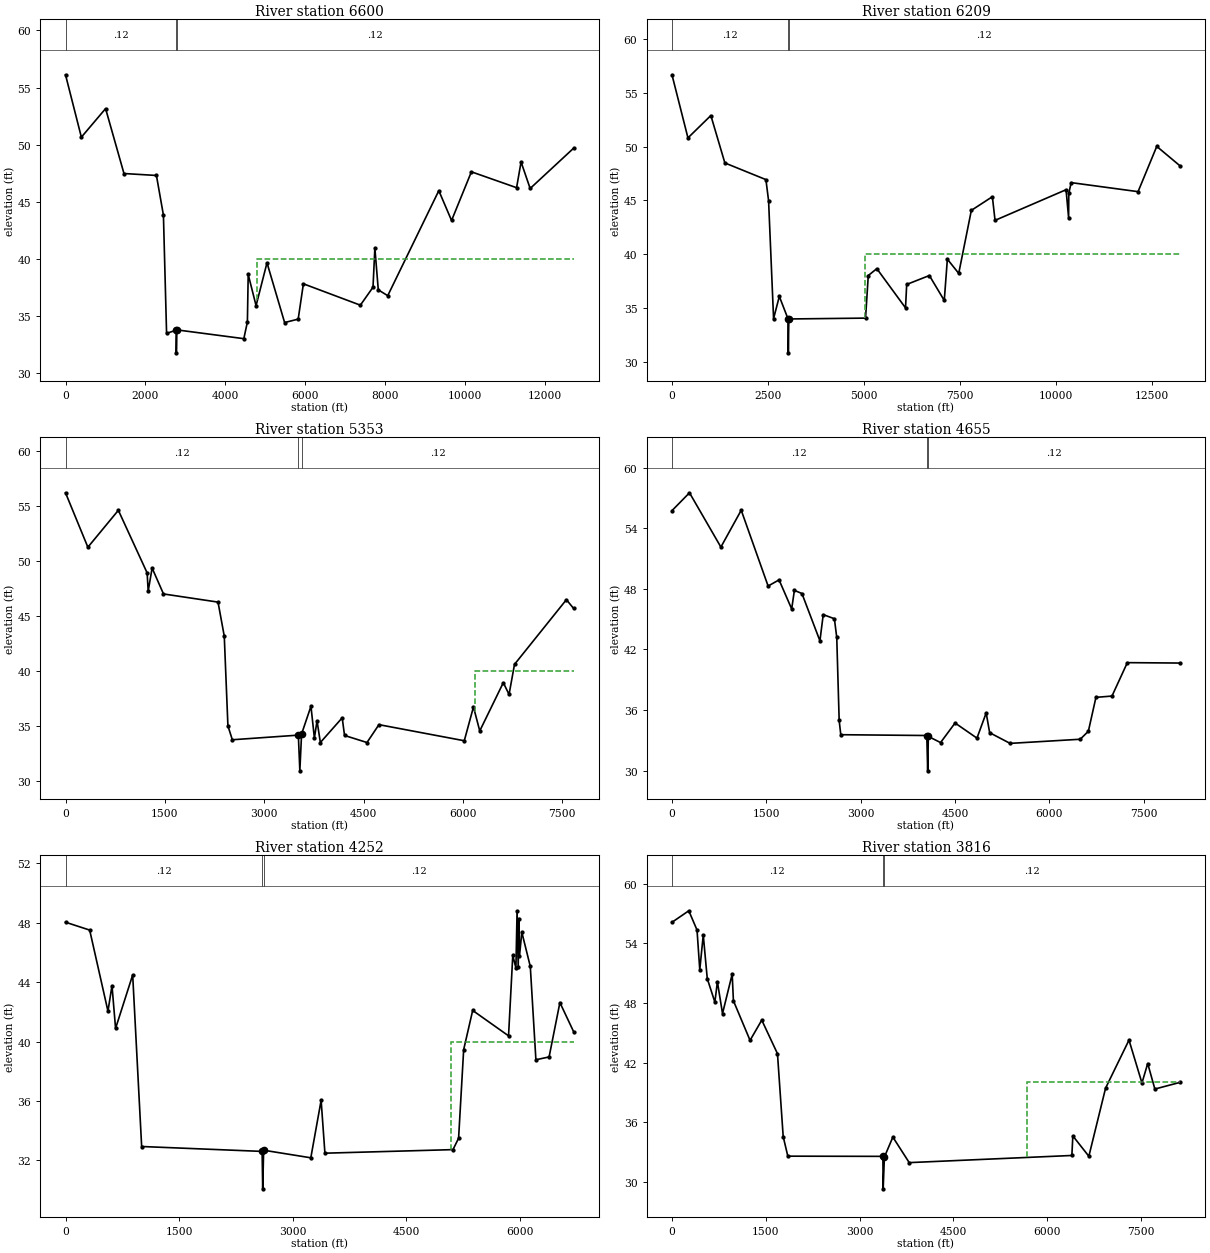
Type RM Length L Ch R = 1 ,6600    ,217.79,391.02,587.68
XS GIS Cut Line= 5
     2092766.006      128648.019     2090361.576       128521.47
     2085594.897      131200.091        2084220.         131474.
        2081950.         134047.
#Sta/Elev= 30
       0   56.12  396.72   50.66 1002.64   53.16 1462.47   47.48 2274.64   47.31
  2449.3   43.84 2528.41   33.49 2770.23   33.78  2772.7   31.79 2783.19    33.8
  4460.5   33.03 4549.96   34.49 4570.05   38.65 4767.02   35.92 5040.09   39.67
 5480.96   34.44 5820.56   34.74 5950.78   37.83 7375.72   35.96 7692.07   37.53
 7738.65   40.95 7824.31    37.3  8060.6   36.79 9338.32   45.98 9657.12   43.37
10153.42   47.6311283.57   46.24 11395.9   48.4911623.12   46.1712708.64   49.69
#Mann= 3 , 0 , 0
       0     .12       0 2770.23     .06       0 2783.19     .12       0
#XS Ineff= 2 , 0
       0                    4800       0      40
Bank Sta=2770.23,2783.19
Exp/Cntr=.3,.1

Type RM Length L Ch R = 1 ,6209    ,550.16,856.08,1061.22
XS GIS Cut Line= 5
      2092794.81      128612.555     2089330.685      128408.634
     2086566.001      130107.859        2085200.         130185.
     2081801.686      134037.962
#Sta/Elev= 30
       0   56.69  415.73   50.82 1011.82    52.9 1376.52   48.49 2444.68   46.94
 2514.05   44.98 2644.09   34.01 2793.54   36.08  3019.8   33.99 3027.86   30.83
 3040.81   33.98 5037.36   34.06 5108.61   38.02 5330.93   38.66 6077.74   35.01
 6107.94   37.19 6698.19   38.02 7085.87    35.7 7166.67   39.54  7462.2   38.22
 7790.67   44.08 8337.82   45.35 8407.21   43.1510255.37      4610322.02   43.39
10326.66   45.67 10388.9   46.6612129.22   45.8212615.83   50.0313220.92   48.22
#Mann= 3 , 0 , 0
       0     .12       0  3019.8     .06       0 3040.81     .12       0
#XS Ineff= 2 , 0
       0                    5035       0      40
Bank Sta=3019.8,3040.81
Exp/Cntr=.3,.1

Type RM Length L Ch R = 1 ,5353    ,518.09,698.11,744.94
XS GIS Cut Line= 4
 2092750.3280917  128554.2042402      2092740.57      128552.018
     2088829.371      127675.738 2085184.6269446  127462.5957959
#Sta/Elev= 30
       0   56.19  337.59   51.25  797.71    54.6 1232.29   48.92 1248.13   47.26
 1307.35   49.36 1479.25   47.01 2302.47   46.27 2396.54   43.18 2451.66   35.04
 2518.17   33.78 3514.75    34.2 3537.46   30.96 3563.53    34.3 3705.27   36.82
 3757.03   33.94 3797.03    35.5 3847.17   33.53  4176.8   35.77 4212.16   34.17
 4551.04   33.53 4731.28   35.15  6019.7   33.69 6158.46   36.76 6253.17   34.58
 6608.92   38.96 6695.45   37.89 6777.77   40.62 7561.19   46.49 7669.12    45.7
#Mann= 3 , 0 , 0
       0     .12       0 3514.75     .06       0 3563.53     .12       0
#XS Ineff= 2 , 0
       0                    6180       0      40
Bank Sta=3514.75,3563.53
Exp/Cntr=.3,.1

Type RM Length L Ch R = 1 ,4655    ,389.04,402.28,351.17
XS GIS Cut Line= 3
      2093115.41      128612.555     2088758.164      126951.264
        2085430.         126197.
#Sta/Elev= 30
       0   55.75  278.42   57.52  777.54   52.14 1100.76   55.79 1528.24   48.28
 1702.06   48.89 1902.94   46.01 1945.94   47.85 2065.82   47.54 2351.79   42.85
 2404.44   45.45 2581.73   45.04 2619.25   43.19  2657.7   34.96 2683.42   33.55
 4050.52   33.47 4064.94   29.97 4075.33   33.38 4269.46   32.77 4500.15   34.71
 4848.01   33.21 4994.71   35.71 5049.77   33.75 5374.58   32.69 6489.57    33.1
 6618.83   33.89 6739.42   37.25 6994.31   37.38 7238.54   40.69 8075.77   40.65
#Mann= 3 , 0 , 0
       0     .12       0 4050.52     .06       0 4075.33     .12       0
Bank Sta=4050.52,4075.33
Exp/Cntr=.3,.1

Type RM Length L Ch R = 1 ,4252    ,398.27,436.23,432.22
XS GIS Cut Line= 3
     2091774.453      127630.059      2086558.61      125848.249
     2085359.938       125934.64
#Sta/Elev= 30
       0   48.04  319.46   47.51  561.11   42.05  614.32   43.77  661.55   40.89
   887.7   44.49 1006.28   32.94 2598.15   32.61 2606.05   30.09 2618.29   32.69
 3241.65   32.18 3377.94   36.05 3428.01   32.49 5120.52   32.73 5194.56    33.5
 5261.48   39.46 5380.64    42.1 5854.56   40.39  5910.5   45.81 5952.05   44.96
 5967.29   48.81 5982.21   45.04 5992.89   48.29 5998.99   45.75 6029.89   47.37
 6141.98   45.06 6215.97   38.78  6390.5   38.97 6533.15   42.63 6713.57   40.68
#Mann= 3 , 0 , 0
       0     .12       0 2598.15     .06       0 2618.29     .12       0
#XS Ineff= 2 , 0
       0                    5090       0      40
Bank Sta=2598.15,2618.29
Exp/Cntr=.3,.1

Type RM Length L Ch R = 1 ,3816    ,211.49,394.04,232.91
XS GIS Cut Line= 5
     2092612.334      127568.875     2086072.296      125153.763
     2085815.824      125709.452     2085431.116      125645.334
  2085281.923919  125620.4686532
#Sta/Elev= 30
       0   56.12  269.04   57.28  400.61   55.34  444.62   51.34  500.29   54.84
  564.39   50.45  686.13   48.08  726.47   50.13  808.32   46.93  962.96    50.9
  982.62   48.22  1248.8   44.23 1436.01   46.27 1687.28   42.89 1778.71   34.54
 1852.74   32.57  3372.9   32.55 3377.79   29.28 3396.82   32.48 3532.55   34.49
 3794.28   31.92 6395.45   32.64    6411   34.61 6667.02   32.56 6934.61   39.42
 7309.08   44.26 7516.31   39.94 7608.54    41.9 7722.71   39.33    8125      40
#Mann= 3 , 0 , 0
       0     .12       0  3372.9     .06       0 3396.82     .12       0
#XS Ineff= 2 , 0
       0                    5680       0      40
Bank Sta=3372.9,3396.82
Exp/Cntr=.3,.1

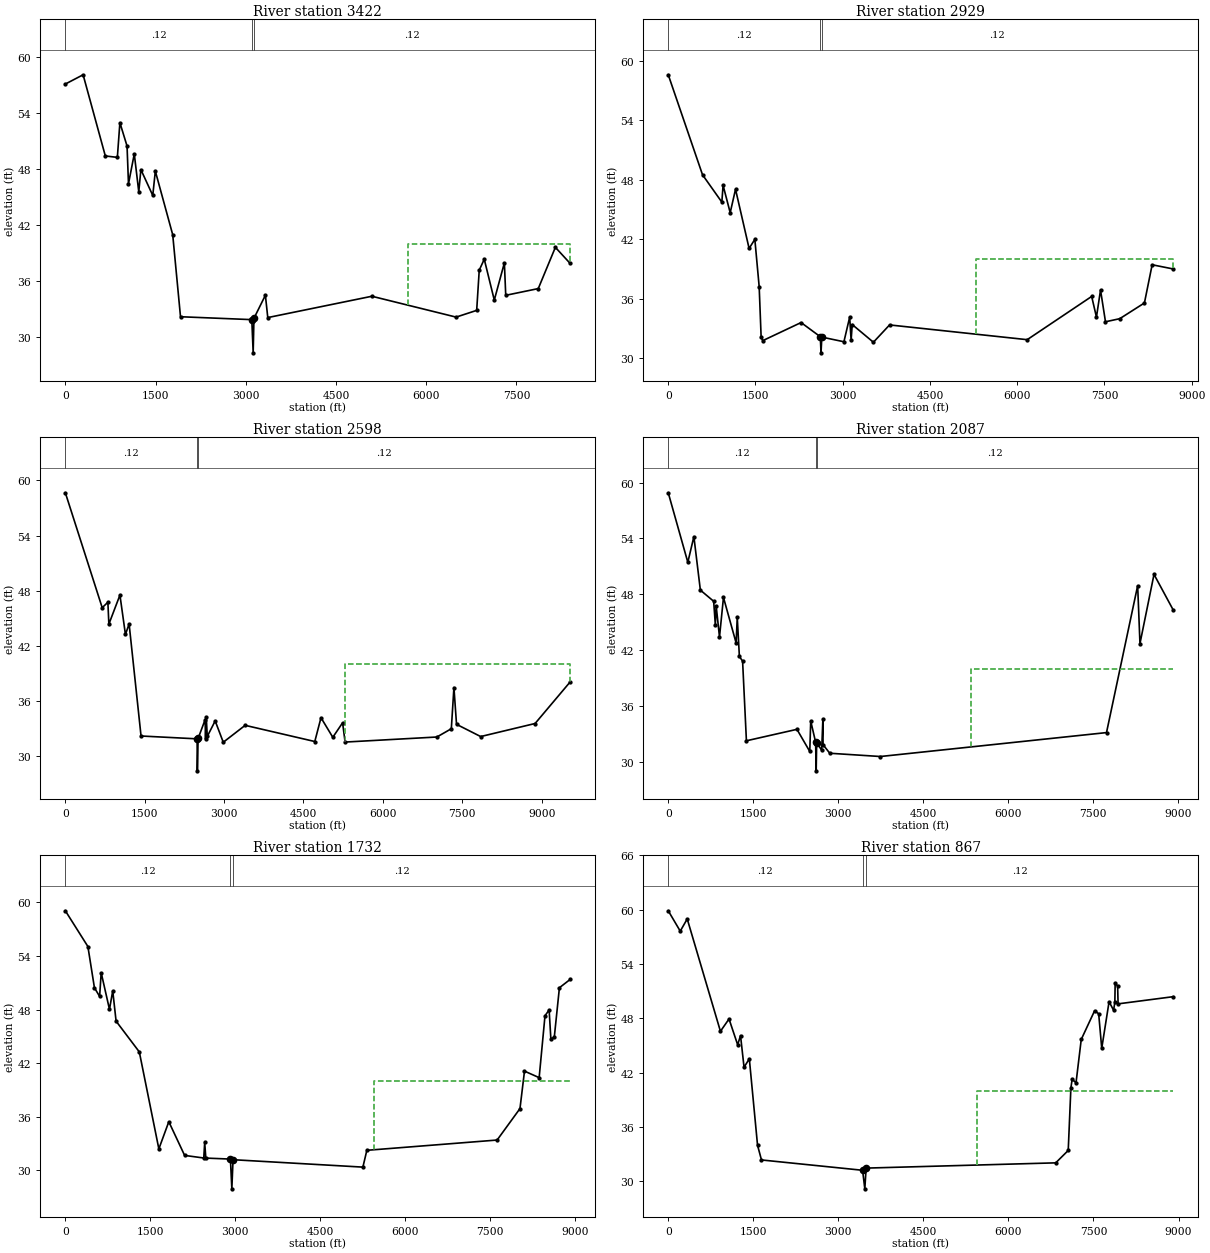
Type RM Length L Ch R = 1 ,3422    ,348.25,493.34,573.56
XS GIS Cut Line= 4
     2092703.154      127489.674     2091353.298      126895.738
     2085662.305      124714.371      2084960.38      125146.324
#Sta/Elev= 30
       0   57.07  295.39   58.06  664.79   49.38  864.73   49.23  907.04   52.94
 1025.97   50.44 1049.83    46.4 1146.21    49.6 1221.15   45.54    1256   47.92
 1453.59   45.16 1496.31   47.76 1785.24   40.96  1914.9   32.19 3100.46   31.88
 3123.15   28.33 3136.12   32.02 3326.24   34.49 3365.91    32.1 5097.14   34.38
 6497.44   32.15 6839.63   32.87  6882.1   37.17 6965.53   38.34  7132.4   33.97
 7300.04   37.95 7322.75   34.48 7863.72    35.2 8147.95   39.61 8393.66   37.89
#Mann= 3 , 0 , 0
       0     .12       0 3100.46     .06       0 3136.12     .12       0
#XS Ineff= 2 , 0
       0                    5690       0      40
Bank Sta=3100.46,3136.12
Exp/Cntr=.3,.1

Type RM Length L Ch R = 1 ,2929    ,309.95,330.57,318.96
XS GIS Cut Line= 4
     2092526.843      127312.403     2086777.594      124127.875
     2085131.898      124875.918 2084858.8057976  125000.0507137
#Sta/Elev= 30
       0   58.62  589.65   48.51  921.65   45.75  942.85   47.45 1065.25   44.68
 1156.75   47.05 1390.31   41.07    1489   41.99 1563.59    37.2 1597.02   32.14
 1623.97   31.75 2283.91   33.58 2614.57   32.15 2627.01   30.52 2640.58   32.11
 3020.64   31.64  3119.7   34.13 3144.38   31.79 3163.27   33.38 3527.66   31.59
 3805.57   33.34 6172.23   31.85 7280.82   36.22 7362.93   34.13 7433.08   36.87
 7518.19   33.66 7763.34   33.97 8187.88   35.56 8320.64   39.42    8680      39
#Mann= 3 , 0 , 0
       0     .12       0 2614.57     .06       0 2640.58     .12       0
#XS Ineff= 2 , 0
       0                    5300       0      40
Bank Sta=2614.57,2640.58
Exp/Cntr=.3,.1

Type RM Length L Ch R = 1 ,2598    ,387.63,510.64,1046.34
XS GIS Cut Line= 4
     2092511.527      127249.453        2091620.         126458.
      2086004.48      123335.188     2084900.457      124907.585
#Sta/Elev= 30
       0   58.65  696.53   46.15  803.78   46.74  822.49   44.36 1031.51   47.52
 1135.48   43.24 1204.95   44.38 1430.42   32.19 2489.64   31.88 2494.63    28.4
 2508.72   31.92 2641.43   33.97 2649.29   31.86 2662.73   34.24 2681.59   32.14
 2831.33   33.83 2984.14   31.51 3397.95   33.35 4713.62   31.59  4830.8   34.18
 5054.07   32.05 5239.24   33.63 5286.24   31.53 7020.39   32.08 7293.67   32.98
  7342.8   37.46 7391.91   33.46 7848.16   32.13 8876.53   33.55 9538.86   38.07
#Mann= 3 , 0 , 0
       0     .12       0 2489.64     .06       0 2508.72     .12       0
#XS Ineff= 2 , 0
       0                    5290       0      40
Bank Sta=2489.64,2508.72
Exp/Cntr=.3,.1

Type RM Length L Ch R = 1 ,2087    ,266.98,355.85,292.2
XS GIS Cut Line= 4
     2092539.532      127149.981     2091567.374      126383.692
     2087038.266      121271.289     2086226.228      121522.906
#Sta/Elev= 30
       0    58.9  345.88   51.43  452.81   54.19  567.41   48.44  802.61   47.24
  832.24   44.68  846.85   46.74  905.33    43.4  975.67   47.65 1199.29   42.76
 1219.05   45.52 1256.78   41.31 1313.47   40.81 1380.97   32.25 2273.48   33.48
 2500.32    31.1 2516.91   34.38  2603.7   32.09 2613.58   29.02  2621.9   32.06
 2710.93   31.23  2731.6   34.56 2735.11   31.83 2853.62   30.91 3747.72   30.56
 7742.46   33.13 8292.87   48.92 8333.66    42.7  8581.6   50.13 8918.01   46.34
#Mann= 3 , 0 , 0
       0     .12       0  2603.7     .06       0  2621.9     .12       0
#XS Ineff= 2 , 0
       0                    5350       0      40
Bank Sta=2603.7,2621.9
Exp/Cntr=.3,.1

Type RM Length L Ch R = 1 ,1732    ,866.08,864.28,574.52
XS GIS Cut Line= 3
     2092612.334      127205.539     2087247.793      121092.955
     2086499.749      121328.055
#Sta/Elev= 30
       0   59.05  398.39   55.05     514   50.43  605.56   49.47  633.22   52.12
  779.51   48.02   837.1   50.09  896.45    46.7 1306.53   43.26 1651.75   32.41
 1827.72   35.45 2106.82   31.68 2445.12   31.39  2461.4   33.13 2481.61   31.38
 2915.82   31.27 2941.03   27.94 2962.13    31.2 5255.98   30.37 5325.79   32.25
 7626.97    33.4  8030.7   36.92 8110.52   41.11  8369.5   40.38 8472.57    47.3
 8545.58   47.96 8576.87   44.66 8637.43   44.94 8727.29   50.44 8916.89   51.37
#Mann= 3 , 0 , 0
       0     .12       0 2915.82     .06       0 2962.13     .12       0
#XS Ineff= 2 , 0
       0                    5450       0      40
Bank Sta=2915.82,2962.13
Exp/Cntr=.3,.1

Type RM Length L Ch R = 1 ,867     ,867.29,867.29,867.29
XS GIS Cut Line= 3
     2092911.551      126735.341     2087760.737      120879.229
     2086692.103      121157.073
#Sta/Elev= 30
       0   59.87  211.59   57.62  334.71   58.97  920.45   46.56 1071.97   47.92
  1224.4   45.07 1274.72   46.09 1336.83   42.59 1430.03   43.52 1574.95   33.97
 1644.22   32.35 3427.73   31.21 3467.02   29.16 3490.05   31.45 6833.73   32.03
 7054.47    33.4 7101.37    40.3 7123.65   41.26 7192.02   40.87  7284.1   45.66
 7520.57   48.84 7591.73   48.49 7645.53   44.68 7774.91   49.83 7854.91   48.88
 7876.84   49.78 7882.21   51.84 7925.79   51.58    7934   49.59  8903.2   50.38
#Mann= 3 , 0 , 0
       0     .12       0 3427.73     .06       0 3490.05     .12       0
#XS Ineff= 2 , 0
       0                    5450       0      40
Bank Sta=3427.73,3490.05
Exp/Cntr=.3,.1

Chan Stop Cuts=-1